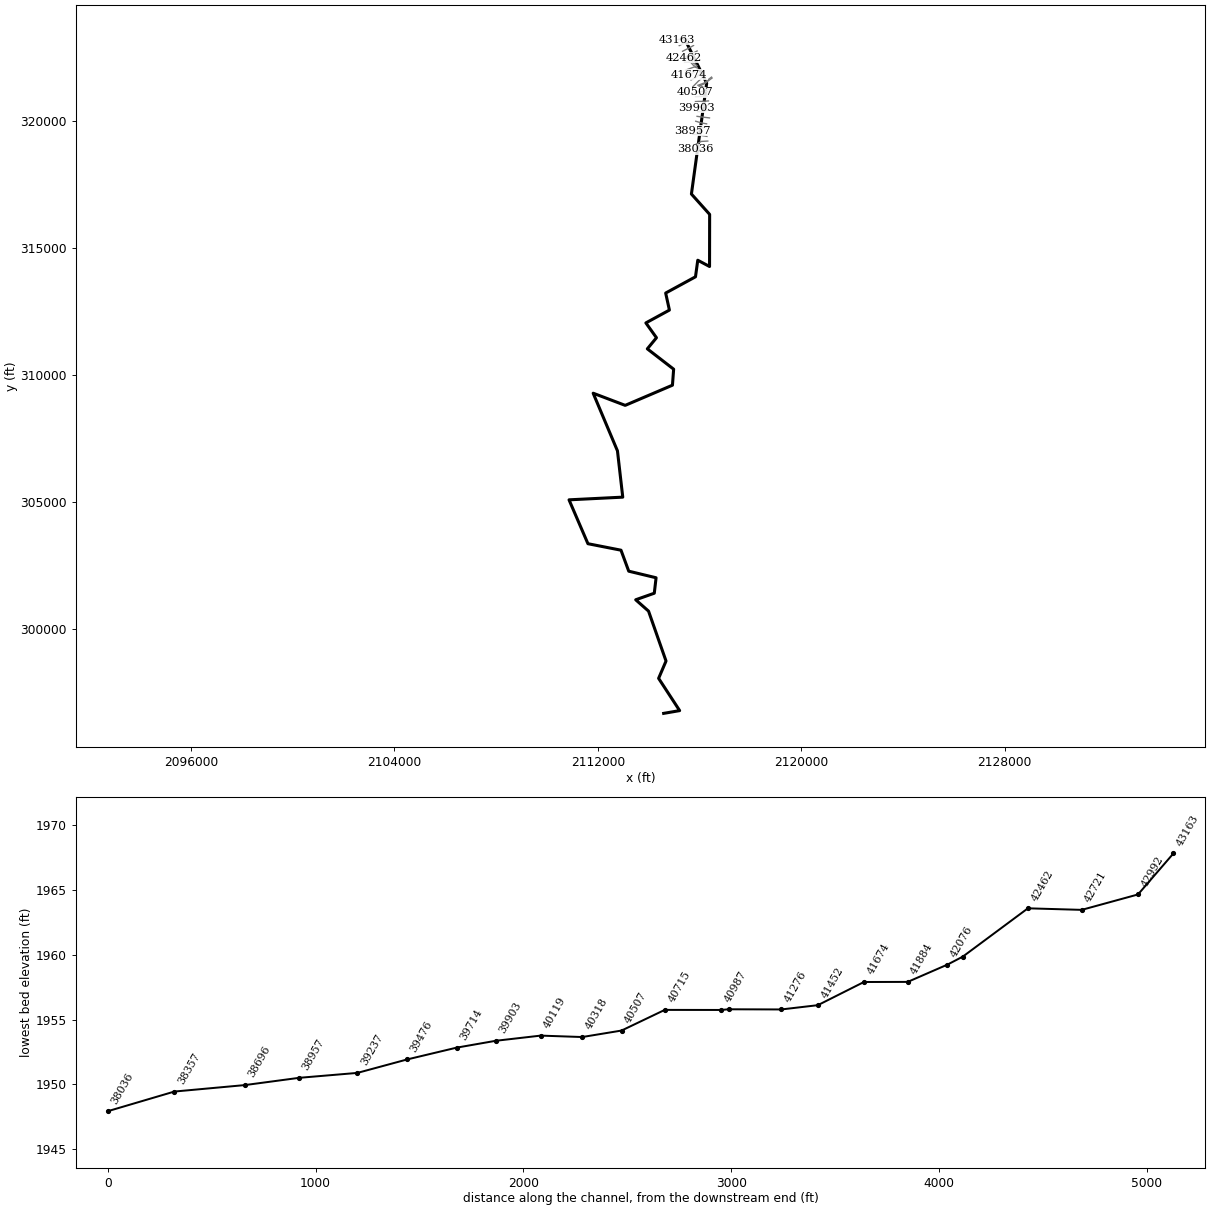
--- MLGNCK.prj (project) ---

Proj Title=MLGNCK
Current Plan=p01
Default Exp/Contr=0,0
English Units
Geom File=g01
Flow File=f01
Plan File=p01
Background Map Layer=DPs_HMS_shifted
Background Map Layer=QC_TUCKHORN
BEGIN DESCRIPTION:
Stream Name- Milligan Creek
Flood Zone: Zone A
Greenbrier County, WV
County-Wide Study
WVDHSEM-2018-3, Flood Risk Project
HEC-RAS Version: 5.0.7
General Notes:
For the Hydrology Regression was used.
END DESCRIPTION:
DSS File=dss
DSS Export Rating Curves= 0
DSS Export Rating Curve Sorted= 0
DSS Export Volume Flow Curves= 0
DXF Filename=..\..\H1\MEADOWRV4\MEADOWRV4.
DXF OffsetX= 0
DXF OffsetY= 0
DXF ScaleX= 0
DXF ScaleY= 0

--- MLGNCK.p01 (plan) ---

Plan Title=Floodplain
Program Version=5.07
Short Identifier=Floodplain
Geom File=g01
Flow File=f01
Subcritical Flow
K Sum by GR= 0
Std Step Tol= 0.01
Critical Tol= 0.01
Num of Std Step Trials= 20
Max Error Tol= 0.3
Flow Tol Ratio= 0.001
Split Flow NTrial= 30
Split Flow Tol= 0.02
Split Flow Ratio= 0.02
Log Output Level= 0
Friction Slope Method= 1
Unsteady Friction Slope Method= 2
Unsteady Bridges Friction Slope Method= 1
Parabolic Critical Depth
Global Vel Dist= 0 , 0 , 0
Global Log Level= 0
CheckData=True
Encroach Param=-1 ,0,0, 0
Computation Interval=0.1SEC
Output Interval=1MIN
Instantaneous Interval=Max Profile
Mapping Interval=1HOUR
Computation Time Step Use Courant=        0
Computation Time Step Use Time Series=    0
Computation Time Step Count To Double=0
Computation Time Step Max Doubling=0
Computation Time Step Max Halving=0
Computation Time Step Residence Courant=0
Run HTab= 0
Run UNet= 0
Run Sediment= 0
Run PostProcess= 0
Run WQNet= 0
Run RASMapper= 0
UNET Theta= 0
UNET Theta Warmup= 0
UNET ZTol= 0
UNET ZSATol= 0
UNET MxIter= 0
UNET Max Iter WO Improvement= 0
UNET MaxInSteps= 0
UNET DtIC= 0
UNET DtMin= 0
UNET MaxCRTS= 0
UNET WFStab= 0
UNET SFStab= 0
UNET WFX= 1
UNET SFX= 1
UNET 1D Methodology=Finite Difference
UNET DSS MLevel= 1
UNET Pardiso=0
UNET DZMax Abort= 0
UNET Use Existing IB Tables= 0
UNET Froude Reduction=False
UNET Froude Limit= 0
UNET Froude Power= 0
UNET D1 Cores= 0
UNET D2 Coriolis=0
UNET D2 Cores= 0
UNET D2 Theta= 1
UNET D2 Theta Warmup= 1
UNET D2 Z Tol= 0.01
UNET D2 Volume Tol= 0.01
UNET D2 Max Iterations= 20
UNET D2 Equation= 0
UNET D2 RampUpFraction=0.1
UNET D2 TimeSlices= 1
UNET D2 BCVolumeCheck=0
UNET D1D2 MaxIter= 0
UNET D1D2 ZTol=0.01
UNET D1D2 QTol=0.1
UNET D1D2 MinQTol=1
DSS File=dss
Write IC File= 0
Write IC File at Fixed DateTime=0
Write IC File at Sim End=0
Echo Input=False
Echo Parameters=False
Echo Output=False
Write Detailed= 0
HDF Write Warmup=0
HDF Write Time Slices=0
HDF Flush=0
HDF Face Node Velocities=0
HDF Compression= 1
HDF Chunk Size= 1
HDF Spatial Parts= 1
HDF Use Max Rows=0
HDF Fixed Rows= 1
Calibration Method= 0
Calibration Iterations= 20
Calibration Max Change=0.05
Calibration Tolerance=0.2
Calibration Maximum=1.5
Calibration Minimum=0.5
Calibration Optimization Method= 1
WQ AD Non Conservative
WQ ULTIMATE=-1
WQ Max Comp Step=1HOUR
WQ Output Interval=15MIN
WQ Output Selected Increments= 0
WQ Output face flow=0
WQ Output face velocity=0
WQ Output face area=0
WQ Output face dispersion=0
WQ Output cell volume=0
WQ Output cell surface area=0
WQ Output cell continuity=0
WQ Output cumulative cell continuity=0
WQ Output face conc=0
WQ Output face dconc_dx=0
WQ Output face courant=0
WQ Output face peclet=0
WQ Output face adv mass=0
WQ Output face disp mass=0
WQ Output cell mass=0
WQ Output cell source sink temp=0
WQ Output nsm pathways=0
WQ Output nsm derived pathways=0
WQ Output MaxMinRange=-1
WQ Daily Max Min Mean=-1
WQ Daily Range=0
WQ Daily Time=0
WQ Create Restart=0
WQ Fixed Restart=0
WQ System Summary=0
WQ Write To DSS=0
WQ Use Fixed Temperature=0
Sorting and Armoring Iterations= 10
XS Update Threshold= 0.02
Bed Roughness Predictor= 0
Hydraulics Update Threshold= 0.02
Energy Slope Method= 1
Volume Change Method= 1
Sediment Retention Method= 0
XS Weighting Method= 0
Number of US Weighted Cross Sections= 1
Number of DS Weighted Cross Sections= 1
Upstream XS Weight=0
Main XS Weight=1
Downstream XS Weight=0
Number of DS XS's Weighted with US Boundary= 1
Upstream Boundary Weight= 1
Weight of XSs Associated with US Boundary= 0
Number of US XS's Weighted with DS Boundary= 1
Downstream Boundary Weight= 0.5
Weight of XSs Associated with DS Boundary= 0.5
Percentile Method= 0
Sediment Output Level= 3
Mass or Volume Output= 0
Output Increment Type= 1
Profile and TS Output Increment= 1
XS Output Flag= 0
XS Output Increment= 10
Write Gradation File= 0
Read Gradation Hotstart= 0
Write HDF5 File= 1
Write Binary Output= 1
Write DSS Sediment File= 0
SV Curve= 0
Specific Gage Flag= 0

--- MLGNCK.f01 (steady flow) ---

Flow Title=MasterFlow
Program Version=5.07
Number of Profiles= 6
Profile Names=f1p,f10p,f4p,f2p,f02p,f1pplus
River Rch & RM=MLGNCK,Main            ,43163
    1400     765    1000    1190    1920    2070
River Rch & RM=MLGNCK,Main            ,42076
    1560     858    1120    1330    2140    2310
River Rch & RM=MLGNCK,Main            ,35735
    1910    1060    1370    1630    2610    2820
River Rch & RM=MLGNCK,Main            ,34475
    1910    1060    1370    1630    2610    2820
River Rch & RM=MLGNCK,Main            ,29756
    3770    2150    2750    3250    5090    5580
River Rch & RM=MLGNCK,Main            ,25279
    4210    2400    3080    3630    5670    6230
River Rch & RM=MLGNCK,Main            ,13389
    4770    2730    3490    4110    6400    7050
Boundary for River Rch & Prof#=BROADRN,Main            , 1
Up Type= 0
Dn Type= 3
Dn Slope=0.05922
Boundary for River Rch & Prof#=BROADRN,Main            , 2
Up Type= 0
Dn Type= 3
Dn Slope=0.05922
Boundary for River Rch & Prof#=BROADRN,Main            , 3
Up Type= 0
Dn Type= 3
Dn Slope=0.05922
Boundary for River Rch & Prof#=BROADRN,Main            , 4
Up Type= 0
Dn Type= 3
Dn Slope=0.05922
Boundary for River Rch & Prof#=BROADRN,Main            , 5
Up Type= 0
Dn Type= 3
Dn Slope=0.05922
Boundary for River Rch & Prof#=BROADRN,Main            , 6
Up Type= 0
Dn Type= 3
Dn Slope=0.05922
Boundary for River Rch & Prof#=LAURELBR,Main            , 1
Up Type= 0
Dn Type= 3
Dn Slope=0.04145
Boundary for River Rch & Prof#=LAURELBR,Main            , 2
Up Type= 0
Dn Type= 3
Dn Slope=0.04145
Boundary for River Rch & Prof#=LAURELBR,Main            , 3
Up Type= 0
Dn Type= 3
Dn Slope=0.04145
Boundary for River Rch & Prof#=LAURELBR,Main            , 4
Up Type= 0
Dn Type= 3
Dn Slope=0.04145
Boundary for River Rch & Prof#=LAURELBR,Main            , 5
Up Type= 0
Dn Type= 3
Dn Slope=0.04145
Boundary for River Rch & Prof#=LAURELBR,Main            , 6
Up Type= 0
Dn Type= 3
Dn Slope=0.04145
Boundary for River Rch & Prof#=LAURELCK1,Main            , 1
Up Type= 0
Dn Type= 3
Dn Slope=0.009
Boundary for River Rch & Prof#=LAURELCK1,Main            , 2
Up Type= 0
Dn Type= 3
Dn Slope=0.009
Boundary for River Rch & Prof#=LAURELCK1,Main            , 3
Up Type= 0
Dn Type= 3
Dn Slope=0.009
Boundary for River Rch & Prof#=LAURELCK1,Main            , 4
Up Type= 0
Dn Type= 3
Dn Slope=0.009
Boundary for River Rch & Prof#=LAURELCK1,Main            , 5
Up Type= 0
Dn Type= 3
Dn Slope=0.009
Boundary for River Rch & Prof#=LAURELCK1,Main            , 6
Up Type= 0
Dn Type= 3
Dn Slope=0.009
Boundary for River Rch & Prof#=MLGNCK,Main            , 1
Up Type= 0
Dn Type= 3
Dn Slope=0.0302
Boundary for River Rch & Prof#=MLGNCK,Main            , 2
Up Type= 0
Dn Type= 3
Dn Slope=0.0302
Boundary for River Rch & Prof#=MLGNCK,Main            , 3
Up Type= 0
Dn Type= 3
Dn Slope=0.0302
Boundary for River Rch & Prof#=MLGNCK,Main            , 4
Up Type= 0
Dn Type= 3
Dn Slope=0.0302
Boundary for River Rch & Prof#=MLGNCK,Main            , 5
Up Type= 0
Dn Type= 3
Dn Slope=0.0302
Boundary for River Rch & Prof#=MLGNCK,Main            , 6
Up Type= 0
Dn Type= 3
Dn Slope=0.0302
Boundary for River Rch & Prof#=MLGNCKTR3,Main            , 1
Up Type= 0
Dn Type= 3
Dn Slope=0.00395
Boundary for River Rch & Prof#=MLGNCKTR3,Main            , 2
Up Type= 0
Dn Type= 3
Dn Slope=0.00395
Boundary for River Rch & Prof#=MLGNCKTR3,Main            , 3
Up Type= 0
Dn Type= 3
Dn Slope=0.00395
Boundary for River Rch & Prof#=MLGNCKTR3,Main            , 4
Up Type= 0
Dn Type= 3
Dn Slope=0.00395
Boundary for River Rch & Prof#=MLGNCKTR3,Main            , 5
Up Type= 0
Dn Type= 3
Dn Slope=0.00395
Boundary for River Rch & Prof#=MLGNCKTR3,Main            , 6
Up Type= 0
Dn Type= 3
Dn Slope=0.00395
Boundary for River Rch & Prof#=MLGNCKTR4,Main            , 1
Up Type= 0
Dn Type= 3
Dn Slope=0.01609
Boundary for River Rch & Prof#=MLGNCKTR4,Main            , 2
Up Type= 0
Dn Type= 3
Dn Slope=0.01609
Boundary for River Rch & Prof#=MLGNCKTR4,Main            , 3
Up Type= 0
Dn Type= 3
Dn Slope=0.01609
Boundary for River Rch & Prof#=MLGNCKTR4,Main            , 4
Up Type= 0
Dn Type= 3
Dn Slope=0.01609
Boundary for River Rch & Prof#=MLGNCKTR4,Main            , 5
Up Type= 0
Dn Type= 3
Dn Slope=0.01609
Boundary for River Rch & Prof#=MLGNCKTR4,Main            , 6
Up Type= 0
Dn Type= 3
Dn Slope=0.01609
Boundary for River Rch & Prof#=TUCKHORN,Main            , 1
Up Type= 0
Dn Type= 1
Dn Known WS=2122.5
Boundary for River Rch & Prof#=TUCKHORN,Main            , 2
Up Type= 0
Dn Type= 1
Dn Known WS=2120.48
Boundary for River Rch & Prof#=TUCKHORN,Main            , 3
Up Type= 0
Dn Type= 1
Dn Known WS=2121.09
Boundary for River Rch & Prof#=TUCKHORN,Main            , 4
Up Type= 0
Dn Type= 1
Dn Known WS=2121.64
Boundary for River Rch & Prof#=TUCKHORN,Main            , 5
Up Type= 0
Dn Type= 1
Dn Known WS=2123.27
Boundary for River Rch & Prof#=TUCKHORN,Main            , 6
Up Type= 0
Dn Type= 1
Dn Known WS=2124.99
Boundary for River Rch & Prof#=TUCKHORNT2,Main            , 1
Up Type= 0
Dn Type= 3
Dn Slope=0.02818
Boundary for River Rch & Prof#=TUCKHORNT2,Main            , 2
Up Type= 0
Dn Type= 3
Dn Slope=0.02818
Boundary for River Rch & Prof#=TUCKHORNT2,Main            , 3
Up Type= 0
Dn Type= 3
Dn Slope=0.02818
Boundary for River Rch & Prof#=TUCKHORNT2,Main            , 4
Up Type= 0
Dn Type= 3
Dn Slope=0.02818
Boundary for River Rch & Prof#=TUCKHORNT2,Main            , 5
Up Type= 0
Dn Type= 3
Dn Slope=0.02818
Boundary for River Rch & Prof#=TUCKHORNT2,Main            , 6
Up Type= 0
Dn Type= 3
Dn Slope=0.02818
DSS Import GetInterval= 0
DSS Import GetPeak= 0
DSS Import FillOption= 0

--- MLGNCK.g01 (geometry) ---

Geom Title=MasterGeometry
Program Version=5.07

River Reach=MLGNCK          ,Main
Reach XY= 30
     2115405.261      323267.859     2116282.667       321503.55
     2115681.855      317138.582     2116399.043       316337.02
      2116395.39      314284.553     2115931.849      314531.948
     2115842.005      313879.605     2114668.828      313239.848
     2114815.964      312569.275     2113890.182      312064.067
     2114306.849      311480.733     2113947.473      311043.234
     2114982.629      310242.452     2114935.755      309612.244
      2113076.38      308817.973     2111815.963       309297.14
     2112772.271      307026.306     2112980.604      305204.692
     2110866.821      305099.054      2111610.58      303371.566
     2112911.239      303116.275     2113216.018      302289.832
2114291.70069883302030.851380702     2114221.075301422.261734587
     2113489.719      301164.327     2113994.927      300717.712
2114683.21296507298752.6183071212114391.44286665298070.557955514
2115219.09675086296800.421335303     2114589.831      296691.758

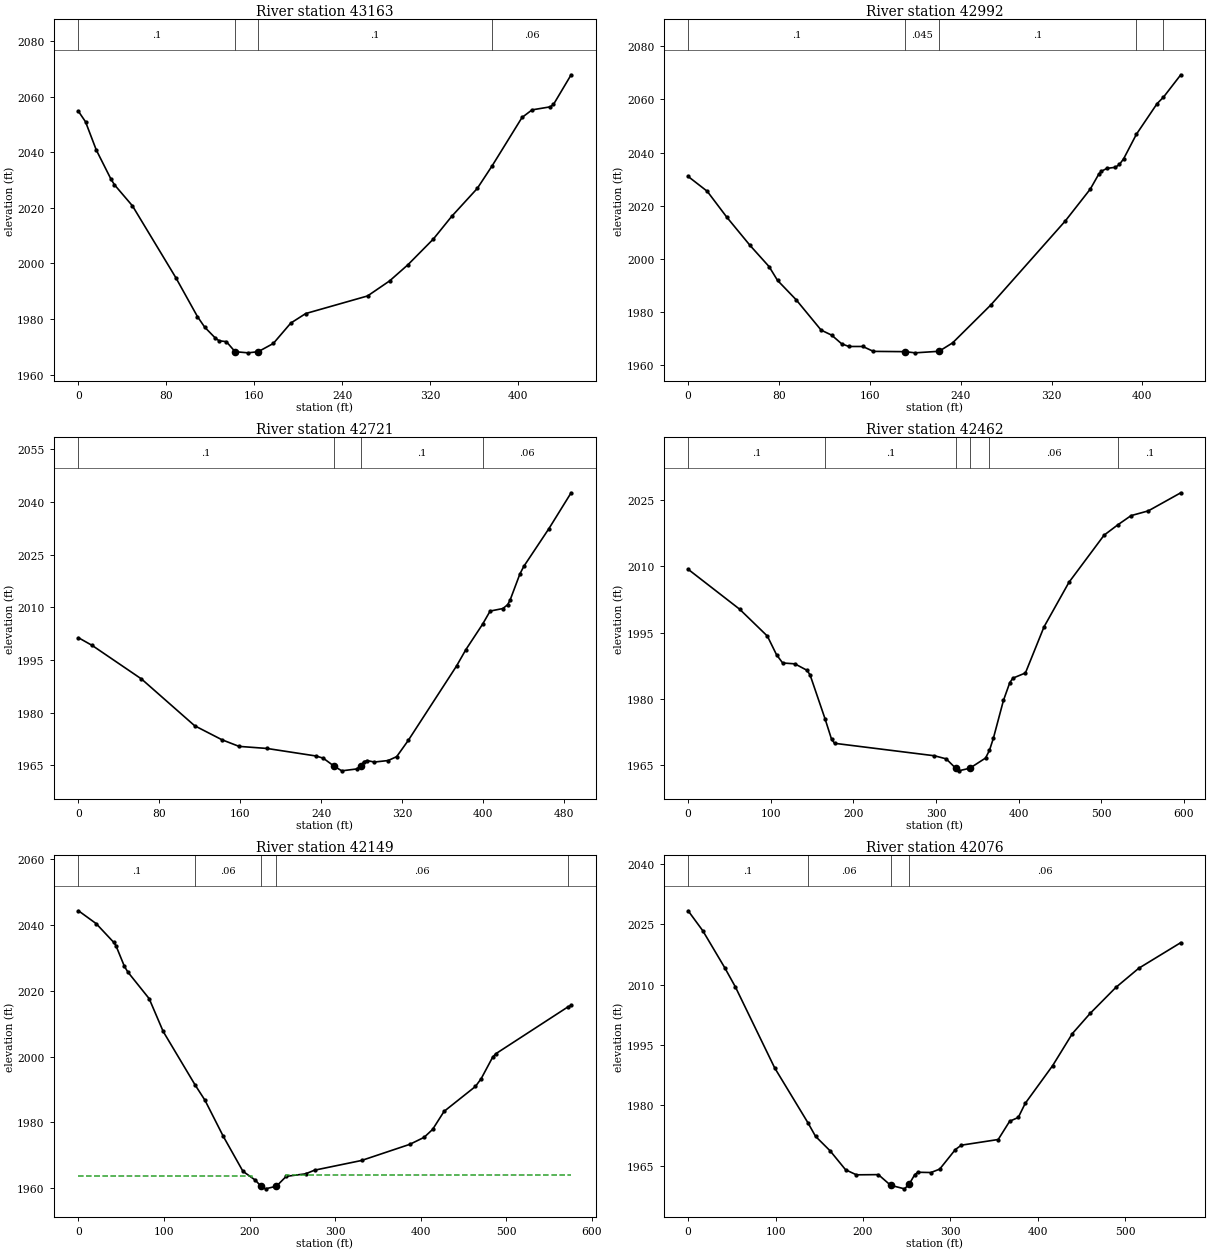
Type RM Length L Ch R = 1 ,43163   ,161.7,170.5,175
XS GIS Cut Line= 4
2115549.65780715323236.1378214892115451.22381884323240.239237668
2115317.92779301323246.3913619372115104.65415168323211.529324412
#Sta/Elev= 30
       0  2054.7     6.4 2050.96    16.2  2040.8    29.4 2030.44    32.7 2028.31
    49.1 2020.71    88.5  1994.9   108.2 1980.88   114.8 1977.07   124.6  1973.1
   127.9 1972.19   134.5 1971.86  142.421968.256   154.2 1967.84  163.481968.255
   177.2 1971.21   193.1 1978.55   206.7 1981.98   262.9  1988.3   282.9  1993.7
   299.5 1999.48   322.8  2008.8   339.4 2016.92   362.7 2026.99  376.262035.141
   403.4 2052.51   412.5 2055.24   429.1 2056.34     432 2057.19448.0615 2067.87
#Mann= 4 ,-1 , 0
       0      .1       0  142.42    .045       0  163.48      .1       0
  376.26     .06       0
Bank Sta=142.42,163.48
XS Rating Curve= 0 ,0
Exp/Cntr(USF)=0,0
Exp/Cntr=0.3,0.1

Type RM Length L Ch R = 1 ,42992   ,268.6,270.7,269.8
XS GIS Cut Line= 3
2115590.67196894323176.667286886 2115459.4266512323111.044628015
2115203.08813998322981.850018362
#Sta/Elev= 30
       0 2031.02    16.8 2025.45    33.9 2015.78    54.5 2005.08    71.3  1997.1
    78.7 1991.93    95.1 1984.64   117.1 1973.22   126.4 1971.32   135.2 1968.06
   141.5 1967.06   153.8 1967.06   163.1 1965.22   191.3 1965.11   199.8 1964.67
  220.941965.256   232.9 1968.43   266.5 1982.67   332.1 2014.28   354.1 2026.27
   361.4 2031.76   363.8 2032.96   368.7 2034.05   376.2 2034.47   379.8 2035.54
   383.5 2037.69  394.732046.903   412.9  2058.4  418.562060.859433.7919 2069.27
#Mann= 5 ,-1 , 0
       0      .1       0   191.3    .045       0  220.94      .1       0
  394.73     .06       0  418.56      .1       0
Bank Sta=191.3,220.94
XS Rating Curve= 0 ,0
Exp/Cntr(USF)=0,0
Exp/Cntr=0.3,0.1

Type RM Length L Ch R = 1 ,42721   ,259.2,258.9,259.9
XS GIS Cut Line= 4
2115764.98215657322985.9514345412115574.26630423322879.314613875
2115449.17311075322817.7933711832115334.33345773322758.322836581
#Sta/Elev= 30
       0 2001.35    13.5 1999.17    62.3 1989.62   114.9 1976.31   141.9 1972.32
   158.8 1970.44   186.4 1969.85   234.8 1967.71   242.1 1967.08  252.73 1964.82
   260.4 1963.48     275 1964.01  278.981964.819   282.3 1966.08   285.3 1966.41
   292.6 1965.98   306.2 1966.41   314.7 1967.52   326.2 1972.16   373.9 1993.31
   383.1 1997.96  399.712005.225   407.1 2008.94   419.7 2009.66   424.5 2010.76
     427 2012.17   436.6 2019.53   440.4 2021.65   465.3 2032.42487.2315  2042.6
#Mann= 4 ,-1 , 0
       0      .1       0  252.73    .045       0  278.98      .1       0
  399.71     .06       0
Bank Sta=252.73,278.98
XS Rating Curve= 0 ,0
Exp/Cntr(USF)=0,0
Exp/Cntr=0.3,0.1

Type RM Length L Ch R = 1 ,42462   ,329.4,313.1,306.1
XS GIS Cut Line= 4
2115907.29066154322770.5514832862115656.31242961322640.557629821
2115563.00001004322581.3525084412115375.73163698322502.841369219
#Sta/Elev= 30
       0 2009.36    62.3  2000.3    95.9 1994.19     107 1989.95   114.4 1988.09
   129.2 1987.89   143.9 1986.42   147.6 1985.36  165.771975.366   173.5 1970.81
   177.2 1969.85   298.1 1967.02   312.3 1966.32  323.84 1964.19   327.2  1963.6
  340.851964.189   359.9  1966.5  364.661968.254   369.4 1970.99   381.6 1979.59
   389.3 1983.64   393.1 1984.65   408.2 1985.82   430.7 1996.29   460.8 2006.38
   503.4 2017.11  520.14 2019.47     536 2021.54   556.9 2022.62596.2156 2026.73
#Mann= 6 ,-1 , 0
       0      .1       0  165.77      .1       0  323.84    .045       0
  340.85      .1       0  364.66     .06       0  520.14      .1       0
Bank Sta=323.84,340.85
XS Rating Curve= 0 ,0
Exp/Cntr(USF)=0,0
Exp/Cntr=0.5,0.3

Type RM Length L Ch R = 1 ,42149   ,72,73.7,73.9
XS GIS Cut Line= 4
2115900.93979098 322190.695772172115754.28360701322302.369747117
2115652.02791911322469.207974749 2115459.6257695322505.535653346
#Sta/Elev= 30
       0 2044.24    20.7 2040.34    41.3 2034.63    43.8 2033.65    53.7 2027.36
    57.8 2025.62    82.6 2017.58      99 2007.62  136.411991.349   147.8 1986.77
   169.2 1975.82   192.2  1965.2   206.7 1962.51  213.221960.675   218.6 1959.87
  231.421960.676   242.8 1963.66   265.4 1964.42   275.9 1965.53   330.8 1968.47
   387.2 1973.37   403.9 1975.48   413.9  1977.9   427.3 1983.37     464 1990.94
   470.7 1993.31     484 1999.77   487.7 2000.85  572.242015.102575.8173 2015.52
#Mann= 5 ,-1 , 0
       0      .1       0  136.41     .06       0  213.22    .045       0
  231.42     .06       0  572.24      .1       0
#XS Ineff= 2 , 0
          202.98  1963.8  242.17         1964.02
Permanent Ineff=
       F       F
Bank Sta=213.22,231.42
XS Rating Curve= 0 ,0
Exp/Cntr(USF)=0,0
Exp/Cntr=0.5,0.3

Type RM Length L Ch R = 1 ,42076   ,174.5,191.3,201.3
XS GIS Cut Line= 4
2115894.21244309322123.4222932872115763.45495542322200.674033009
2115653.37338869322327.9336690932115409.84339513 322323.89726036
#Sta/Elev= 30
       02028.382  16.763 2023.42  42.0812014.151  54.0582009.456  98.9561989.349
 137.0631975.682 145.7621972.312 162.4721968.702  180.171963.993 192.5611962.739
 217.6351962.789  231.671960.141 247.5361959.255  252.741960.356 259.2531962.767
 262.7691963.376 277.814 1963.31 287.8441964.159 305.7731969.023 312.6051970.109
 354.7891971.518 367.9151976.063 377.758    1977 385.6511980.485 417.134  1989.9
 439.6681997.856  459.892002.846 489.3222009.311 515.5722014.086 563.7012020.465
#Mann= 4 ,-1 , 0
       0      .1       0 137.063     .06       0  231.67    .045       0
  252.74     .06       0
Bank Sta=231.67,252.74
XS Rating Curve= 0 ,0
Exp/Cntr(USF)=0,0
Exp/Cntr=0.5,0.3

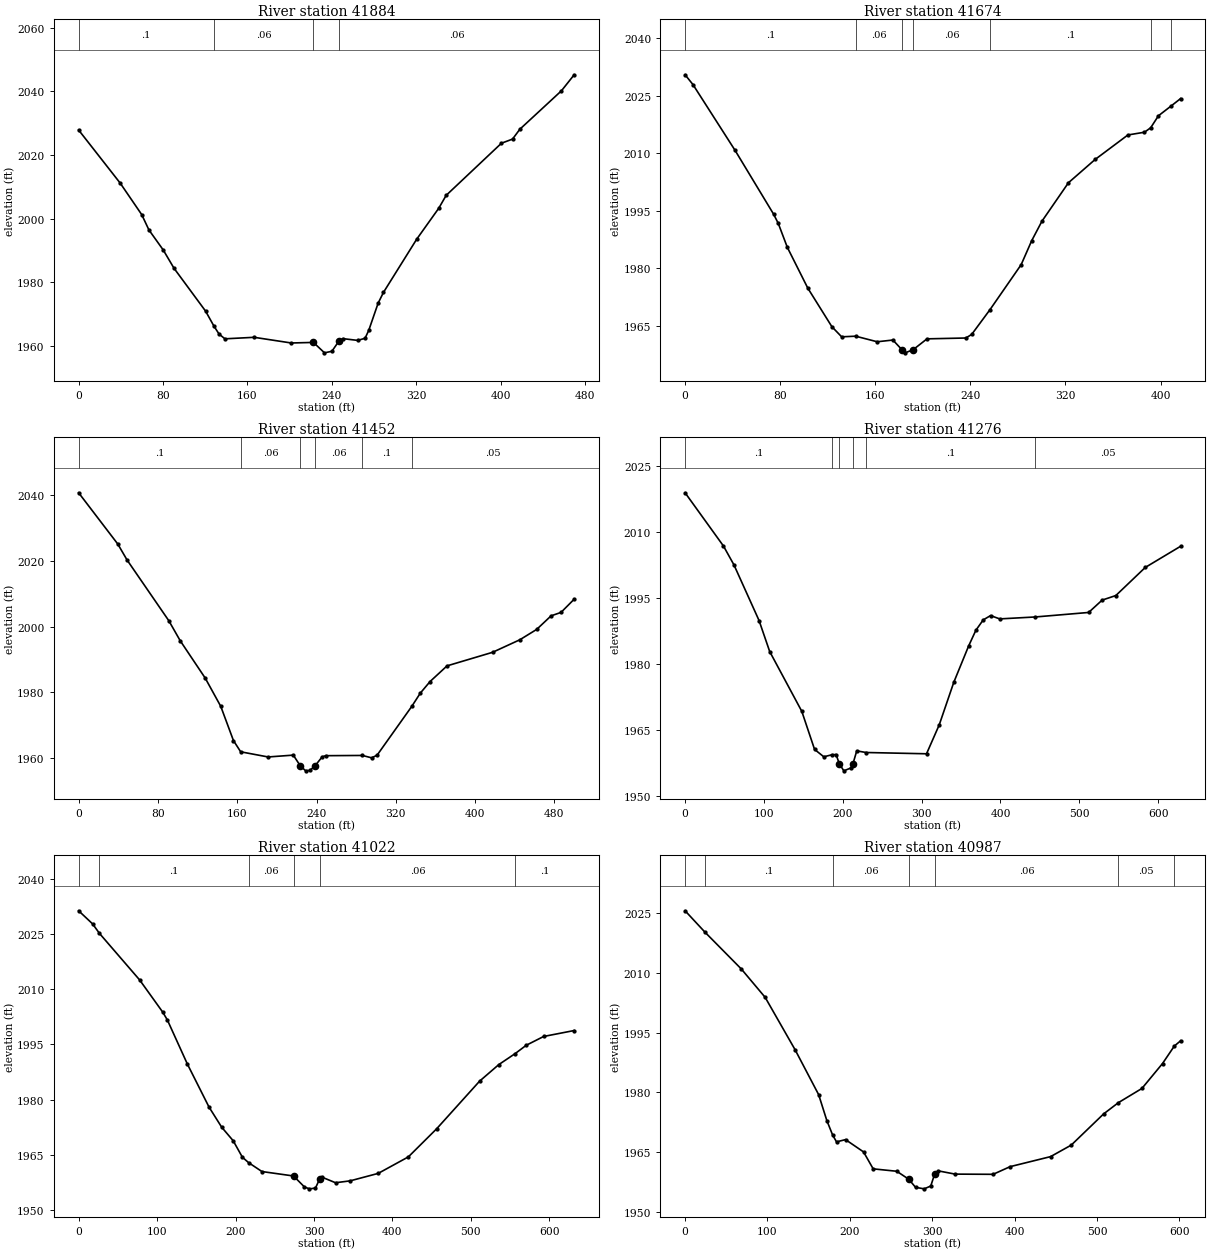
Type RM Length L Ch R = 1 ,41884   ,205.6,210.6,212.1
XS GIS Cut Line= 3
 2115899.5943214322111.3130670872115791.24317172322140.540081933
2115455.58936077 322017.13019665
#Sta/Elev= 30
       02027.849  39.4482011.169  59.8362001.289  66.6331996.499  80.2251990.194
  90.4191984.471 120.4081970.994 128.2451966.331 133.1871963.796 138.7321962.317
 166.4131962.791 201.6521961.009 222.6251961.188 233.1121957.918 240.1031958.406
 247.0941961.739  250.591962.373 264.5721961.824 271.5631962.486 275.059 1964.96
 283.9821973.516 289.0411976.897 320.5011993.567 341.474 2003.31 348.4652007.339
 400.8992023.708 411.3852024.998 418.3772028.107  457.782040.163 469.8462045.186
#Mann= 4 ,-1 , 0
       0      .1       0 128.245     .06       0 222.625    .045       0
 247.094     .06       0
Bank Sta=222.625,247.094
XS Rating Curve= 0 ,0
Exp/Cntr(USF)=0,0
Exp/Cntr=0.3,0.1

Type RM Length L Ch R = 1 ,41674   ,222.5,221.8,222.3
XS GIS Cut Line= 4
2115945.34028704322046.7305273592115813.48426843321968.693291854
2115746.21078955321912.1835695912115591.48178811321828.764455776
#Sta/Elev= 30
       0 2030.45     6.6  2027.9    42.1  2010.7    74.5 1994.06    78.4 1991.66
      86 1985.43   103.2  1974.8   123.5 1964.72   131.7 1962.09  143.481962.252
   161.6  1960.8   174.8 1961.25   182.51958.702     185 1957.91  191.721958.703
   203.5 1961.56   236.2 1961.78   241.1 1962.72  256.511969.187   282.7 1980.91
   291.6 1987.19   300.2 1992.26   322.5 2002.29   344.9 2008.35   372.5 2014.75
   386.4 2015.46  391.642016.622   398.2 2019.76  408.582022.243416.8599 2024.25
#Mann= 7 ,-1 , 0
       0      .1       0  143.48     .06       0   182.5    .045       0
  191.72     .06       0  256.51      .1       0  391.64     .05       0
  408.58      .1       0
Bank Sta=182.5,191.72
XS Rating Curve= 0 ,0
Exp/Cntr(USF)=0,0
Exp/Cntr=0.3,0.1

Type RM Length L Ch R = 1 ,41452   ,178.8,175.7,178.9
XS GIS Cut Line= 4
2116079.88724481321906.801691281     2115935.922321791.091307601
2115839.04819041321715.7450112512115666.82808446 321629.63495828
#Sta/Elev= 30
       0  2040.7    39.5 2025.11    48.9 2020.24      91 2001.78   102.5 1995.69
   127.7 1984.34   143.4 1975.74   156.2 1965.33   163.51961.911   191.2 1960.34
   216.6  1960.9  223.731957.606   229.1 1956.12   233.3 1956.25  238.421957.609
   245.7 1960.37   249.4 1960.73  286.28  1960.8   295.6 1960.08   301.1 1960.87
  336.051975.693   344.8 1979.78   354.6 1983.29   371.7 1988.05   417.6 1992.17
   445.1 1995.98   462.1 1999.13   476.7 2003.27   486.7 2004.31499.9758 2008.33
#Mann= 6 ,-1 , 0
       0      .1       0   163.5     .06       0  223.73    .045       0
  238.42     .06       0  286.28      .1       0  336.05     .05       0
Bank Sta=223.73,238.42
XS Rating Curve= 0 ,0
Exp/Cntr(USF)=0,0
Exp/Cntr=0.3,0.1

Type RM Length L Ch R = 1 ,41276   ,253.8,254,247.3
XS GIS Cut Line= 4
2116186.17934145  321803.2005338 2116074.5053665321684.799210964
2115952.06763493321579.8525839062115738.13797208  321363.2319819
#Sta/Elev= 30
       0 2018.87    48.7 2006.78      62  2002.5    93.8 1989.89   107.3 1982.85
     148 1969.29   164.2 1960.65   175.9 1958.98   186.41959.442   191.5 1959.49
  195.511957.421   201.3 1955.79   210.8 1956.48  212.931957.422   217.7 1960.32
  229.52 1959.95   306.2 1959.66   322.3 1966.22   340.8 1975.89   359.6 1984.12
   368.8 1987.69   378.1 1990.03   387.4 1991.01     399 1990.26  443.961990.695
   511.8 1991.72   528.9 1994.52   546.3 1995.56   583.6 2001.93628.4683 2006.74
#Mann= 6 ,-1 , 0
       0      .1       0   186.4     .06       0  195.51    .045       0
  212.93     .06       0  229.52      .1       0  443.96     .05       0
Bank Sta=195.51,212.93
XS Rating Curve= 0 ,0
Exp/Cntr(USF)=0,0
Exp/Cntr=0.5,0.3

Type RM Length L Ch R = 1 ,41022   ,36,35,34.3
XS GIS Cut Line= 4
2116472.76436149321741.3089332272116295.65187106321604.790899668
2116185.70294809321510.3096035022115938.61293915321419.741704162
#Sta/Elev= 30
       02031.283  17.8592027.714  26.5092025.155  77.766 2012.51  107.122003.801
 113.1332001.639 138.5871989.698 166.2351977.996 182.3581972.539 197.0681968.846
 208.7641964.388 216.692 1962.91 233.6881960.499 273.9881959.291 287.9471956.295
 294.2491955.803 301.9061956.002  307.251958.448 310.8181958.921 327.4981957.458
 346.1111957.969 381.9181959.996 420.3551964.477 456.3931972.096 511.2061985.041
 535.6661989.531 556.6321992.531 570.6091994.771 592.8461997.165 631.7531998.776
#Mann= 6 ,-1 , 0
       0     .05       0  26.509      .1       0 216.692     .06       0
 273.988    .045       0  307.25     .06       0 556.632      .1       0
Bank Sta=273.988,307.25
XS Rating Curve= 0 ,0
Exp/Cntr(USF)=0,0
Exp/Cntr=0.5,0.3

Type RM Length L Ch R = 1 ,40987   ,286.2,271.7,245.4
XS GIS Cut Line= 4
2116493.83113567321704.1645803172116326.54271564321580.517491556
 2116204.3353536321484.9760510632115985.70437437321390.141373453
#Sta/Elev= 30
       02025.589  24.2652020.184  68.2642010.965  97.2082003.835  133.541990.675
 162.0981979.409 172.0541972.889 179.0911969.255 183.7831967.551 194.7361968.115
 216.5931965.024 228.2791960.772 256.9271960.164 271.5381958.151 279.6981956.127
 290.2431955.751 298.1721956.462 302.7361959.361 306.9011960.281 327.7231959.449
 373.8621959.398 394.4941961.324 443.5891963.841 468.6951966.738  507.961974.567
 525.8411977.389 554.4511980.963 579.4841987.228 593.7891991.612 601.4591992.941
#Mann= 7 ,-1 , 0
       0     .05       0  24.265      .1       0 179.091     .06       0
 271.538    .045       0 302.736     .06       0 525.841     .05       0
 593.789      .1       0
Bank Sta=271.538,302.736
XS Rating Curve= 0 ,0
Exp/Cntr(USF)=0,0
Exp/Cntr=0.5,0.3

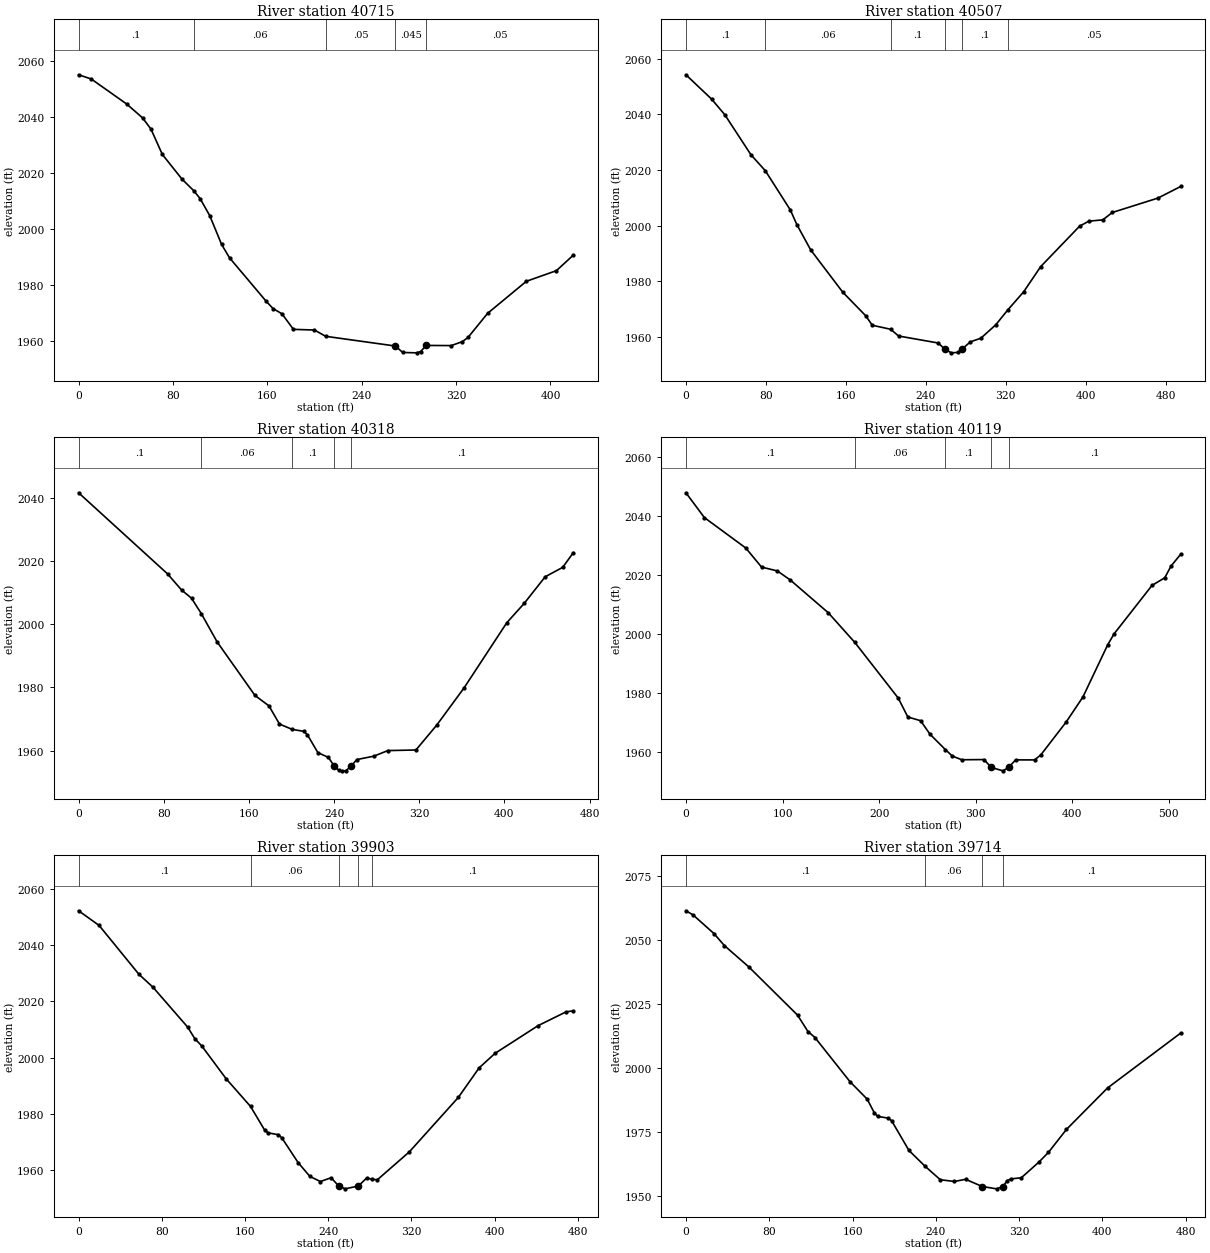
Type RM Length L Ch R = 1 ,40715   ,200,207.9,214
XS GIS Cut Line= 4
2116377.23602148321259.6308244192116214.59362805321293.014809419
2116059.57882392321395.7429579512115992.43172226321390.141373453
#Sta/Elev= 30
       02055.089  10.6982053.594  40.8412044.621  54.2382039.692  61.3492035.684
  70.9852026.634  87.7312017.775  97.7782013.603 103.0322010.833 111.1752004.765
 121.2231994.484 127.922 1989.71 158.6091974.378 164.7631971.592 172.4121969.695
 182.1141964.145 199.9511963.906 209.4191961.662 268.5981958.184 274.7451955.883
 286.5531955.756 289.9031956.205 294.6371958.399 315.9411958.349  325.411959.782
 330.1441961.277 346.7141969.866 379.5611981.316 405.0431985.118 419.3781990.667
#Mann= 5 ,-1 , 0
       0      .1       0  97.778     .06       0 209.419     .05       0
 268.598    .045       0 294.637     .05       0
Bank Sta=268.598,294.637
XS Rating Curve= 0 ,0
Exp/Cntr(USF)=0,0
Exp/Cntr=0.3,0.1

Type RM Length L Ch R = 1 ,40507   ,190.1,189.2,189.3
XS GIS Cut Line= 3
2116330.14458626 321172.175301872116131.01508876321176.211710603
2115836.35725125321147.956849472
#Sta/Elev= 30
       0 2054.28    25.7 2045.52    38.9  2039.9    65.1 2025.47   79.512019.709
   104.5  2005.6     111 2000.34   124.9 1991.21     157 1975.98     180 1967.48
   186.5 1964.09  204.921962.646   212.8 1960.22   252.4 1957.71   259.41955.434
   265.6 1954.16   272.2 1954.32  276.041955.432   284.7 1958.11   295.2 1959.43
     310 1964.21  321.86 1969.49   338.1 1976.17   355.1 1985.22     394 1999.76
   403.2 2001.57   417.2 2002.04   426.8  2004.7   472.4 2009.88495.1798 2014.06
#Mann= 6 ,-1 , 0
       0      .1       0   79.51     .06       0  204.92      .1       0
   259.4    .045       0  276.04      .1       0  321.86     .05       0
Bank Sta=259.4,276.04
XS Rating Curve= 0 ,0
Exp/Cntr(USF)=0,0
Exp/Cntr=0.3,0.1

Type RM Length L Ch R = 1 ,40318   ,198.1,199.7,197.3
XS GIS Cut Line= 3
2116305.92613386320991.8823784622116114.86945383320983.809560995
2115841.73912956320969.009395641
#Sta/Elev= 30
       0 2041.54    83.6  2015.9    96.7 2010.82   106.1 2008.21  115.232003.378
   130.1 1994.43   165.7 1977.48   178.8  1974.2   188.7 1968.45  200.561966.771
   211.7 1966.13     215 1965.02   224.8 1959.41   234.7  1957.9  240.061955.203
   244.5 1953.77   247.8 1953.66   251.1 1953.69  256.161955.201   261.3 1957.22
   277.4  1958.3   290.5 1960.06   316.9 1960.25   336.5 1968.14   362.1 1979.87
   402.2 2000.45   418.7 2006.62   438.3 2014.99   454.8 2017.98464.7582 2022.63
#Mann= 5 ,-1 , 0
       0      .1       0  115.23     .06       0  200.56      .1       0
  240.06    .045       0  256.16      .1       0
Bank Sta=240.06,256.16
XS Rating Curve= 0 ,0
Exp/Cntr(USF)=0,0
Exp/Cntr=0.3,0.1

Type RM Length L Ch R = 1 ,40119   ,213,216.1,218.3
XS GIS Cut Line= 4
2116353.01756908320803.5166375872116102.76022763320784.680063499
2115978.97702648320786.0255330772115841.73912956320779.298185189
#Sta/Elev= 30
       0 2047.92    19.1 2039.52    61.9 2029.23    78.3 2022.76    94.6 2021.46
     108 2018.39   147.4 2007.28  174.821997.256   219.8 1978.39   229.7    1972
   242.9 1970.75   252.7 1966.15  268.531960.983   275.7 1958.79   285.5 1957.52
   308.5 1957.59  316.141954.916   328.2 1953.77  333.971954.916   341.3 1957.48
     361 1957.47   367.6 1959.26   393.8 1970.38     411  1978.8   436.5 1996.37
   443.1  2000.1   482.5 2016.56   495.7 2019.15   502.2 2023.12512.1584  2027.1
#Mann= 5 ,-1 , 0
       0      .1       0  174.82     .06       0  268.53      .1       0
  316.14    .045       0  333.97      .1       0
Bank Sta=316.14,333.97
XS Rating Curve= 0 ,0
Exp/Cntr(USF)=0,0
Exp/Cntr=0.3,0.1

Type RM Length L Ch R = 1 ,39903   ,188.7,188.4,188.1
XS GIS Cut Line= 4
2116338.21740372320635.3329403782116111.49949372320586.831905187
2116012.20383888320557.7697623092115874.15866021320532.340387291
#Sta/Elev= 30
       0 2052.19    19.7 2046.99      58 2029.62    71.5 2025.03     105 2010.79
   111.7 2006.75   118.4 2004.17   141.9 1992.47  165.331982.648   178.8  1974.3
   182.2 1973.27   192.2  1972.6   195.6 1971.39   211.1 1962.68   222.4 1957.78
   232.5 1955.97   242.8 1957.32  250.061954.389   256.3 1953.37  269.031954.389
     277 1957.23  281.931956.794   287.2 1956.58     318 1966.51   365.1 1985.86
   385.1 1996.36   400.4 2001.52   441.8 2011.37   468.5 2016.23475.6768 2016.66
#Mann= 5 ,-1 , 0
       0      .1       0  165.33     .06       0  250.06    .045       0
  269.03     .06       0  281.93      .1       0
Bank Sta=250.06,269.03
XS Rating Curve= 0 ,0
Exp/Cntr(USF)=0,0
Exp/Cntr=0.3,0.1

Type RM Length L Ch R = 1 ,39714   ,239.3,237.8,232.8
XS GIS Cut Line= 4
2116399.69907725320453.6304169972116156.30363065320405.193512201
2116059.42982106320380.9750598022115932.28294597320380.975059802
#Sta/Elev= 30
       0 2061.43     6.8 2059.83    26.9 2052.54    36.9 2047.85    60.4 2039.51
   107.2 2020.68   117.2 2014.28   123.9 2011.94   157.6 1994.67   174.1 1987.86
   180.8 1982.62   184.1 1981.12   194.2 1980.47   197.5 1979.47   214.2 1967.83
  229.741961.639   244.3  1956.4   257.8 1955.72   268.6 1956.56   284.6 1953.75
   298.4 1952.84  304.321953.751   308.5 1955.95   311.9 1956.72   322.1 1957.16
     339 1963.28   348.1 1967.05   365.5 1976.06   404.9 1992.22475.1703 2013.67
#Mann= 4 ,-1 , 0
       0      .1       0  229.74     .06       0   284.6    .045       0
  304.32      .1       0
Bank Sta=284.6,304.32
XS Rating Curve= 0 ,0
Exp/Cntr(USF)=0,0
Exp/Cntr=0.3,0.1

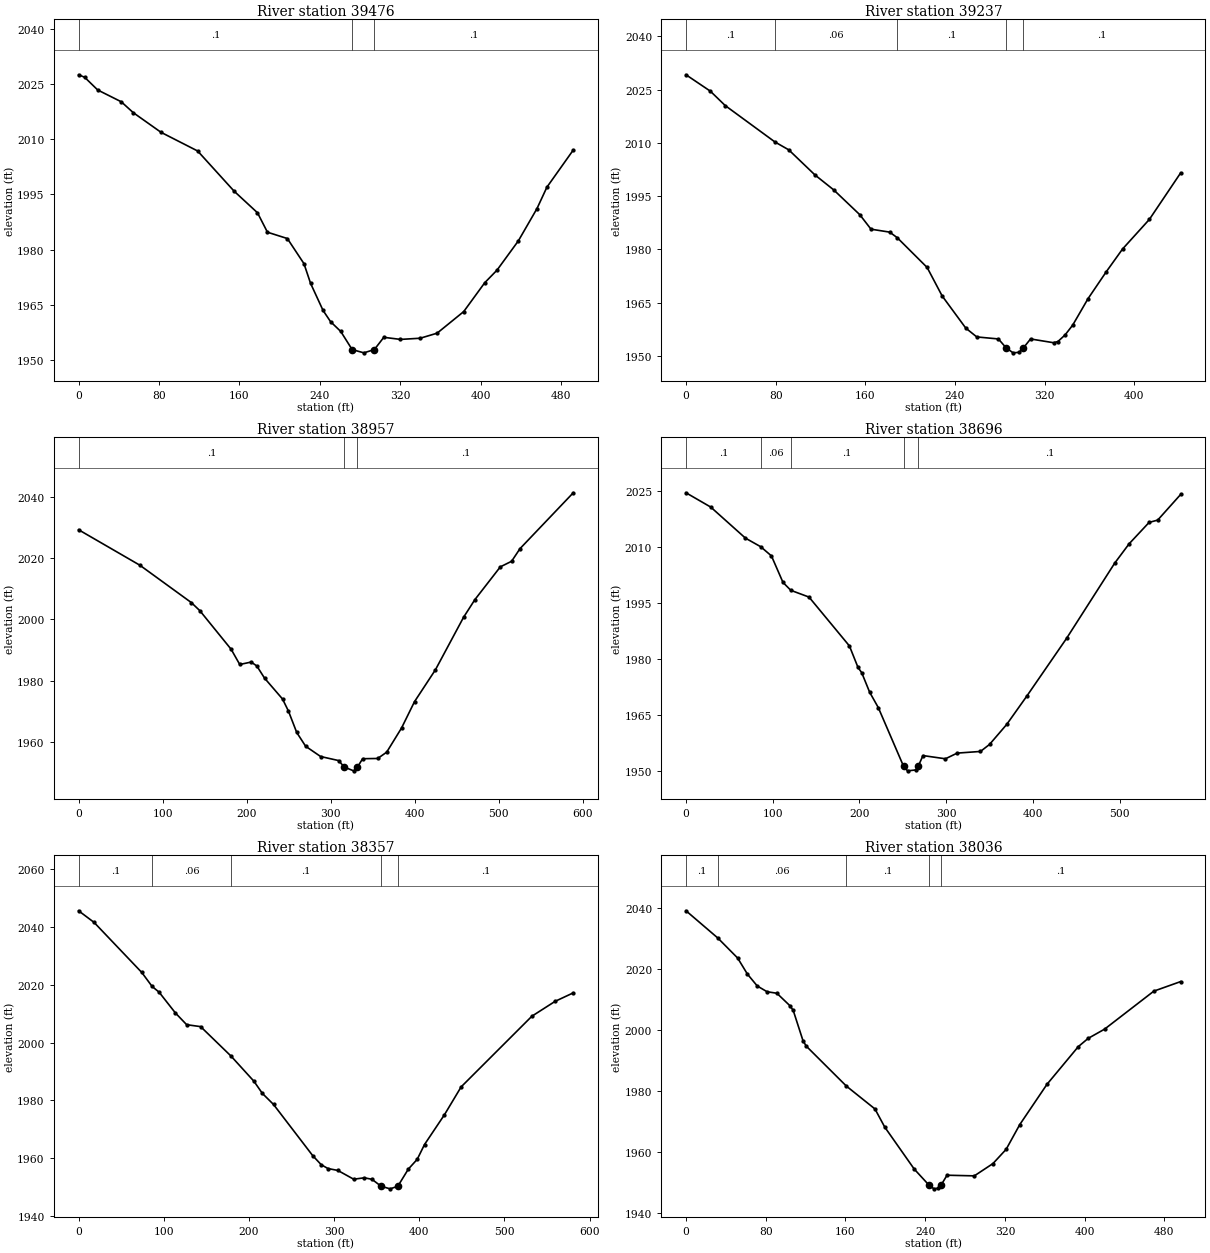
Type RM Length L Ch R = 1 ,39476   ,242.6,239.4,237.5
XS GIS Cut Line= 4
2116392.43354153320135.1577679612116151.45994017320164.219910839
 2116067.9062794320175.1182144182115904.43172571320196.914821576
#Sta/Elev= 30
       0 2027.49       6 2026.82      19 2023.36    42.4 2020.16    54.4 2017.19
      82 2011.85   118.4 2006.78   154.7 1995.85   177.9 1989.99   187.8 1984.71
   207.6 1982.99   224.1 1976.17   230.7  1970.8   243.1 1963.45   250.6 1960.39
   260.7 1957.74  272.031952.816   283.7 1951.93   294.11952.818   303.5 1956.15
   320.1 1955.58   339.7  1955.9   356.5 1957.27     383 1963.15   403.9 1970.99
   416.1 1974.41   437.3 1982.36   455.8 1991.12   465.7 1996.95491.9024 2007.04
#Mann= 3 ,-1 , 0
       0      .1       0  272.03    .045       0   294.1      .1       0
Bank Sta=272.03,294.1
XS Rating Curve= 0 ,0
Exp/Cntr(USF)=0,0
Exp/Cntr=0.3,0.1

Type RM Length L Ch R = 1 ,39237   ,274.9,280.1,285
XS GIS Cut Line= 3
2116279.81773788319901.4497023192116063.06258892319941.410148776
2115851.15113044320004.378125011
#Sta/Elev= 30
       0 2029.19    21.7 2024.58      35 2020.52   79.33 2010.28    91.7 2008.05
   115.1 2000.98   131.8 1996.78   155.1 1989.79   165.1 1985.71   181.8 1984.88
  188.521983.313   215.2 1974.93   228.6 1966.91   249.7 1957.85   259.5 1955.37
   278.8  1954.8  285.671952.311   291.9 1950.89   297.2 1951.03  301.171952.313
   307.5  1954.8     328 1953.74   331.9 1954.07   338.3 1955.93   345.1 1958.69
   358.8 1966.15     375 1973.69   389.6 1980.13   413.6 1988.49441.4767 2001.57
#Mann= 5 ,-1 , 0
       0      .1       0   79.33     .06       0  188.52      .1       0
  285.67    .045       0  301.17      .1       0
Bank Sta=285.67,301.17
XS Rating Curve= 0 ,0
Exp/Cntr(USF)=0,0
Exp/Cntr=0.3,0.1

Type RM Length L Ch R = 1 ,38957   ,266.1,260.8,255.3
XS GIS Cut Line= 4
2116279.81773788319787.6229760482116026.73491032319721.022231953
2115916.54095191319673.7962497762115714.31687439 319630.20303546
#Sta/Elev= 30
       0 2029.28    72.9 2017.69     134 2005.51   144.2 2002.85   181.5 1990.22
   191.7 1985.26   205.3 1986.05     212 1984.78   221.2  1980.8   242.6 1973.98
   249.6 1970.06   259.5 1963.04   270.1 1958.54   287.9 1955.19   309.4 1953.86
     3161951.745   327.2 1950.51  331.731951.747   337.9 1954.47   355.8 1954.55
   366.5 1956.61   384.2 1964.51   399.6 1973.11   424.5 1983.53     458  2000.7
   471.4 2006.44   501.7 2017.16   515.1 2018.98   525.1 2023.11588.4562 2041.36
#Mann= 3 ,-1 , 0
       0      .1       0     316    .045       0  331.73      .1       0
Bank Sta=316,331.73
XS Rating Curve= 0 ,0
Exp/Cntr(USF)=0,0
Exp/Cntr=0.3,0.1

Type RM Length L Ch R = 1 ,38696   ,332.3,339.4,346.2
XS GIS Cut Line= 4
 2116293.1378867319407.3932733962116072.74996988319446.142797234
2115934.70479121319477.6267853512115730.05886845 319488.52508893
#Sta/Elev= 30
       0 2024.47    28.5 2020.64    68.5 2012.32   86.182010.004    98.5 2007.55
   111.8 2000.45  120.871998.323   141.8 1996.52   188.4 1983.42   198.3 1977.66
   202.6 1976.24   211.7 1971.03   221.7 1966.89   250.81951.183   255.4 1949.95
   265.5  1950.2  267.731951.188   273.2 1954.04   299.1 1953.18   312.6  1954.7
   339.5 1955.15   349.9 1957.02   369.7 1962.38   392.7 1969.91   438.7 1985.44
   494.3 2005.64   510.9 2010.81   533.9 2016.53   543.8 2017.15570.2944 2024.03
#Mann= 5 ,-1 , 0
       0      .1       0   86.18     .06       0  120.87      .1       0
   250.8    .045       0  267.73      .1       0
Bank Sta=250.8,267.73
XS Rating Curve= 0 ,0
Exp/Cntr(USF)=0,0
Exp/Cntr=0.3,0.1

Type RM Length L Ch R = 1 ,38357   ,324.6,321.1,318.4
XS GIS Cut Line= 4
2116325.83279744 319223.333035172116067.35447534319209.065611156
2115933.49386859319130.0919934382115780.91761848319061.069404103
#Sta/Elev= 30
       0 2045.55    18.2 2041.53    74.2 2024.23   86.352019.396    94.5 2017.43
   113.7 2010.23   126.9 2006.18   143.3 2005.51  179.051995.315   205.9 1986.63
   215.8 1982.43   228.9 1978.61     275 1960.89   284.9 1957.79   292.8 1956.47
   304.4 1955.81     323 1952.78   335.5 1953.26   344.4 1952.76  355.211950.348
   365.8 1949.45  374.851950.347   387.2 1956.28   397.6 1959.64   406.2 1964.77
   429.6 1975.06   449.2 1984.69   532.3 2009.12   559.6 2014.26 580.853 2017.18
#Mann= 5 ,-1 , 0
       0      .1       0   86.35     .06       0  179.05      .1       0
  355.21    .045       0  374.85      .1       0
Bank Sta=355.21,374.85
XS Rating Curve= 0 ,0
Exp/Cntr(USF)=0,0
Exp/Cntr=0.3,0.1

Type RM Length L Ch R = 1 ,38036   ,216.5,217.6,219.1
XS GIS Cut Line= 4
 2116323.4109522318877.009165877  2116104.233958318877.009165877
2115931.07202335318891.5402373162115828.14360066318901.227618275
#Sta/Elev= 30
       0 2039.21   31.792030.306    51.8  2023.7    61.6 2018.43    71.5 2014.52
    81.3 2012.64    91.2 2012.13   104.3 2008.03   107.6 2006.48   117.4 1996.55
   120.7 1994.76  160.971981.644   189.6 1974.15   199.4  1968.2     229 1954.41
  243.341949.314   248.8 1947.93   252.9 1948.11  256.221949.314   261.9  1952.4
   289.3 1952.19     308 1956.23   321.2  1960.9   334.9 1969.03   362.2 1982.25
   393.6 1994.61   403.5 1997.32     420 2000.36   469.4 2012.83496.3308 2015.97
#Mann= 5 ,-1 , 0
       0      .1       0   31.79     .06       0  160.97      .1       0
  243.34    .045       0  256.22      .1       0
Bank Sta=243.34,256.22
XS Rating Curve= 0 ,0
Exp/Cntr(USF)=0,0
Exp/Cntr=0.3,0.1