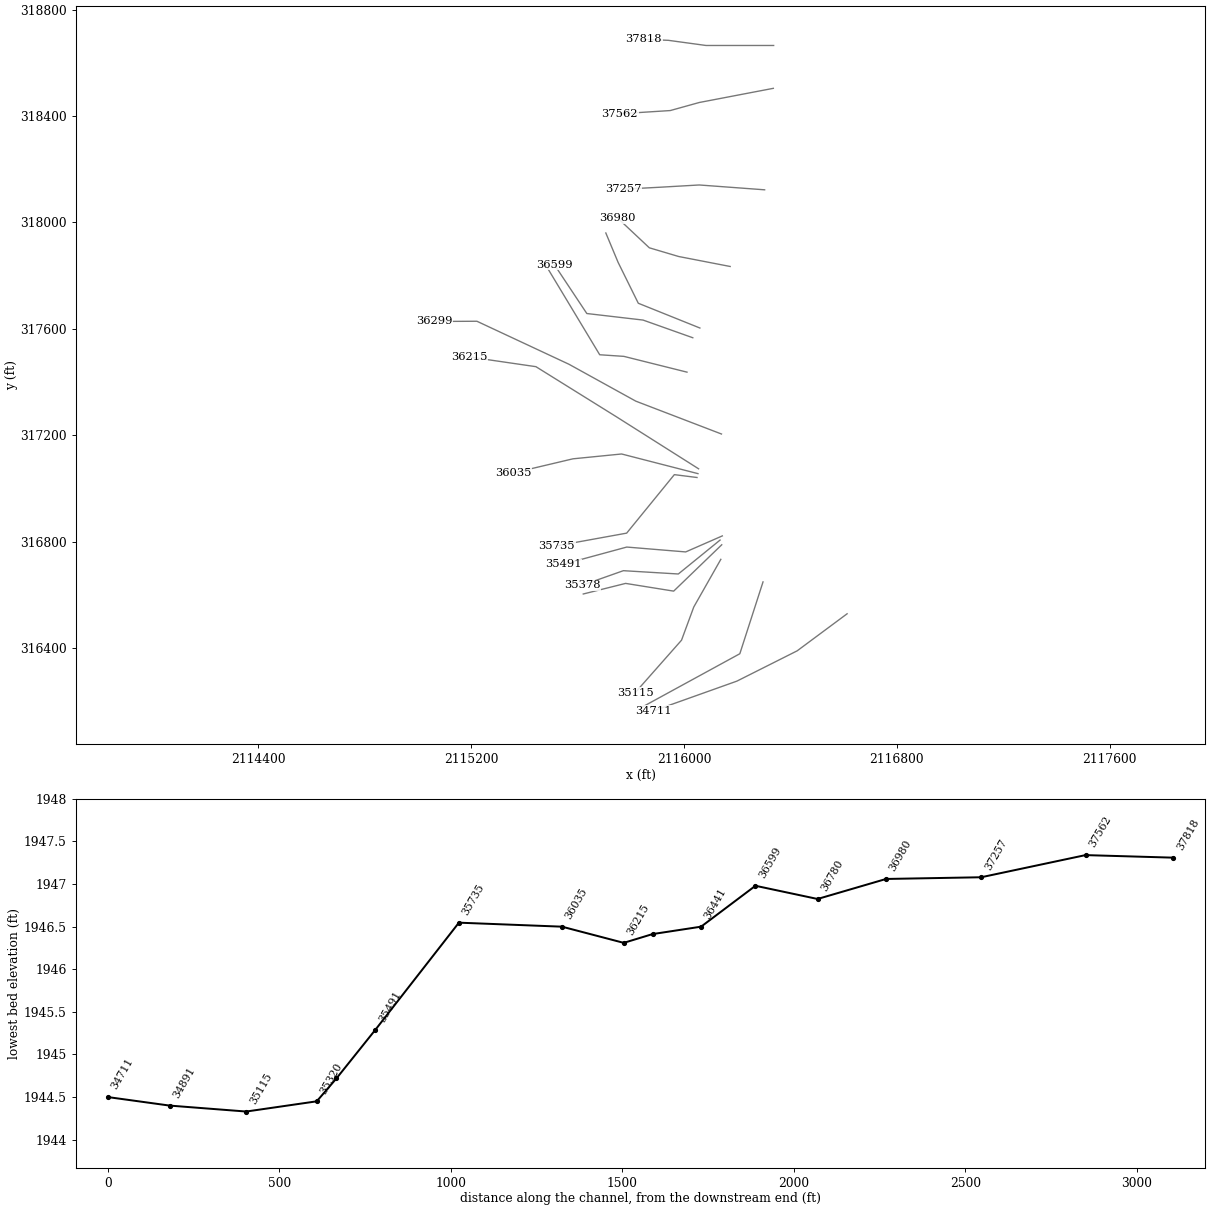
HEC-RAS study MLGNCK.prj: MLGNCK

--- MLGNCK.g01 (geometry) --- (continued)

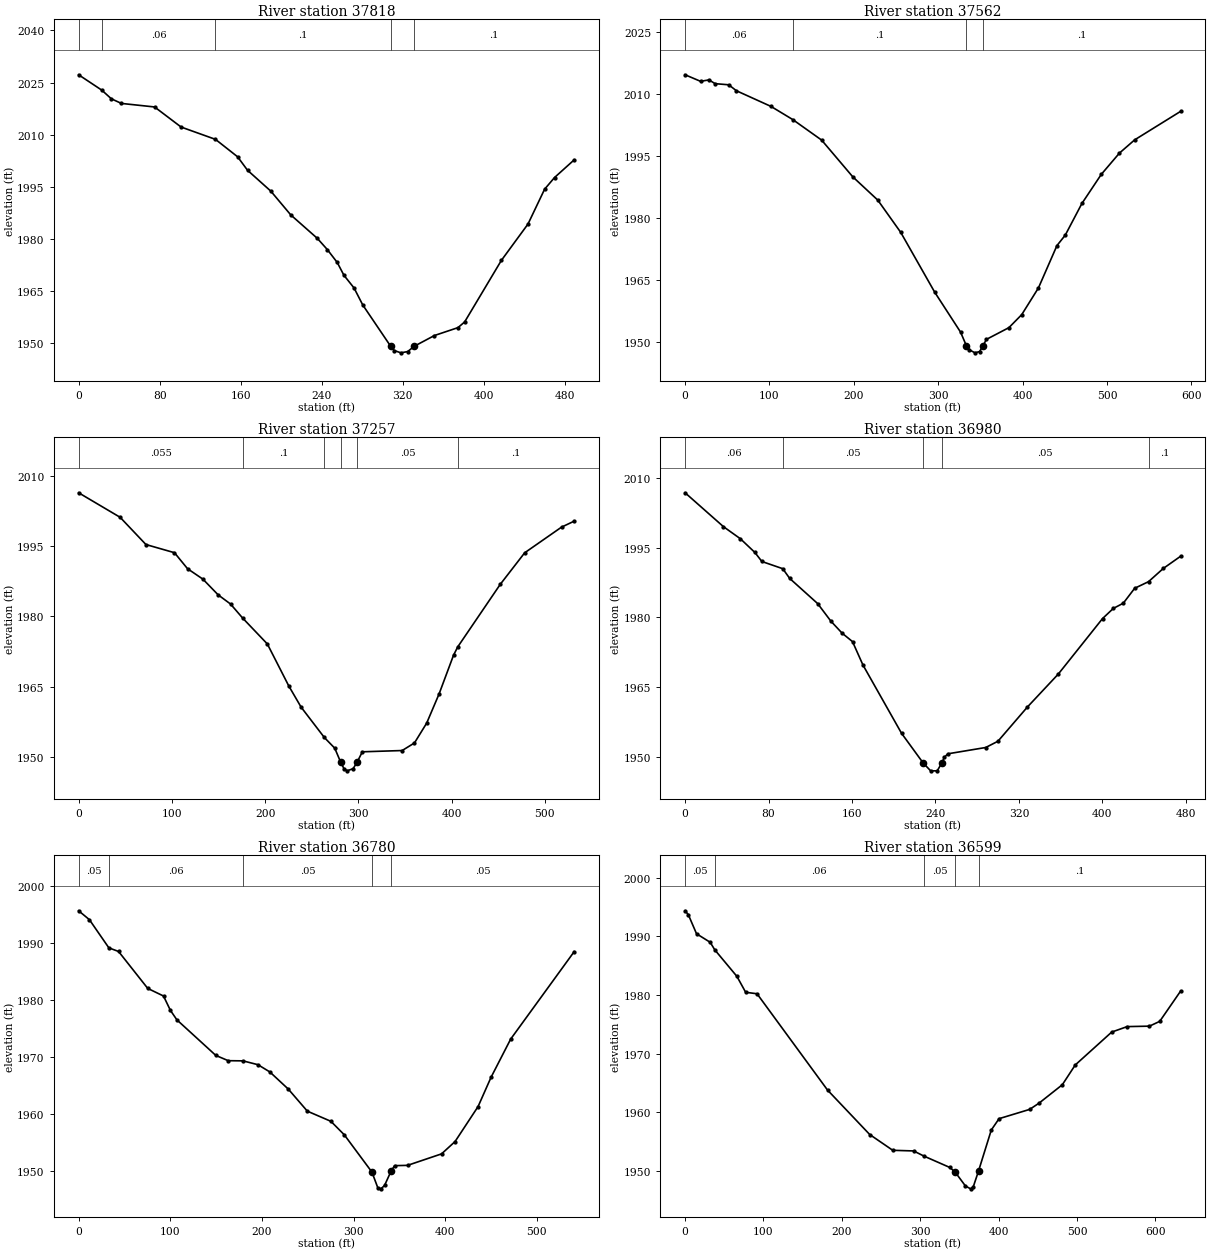
Type RM Length L Ch R = 1 ,37818   ,253.3,256.4,257.9
XS GIS Cut Line= 4
2116336.73110102318665.0977073932116082.43735084318665.097707393
2115940.75940431318684.472469311 2115848.7292852318688.105237171
#Sta/Elev= 30
       0 2027.22   22.862022.804    32.3 2020.32    42.2 2018.99      75 2017.97
   101.2  2012.2  135.132008.662     157 2003.65   166.8 1999.78   189.8 1993.78
   209.5 1986.95   235.7 1980.22   245.6 1976.99   255.4 1973.28     262  1969.6
     272 1965.95   280.6 1961.07  308.191949.193   311.7 1947.97   318.3 1947.31
     325 1947.68  331.381949.193   351.4 1952.29   374.6 1954.55   381.2 1956.18
   417.5 1973.88   443.8 1984.33   460.2 1994.34     470 1997.69489.3921 2002.77
#Mann= 5 ,-1 , 0
       0      .1       0   22.86     .06       0  135.13      .1       0
  308.19    .045       0  331.38      .1       0
Bank Sta=308.19,331.38
XS Rating Curve= 0 ,0
Exp/Cntr(USF)=0,0
Exp/Cntr=0.3,0.1

Type RM Length L Ch R = 1 ,37562   ,304.5,304.2,299
XS GIS Cut Line= 4
 2116335.5201784318504.0449989452116057.00797582318450.764403669
2115948.02494003318420.491338171 2115757.9100887318408.382111972
#Sta/Elev= 30
       0 2014.55    18.3 2012.97    28.3 2013.31    35.6  2012.4    51.7 2012.13
    60.8 2010.69   101.8  2006.9  127.542003.728   161.8 1998.76   198.7 1989.88
   228.3 1984.26   255.5 1976.46   295.7 1962.02   326.4 1952.35  333.231949.091
   336.6  1948.1   343.5 1947.34     349 1947.66  353.011949.091   357.1  1950.6
   383.7 1953.43   398.9 1956.58   418.7 1963.04   440.6 1973.26   450.5  1975.8
   470.2 1983.45   493.2 1990.49   514.7 1995.63   532.7 1998.82587.1724 2005.71
#Mann= 4 ,-1 , 0
       0     .06       0  127.54      .1       0  333.23    .045       0
  353.01      .1       0
Bank Sta=333.23,353.01
XS Rating Curve= 0 ,0
Exp/Cntr(USF)=0,0
Exp/Cntr=0.3,0.1

Type RM Length L Ch R = 1 ,37257   ,278.2,277.3,271.5
XS GIS Cut Line= 4
2116302.82526766318122.6043736742116057.00797582318140.768212973
2115909.27541619318132.2917546332115772.44116014318125.026218914
#Sta/Elev= 30
       0 2006.38    44.5 2001.15    72.2 1995.34   102.8  1993.6   116.8 1990.19
   133.3 1987.96   149.7  1984.6   162.9 1982.66  175.981979.645   202.4 1974.14
   225.4 1965.18   238.6 1960.67  263.521954.193   274.7 1951.91  281.04 1948.93
   284.6 1947.54   287.9 1947.08   294.4 1947.54  298.69 1948.93   304.3 1951.14
     347 1951.41   360.2 1953.03   373.3 1957.26   386.6 1963.48   402.1 1971.74
  406.63 1973.52   452.2 1986.85   478.4 1993.58   517.9 1999.05  531.49 2000.33
#Mann= 6 ,-1 , 0
       0    .055       0  175.98      .1       0  263.52     .05       0
  281.04    .045       0  298.69     .05       0  406.63      .1       0
Bank Sta=281.04,298.69
XS Rating Curve= 0 ,0
Exp/Cntr(USF)=0,0
Exp/Cntr=0.3,0.1

Type RM Length L Ch R = 1 ,36980   ,204.4,199.7,188.9
XS GIS Cut Line= 4
2116173.25654733317834.4047901362115979.50892815317871.943391353
2115869.31496974317904.6383020912115750.64455298318016.043183122
#Sta/Elev= 30
       0 2006.75    36.8 1999.47      53 1996.88    66.9 1993.94    73.6    1992
   93.621990.453   100.3 1988.36   127.1 1982.96   139.7 1979.21   150.5 1976.62
   160.5  1974.8   170.5 1969.78   207.5 1955.12  228.181948.761   235.4 1947.06
   241.7 1947.06  246.15 1948.76   248.5 1949.97     252 1950.72   288.2 1952.07
   299.9 1953.41   328.2 1960.77   357.8 1967.84   400.2 1979.75   410.5 1981.92
   420.1 1983.05     431 1986.25  444.281987.668   458.4  1990.5475.0616 1993.13
#Mann= 5 ,-1 , 0
       0     .06       0   93.62     .05       0  228.18    .045       0
  246.15     .05       0  444.28      .1       0
Bank Sta=228.18,246.15
XS Rating Curve= 0 ,0
Exp/Cntr(USF)=0,0
Exp/Cntr=0.3,0.1

Type RM Length L Ch R = 1 ,36780   ,166.9,181.1,193
XS GIS Cut Line= 4
2116059.42982106317603.118569734  2115827.907555317696.200185991
 2115751.8554756317850.1467841952115705.84041605317960.340742606
#Sta/Elev= 30
       01995.701  11.7641994.135   32.981989.185  43.5881988.546  75.4131982.053
  92.6031980.719 100.1651978.188 107.2371976.524  149.671970.277 163.2211969.351
 179.3371969.319 195.6391968.646 208.6191967.373 228.7951964.352 249.5331960.479
 275.2181958.696 289.8551956.322 320.0191949.766 326.4481946.996 329.8161946.825
 333.7671947.417 341.0861950.013 344.745  1950.9 358.8551950.951 395.9761952.971
 410.7071955.139 435.8031961.285 450.0251966.452 471.3571973.142 540.6561988.517
#Mann= 5 ,-1 , 0
       0     .05       0   32.98     .06       0 179.337     .05       0
 320.019    .045       0 341.086     .05       0
Bank Sta=320.019,341.086
XS Rating Curve= 0 ,0
Exp/Cntr(USF)=0,0
Exp/Cntr=0.3,0.1

Type RM Length L Ch R = 1 ,36599   ,157.6,158.5,161.7
XS GIS Cut Line= 4
2116032.73741244 317566.557938032115845.78633022317632.996164095
2115634.39598147 317657.610087632115512.09279686317841.670325855
#Sta/Elev= 30
       01994.365   4.1461993.691  14.5921990.447  32.0011988.996  37.8271987.717
  66.0851983.189  77.2651980.476  91.7741980.224 181.6861963.818 235.506 1956.24
 264.9471953.548 291.5771953.438 304.7891952.556 337.8191950.617 344.8271949.783
 357.6371947.468 364.243 1946.98 367.5461947.281 374.4121950.042 390.6671957.013
 400.5761958.938 439.5381960.516 451.3941961.565 481.2661964.718 497.7391968.086
 544.2911973.697 563.9861974.626 592.4021974.704 605.525 1975.52 632.2131980.685
#Mann= 5 ,-1 , 0
       0     .05       0  37.827     .06       0 304.789     .05       0
 344.827    .045       0 374.412      .1       0
Bank Sta=344.827,374.412
XS Rating Curve= 0 ,0
Exp/Cntr(USF)=0,0
Exp/Cntr=0.3,0.1

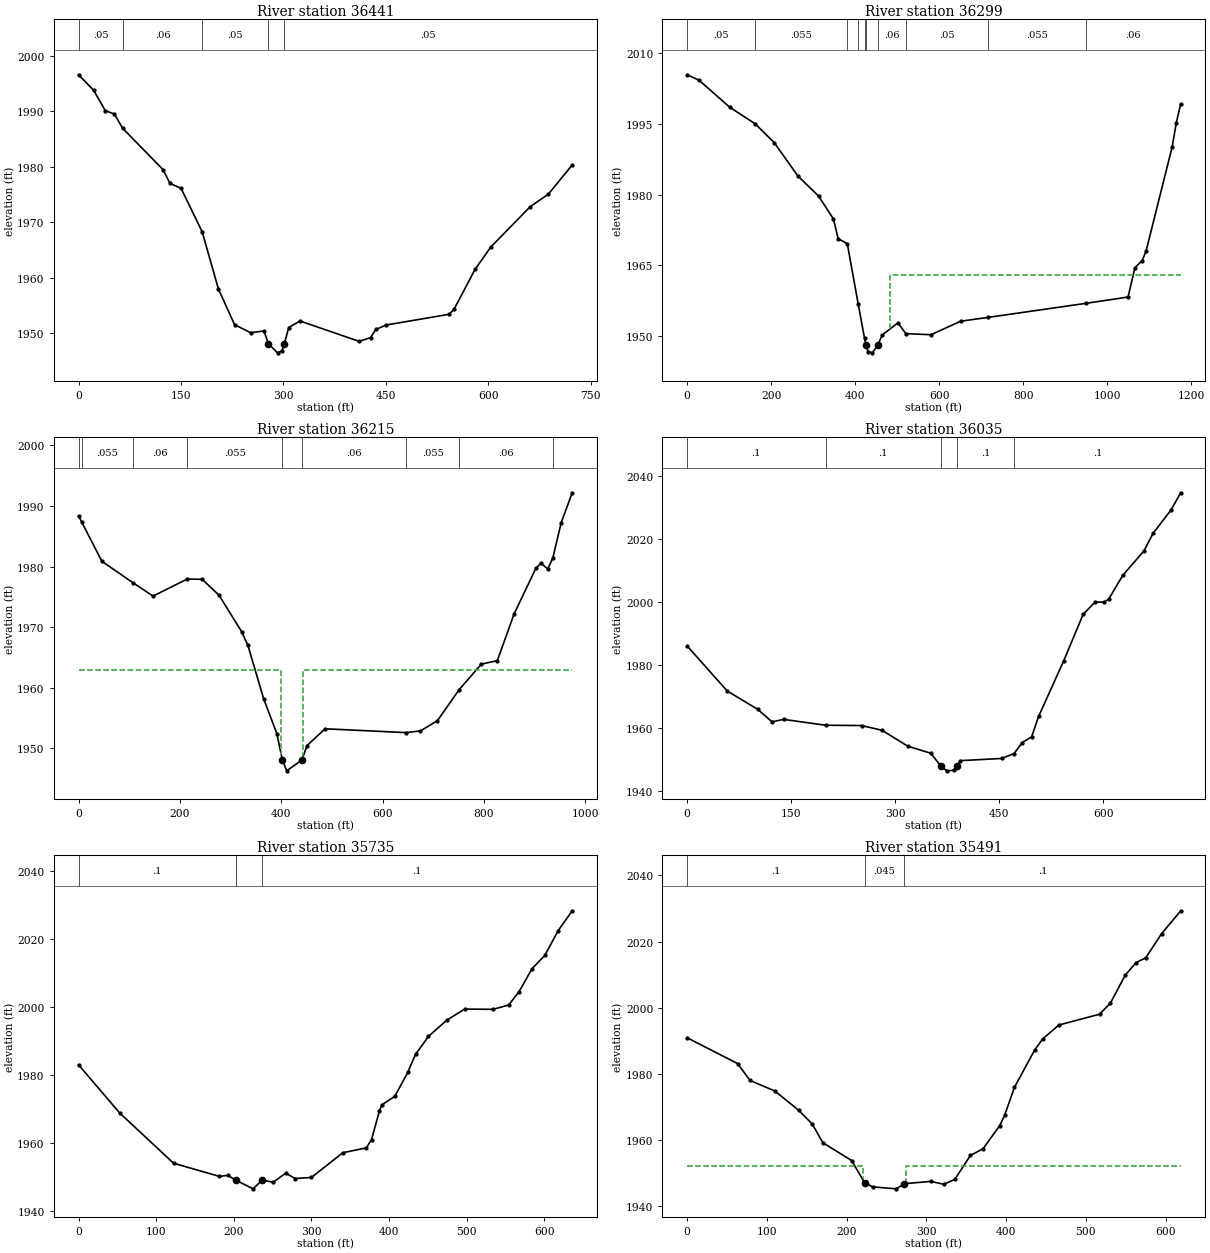
Type RM Length L Ch R = 1 ,36441   ,141.5,141.5,128.2
XS GIS Cut Line= 4
2116010.99291626317437.2221708062115773.65208276317496.557379182
2115682.83288627317502.6119922812115483.03065398317834.404790136
#Sta/Elev= 30
       0 1996.55    22.2 1993.75    39.1  1990.1    52.6 1989.48   64.621986.914
   123.6  1979.5     134    1977   150.2 1976.11  181.181968.239   204.8 1958.01
   228.5 1951.57   251.9 1950.13   271.7 1950.43  277.961948.161   291.4  1946.5
     298 1946.87  301.491948.158   307.8 1951.06   324.3 1952.23   411.1 1948.56
   427.7 1949.25   435.3 1950.71   450.7 1951.51   542.6 1953.44   549.8 1954.31
   580.8 1961.55   603.8 1965.55   661.3 1972.79   688.1 1975.07 722.974 1980.32
#Mann= 5 ,-1 , 0
       0     .05       0   64.62     .06       0  181.18     .05       0
  277.96    .045       0  301.49     .05       0
Bank Sta=277.96,301.49
XS Rating Curve= 0 ,0
Exp/Cntr(USF)=0,0
Exp/Cntr=0.5,0.3

Type RM Length L Ch R = 1 ,36299   ,85.2,84,82.8
XS GIS Cut Line= 5
 2116140.5616366317204.725027784 2115818.4562197317328.239135015
2115567.39871368317466.8281686912115221.24746142317628.554129859
2115060.30825258317627.683474849
#Sta/Elev= 30
       02005.457  28.3062004.319 102.095 1998.53  161.831995.069 207.5091991.041
 263.7291983.971 312.9221979.709 348.265 1974.85 359.5871970.645 381.3181969.591
 407.2521956.787 422.3671949.476  425.28 1948.13  430.711946.668 441.1961946.413
  454.411948.157 464.4381950.209 501.9131952.785 520.6511950.481 580.6111950.262
 651.138 1953.13  716.32 1953.94 948.3721956.9141049.4041958.2641065.8091964.499
1083.0281966.0111092.0561967.9561154.3921990.1521164.2351995.2811174.7541999.309
#Mann= 10 ,-1 , 0
       0     .05       0  161.83    .055       0 381.318    .045       0
 407.252    .055       0 422.367     .06       0  425.28    .045       0
  454.41     .06       0 520.651     .05       0  716.32    .055       0
 948.372     .06       0
#XS Ineff= 2 , 0
                             484            1963
Permanent Ineff=
       F       F
Bank Sta=425.28,454.41
XS Rating Curve= 0 ,0
Exp/Cntr(USF)=0,0
Exp/Cntr=0.5,0.3

Type RM Length L Ch R = 1 ,36215   ,169.2,180.1,192.2
XS GIS Cut Line= 4
2116054.58613058317073.9453848342115744.58993988317270.114849259
2115443.07020753317457.8078553452115193.62014783317494.135533942
#Sta/Elev= 30
       0 1988.36    6.021987.389      46 1980.88   106.81977.374     147 1975.14
   214.8 1977.96     244  1977.9   277.1 1975.29   321.7 1969.29   334.2 1967.01
   365.1 1958.24   391.3 1952.44  402.221948.108   410.8 1946.31  440.781948.109
   450.8 1950.48   486.5 1953.25  645.911952.616   674.7  1952.9   708.1 1954.58
  751.131959.717   794.8 1963.91   826.3 1964.49   859.5 1972.21   902.6 1979.76
   912.5 1980.55   925.8 1979.61  935.871981.426   952.3 1987.24974.0989 1992.18
#Mann= 9 ,-1 , 0
       0      .1       0    6.02    .055       0   106.8     .06       0
   214.8    .055       0  402.22    .045       0  440.78     .06       0
  645.91    .055       0  751.13     .06       0  935.87      .1       0
#XS Ineff= 2 , 0
             400    1963     442            1963
Permanent Ineff=
       F       F
Bank Sta=402.22,440.78
XS Rating Curve= 0 ,0
Exp/Cntr(USF)=0,0
Exp/Cntr=0.5,0.3

Type RM Length L Ch R = 1 ,36035   ,289.5,300.5,307
XS GIS Cut Line= 4
2116052.16428534317055.7815455352115765.17562442 317129.64782535
2115582.32630882317111.4839860512115357.09470151317058.203390775
#Sta/Elev= 30
       0 1986.18      58 1971.84     102 1966.01   122.3 1962.08   139.3 1962.84
  199.591960.986   251.5 1960.88   281.1 1959.38   318.2 1954.31   351.2  1952.1
  365.711948.054   374.3  1946.5   384.2 1946.67  388.971948.053   394.1 1949.74
   453.4 1950.43  471.371952.001   483.1  1955.5   496.6 1957.29   506.7 1963.78
   542.6  1981.3   570.8 1996.16   588.2 2000.16   601.1 2000.04   607.9 2001.08
   628.1 2008.61   658.5 2016.35   671.9 2022.01   697.3 2029.26711.5394 2034.81
#Mann= 5 ,-1 , 0
       0      .1       0  199.59      .1       0  365.71    .045       0
  388.97      .1       0  471.37      .1       0
Bank Sta=365.71,388.97
XS Rating Curve= 0 ,0
Exp/Cntr(USF)=0,0
Exp/Cntr=0.3,0.1

Type RM Length L Ch R = 1 ,35735   ,251.4,243.5,221.3
XS GIS Cut Line= 4
2116048.53151748317041.2504740962115963.39949464317052.001116614
 2115784.1838035 316832.164787262115521.78017782316784.534878676
#Sta/Elev= 30
       01983.052  52.9271968.898 122.4491954.082 181.5941950.203 192.3421950.524
 202.7581949.098 224.9881946.547 236.6211949.156 250.6391948.478 266.9621951.167
  278.951949.589 300.1151949.901 340.5261957.176 370.8781958.599 377.5471961.029
  387.551969.358 390.8851971.256 407.5571973.804 424.2291980.804 434.2321986.135
 450.9041991.402 474.2461996.141 497.587 1999.45 534.2661999.375 554.2722000.652
  567.612004.552 584.2822011.313 600.9542015.273 617.943 2022.51  636.132028.377
#Mann= 3 , 0 , 0
       0      .1       0 202.758    .045       0 236.621      .1       0
Bank Sta=202.758,236.621
XS Rating Curve= 0 ,0
Exp/Cntr(USF)=0,0
Exp/Cntr=0.3,0.1

Type RM Length L Ch R = 1 ,35491   ,110,113.5,103.9
XS GIS Cut Line= 4
2116143.74022789316821.7513936292116006.07362949316761.522256829
2115784.51644769316779.8061019292115546.82646139 316715.27488393
#Sta/Elev= 30
       0 1990.93    63.5 1983.11    78.9 1978.03   110.1 1974.84   139.8 1969.04
   157.1 1964.82   170.2 1959.22   206.4 1953.83   222.6 1947.12   232.8 1945.88
   262.4 1945.29   272.3 1946.85   305.3 1947.53   321.7 1946.68   335.7 1948.15
   355.3  1955.4     371 1957.38   391.8 1964.33   398.2 1967.54   410.5 1975.99
   435.6 1987.15   445.8 1990.57   466.2 1994.78   517.2 1998.04   530.8 2001.42
   549.3 2009.83   562.9 2013.63     575 2015.06     595  2022.4   618.9 2029.28
#Mann= 3 , 0 , 0
       0      .1       0   222.6    .045       0   272.3      .1       0
#XS Ineff= 2 , 0
             220 1952.12     274         1952.12
Permanent Ineff=
       F       F
Bank Sta=222.6,272.3
XS Rating Curve= 0 ,0
Exp/Cntr(USF)=0,0
Exp/Cntr=0.5,0.3

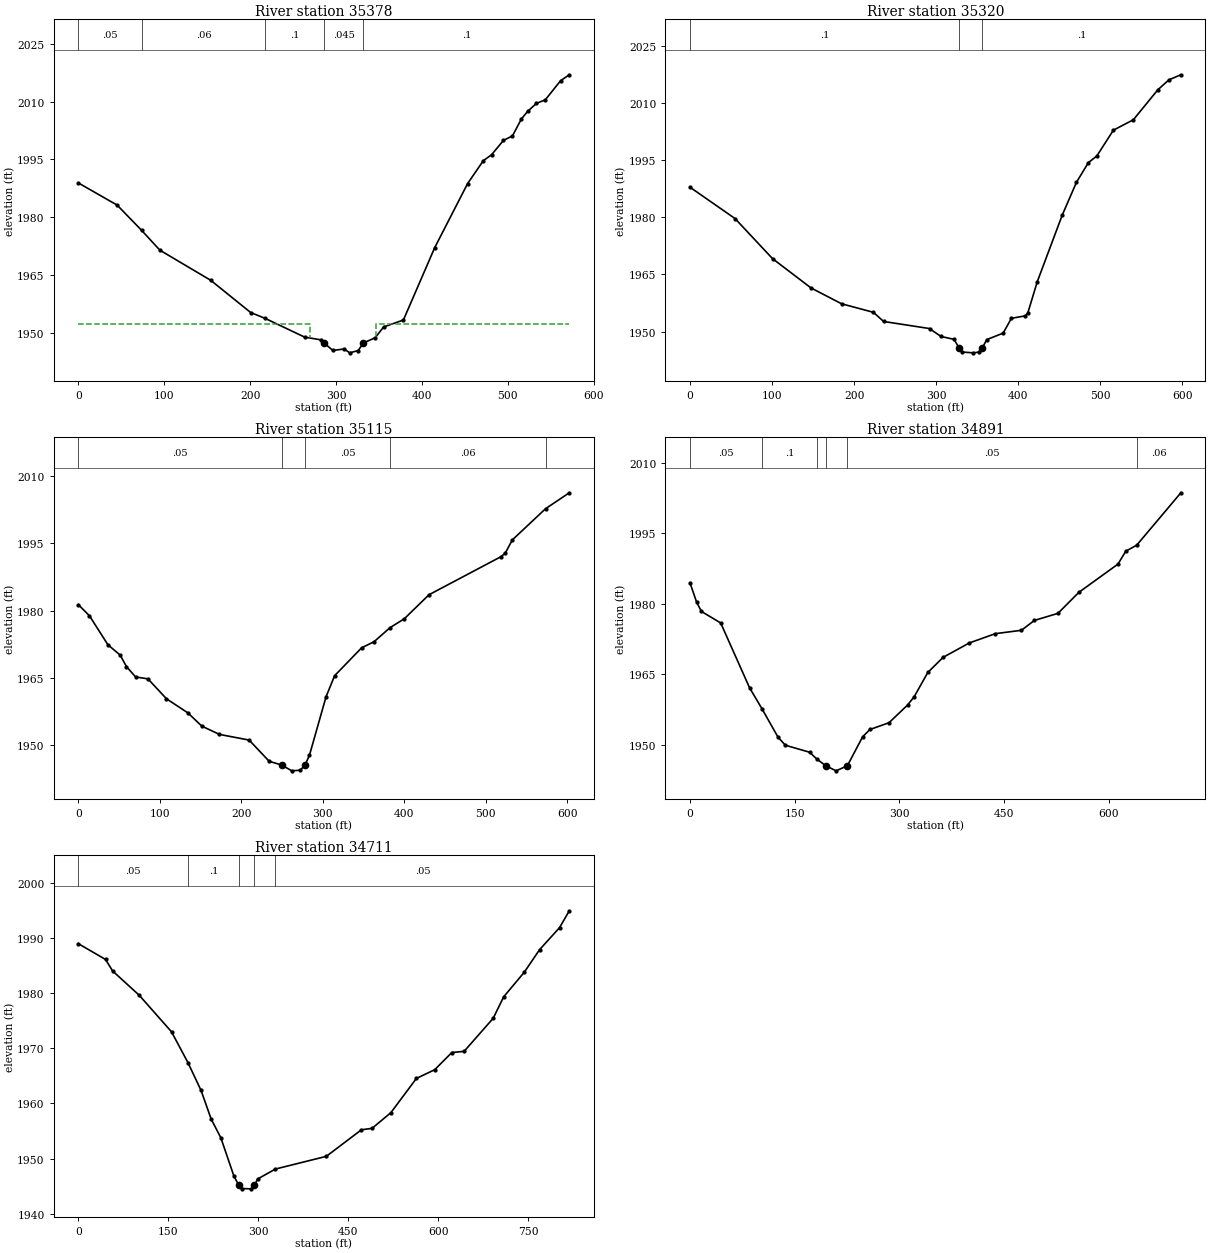
Type RM Length L Ch R = 1 ,35378   ,58.3,57.5,56.5
XS GIS Cut Line= 4
2116135.26475502316806.0790792362115978.38523639316678.592054958
 2115771.8398301316691.0151075682115618.65398741316636.802319047
#Sta/Elev= 30
       01988.856  45.1121983.101  73.7341976.515  94.8721971.389 154.0571963.566
 200.5611955.197 217.3481953.679 263.3631948.809  282.171948.104  286.371947.214
  296.231945.341 309.3771945.718 315.9511944.719 325.8111945.322 331.7741947.276
 345.5321948.639 355.3921951.446 378.3991953.249 414.8771972.061 453.1591988.701
 471.4521994.639 481.0011996.179 494.9221999.916 505.3632001.084 515.8032005.494
 523.1422007.481 533.2042009.522 543.6452010.463  561.422015.431 571.5632016.964
#Mann= 5 ,-1 , 0
       0     .05       0  73.734     .06       0 217.348      .1       0
  286.37    .045       0 331.774      .1       0
#XS Ineff= 2 , 0
             270 1952.12     346         1952.12
Permanent Ineff=
       F       F
Bank Sta=286.37,331.774
XS Rating Curve= 0 ,0
Exp/Cntr(USF)=0,0
Exp/Cntr=0.5,0.3

Type RM Length L Ch R = 1 ,35320   ,187.1,205.6,223.8
XS GIS Cut Line= 4
2116141.58918729316788.4102643292115960.90177689 316614.17597573
2115780.21436649 316643.215023832115621.03736209 316603.42077273
#Sta/Elev= 30
       0  1987.9    54.9 1979.68   100.6 1969.16   147.5 1961.47   184.8 1957.31
   223.5 1955.08   235.9 1952.68   291.9 1950.82   305.7 1948.76   321.8 1947.98
   328.1 1945.65   331.7 1944.66     345 1944.45   351.7 1944.63   355.8 1945.59
   361.6 1947.92   381.6 1949.62   391.6  1953.5   408.2 1954.14   411.5 1954.82
   423.1 1963.08   453.6  1980.6   470.9 1989.19   485.5 1994.37   495.6 1996.06
   515.9 2002.86   540.2 2005.59   570.1 2013.47   583.6 2016.07   598.1 2017.39
#Mann= 3 , 0 , 0
       0      .1       0   328.1    .045       0   355.8      .1       0
Bank Sta=328.1,355.8
XS Rating Curve= 0 ,0
Exp/Cntr(USF)=0,0
Exp/Cntr=0.5,0.3

Type RM Length L Ch R = 1 ,35115   ,221.7,223.5,222.6
XS GIS Cut Line= 4
2116138.13979136 316733.676128642116036.42229128316554.459580893
2115990.40723173316429.7345510432115816.03437446316232.354163998
#Sta/Elev= 30
       0 1981.32    13.6 1978.84    36.2  1972.4    51.3 1970.09    58.9 1967.55
    70.2 1965.23    85.3 1964.81   108.1 1960.37   134.3 1957.24   151.4 1954.29
   173.1 1952.44   209.5 1951.18     234 1946.47   249.41945.622   261.9 1944.33
   272.4 1944.48  278.071945.622   283.5 1947.79   303.9 1960.82   314.4 1965.51
   347.6 1971.73   362.8 1973.07  382.331976.195   399.9 1978.18   430.2 1983.53
   518.8 1992.03   523.8  1992.8   532.5 1995.74  573.222002.683602.3851 2006.23
#Mann= 5 ,-1 , 0
       0     .05       0   249.4    .045       0  278.07     .05       0
  382.33     .06       0  573.22      .1       0
Bank Sta=249.4,278.07
XS Rating Curve= 0 ,0
Exp/Cntr(USF)=0,0
Exp/Cntr=0.3,0.1

Type RM Length L Ch R = 1 ,34891   ,186.8,180.2,165.1
XS GIS Cut Line= 3
2116296.77065456316648.9115452462116209.58422593316378.875801007
2115841.46374948316177.862646102
#Sta/Elev= 30
       0 1984.43     9.5 1980.32    16.4 1978.33      44 1975.88    85.4 1962.07
  103.031957.648   126.2 1951.55   136.7 1949.85   171.6 1948.35  181.741946.901
  194.661945.476   209.3  1944.4  225.441945.476   247.4 1951.66   257.8  1953.2
   285.1 1954.64   311.7  1958.4   321.1 1960.16   340.7 1965.34   362.6 1968.56
     400 1971.61   437.4  1973.6   474.8 1974.32   493.4 1976.42   527.1 1977.92
     557 1982.39   613.1 1988.41   624.3 1991.16   639.91992.428703.1888 2003.59
#Mann= 6 ,-1 , 0
       0     .05       0  103.03      .1       0  181.74     .05       0
  194.66    .045       0  225.44     .05       0   639.9     .06       0
Bank Sta=194.66,225.44
XS Rating Curve= 0 ,0
Exp/Cntr(USF)=0,0
Exp/Cntr=0.3,0.1

Type RM Length L Ch R = 1 ,34711   ,243.4,236,219.9
XS GIS Cut Line= 4
2116612.82145836316529.0302058752116425.12845227316389.774104586
2116198.68592235316275.9473783152115886.26788641316164.542497283
#Sta/Elev= 30
       0 1988.95    45.3 1986.09    57.2 1983.99   101.4 1979.61   155.3 1972.98
  182.821967.366   204.6 1962.34   221.5 1957.14   237.6 1953.76   259.5 1946.78
  267.691945.121   273.3 1944.55     288  1944.5  293.621945.121     299 1946.29
  328.671948.092   413.5 1950.39   472.1 1955.21   489.8 1955.47   521.2 1958.31
   563.8 1964.52   594.3  1966.1   622.9 1969.22   643.4 1969.43   691.9 1975.43
   709.3 1979.31   743.6 1983.76   769.2 1987.86   802.6 1991.87818.8397 1994.92
#Mann= 5 ,-1 , 0
       0     .05       0  182.82      .1       0  267.69    .045       0
  293.62      .1       0  328.67     .05       0
Bank Sta=267.69,293.62
XS Rating Curve= 0 ,0
Exp/Cntr(USF)=0,0
Exp/Cntr=0.3,0.1