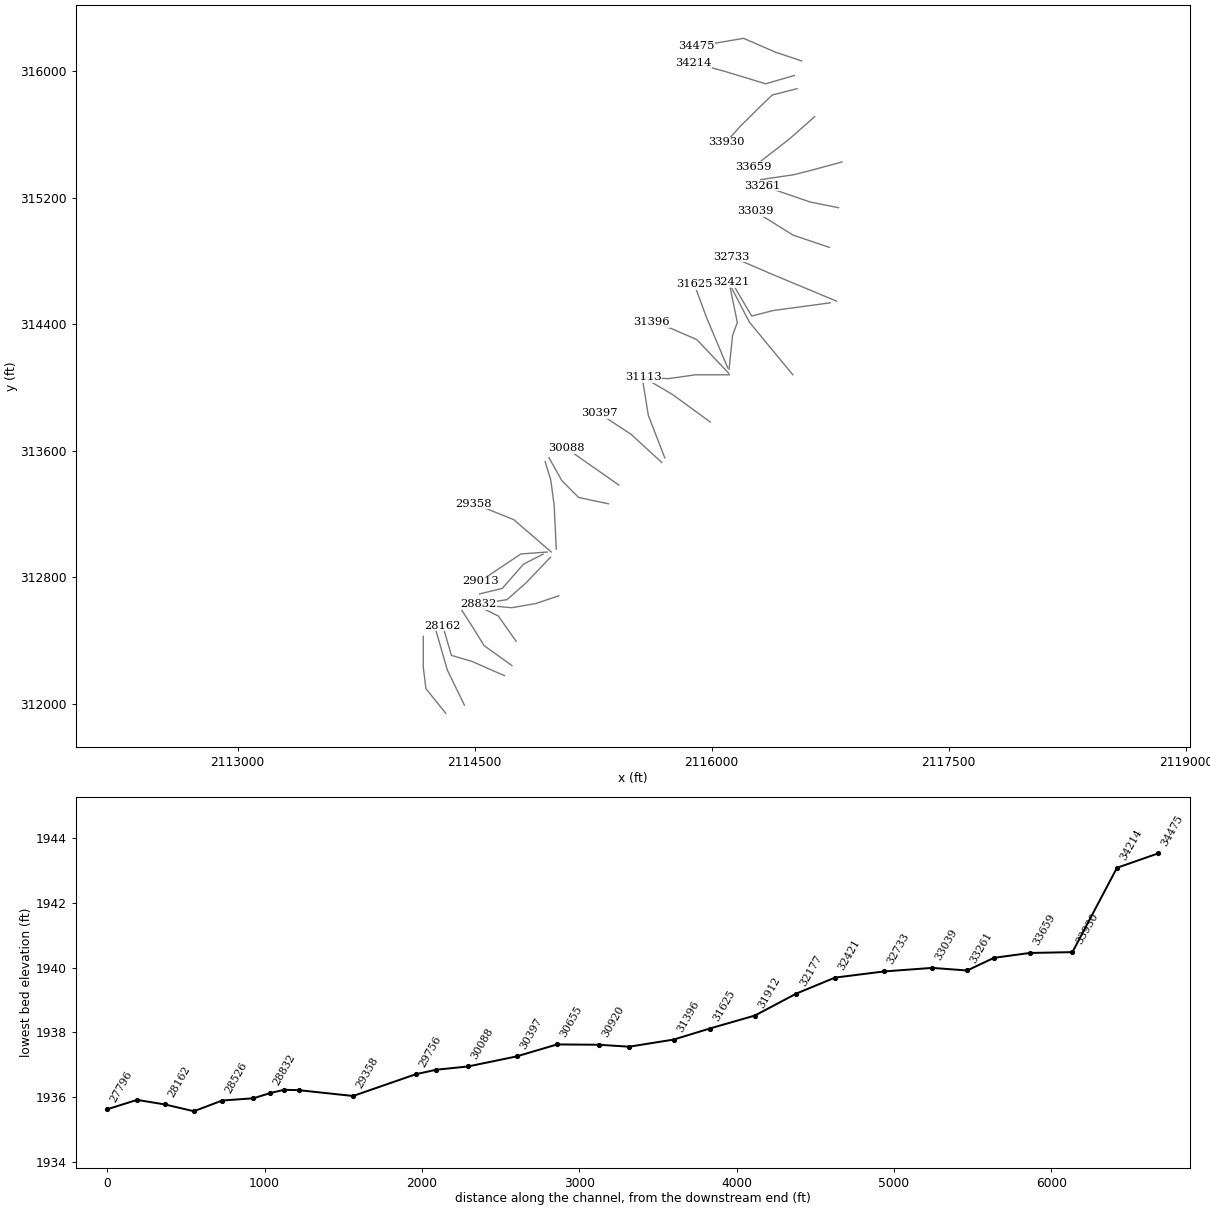
HEC-RAS study MLGNCK.prj: MLGNCK

--- MLGNCK.g01 (geometry) --- (continued)

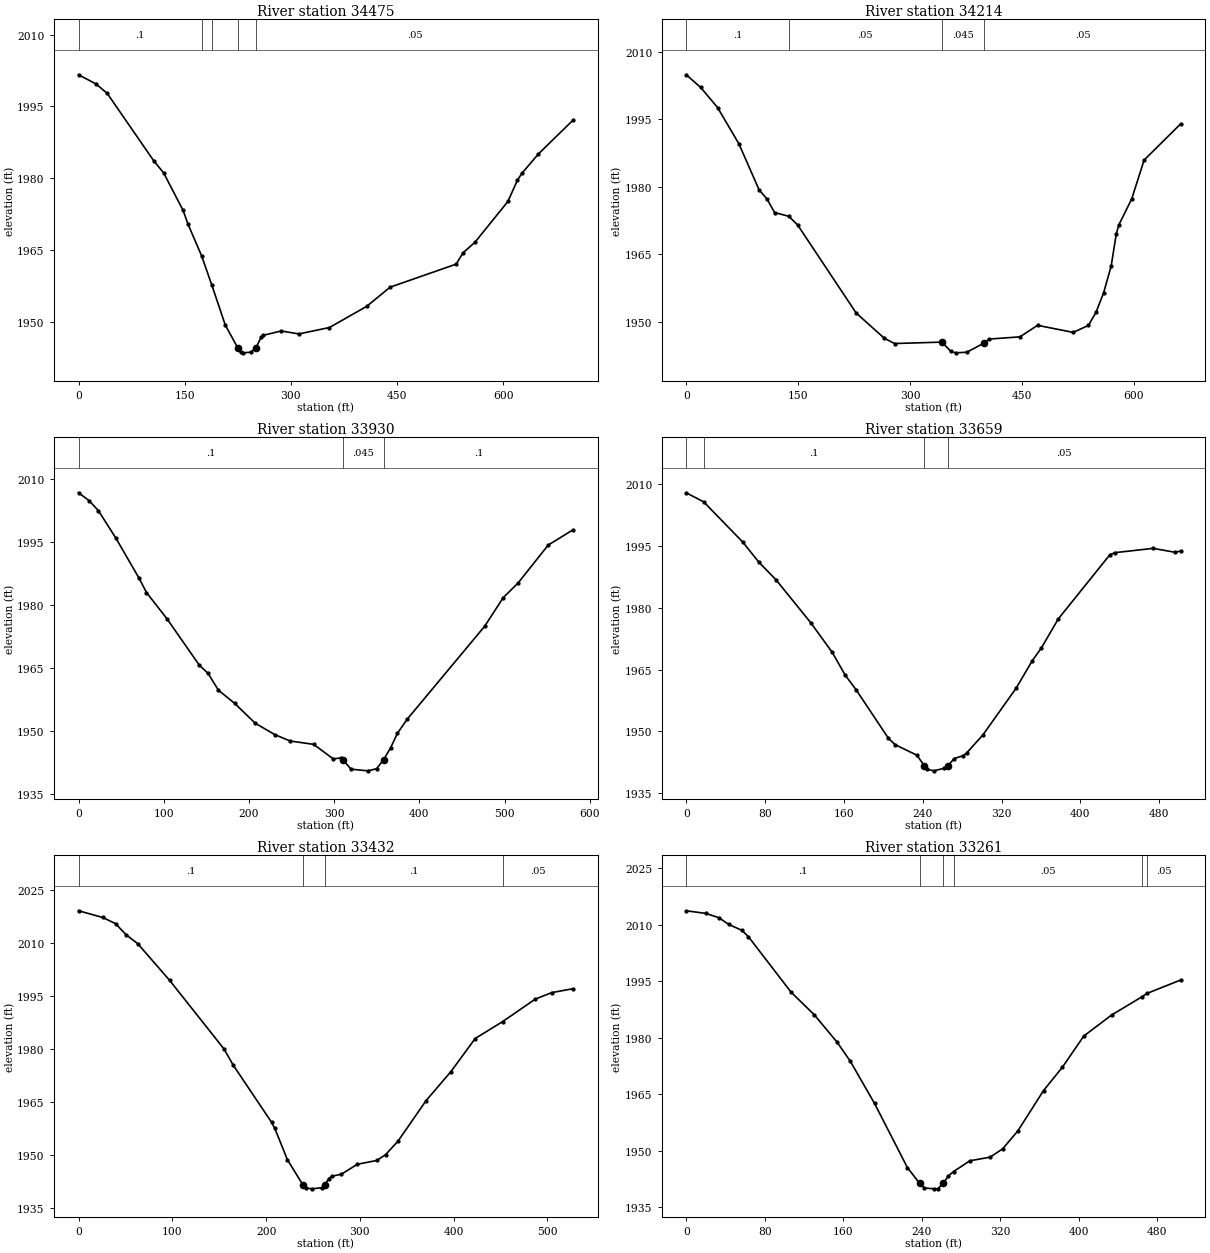
Type RM Length L Ch R = 1 ,34475   ,245.2,261.3,265.9
XS GIS Cut Line= 4
2116569.22824404316066.4577650712116405.75369035316120.949282966
2116202.31869021 316209.346634222115902.00988047316158.487884184
#Sta/Elev= 30
       0 2001.61    24.6  1999.7    40.5 1997.72   106.2 1983.64   120.1 1981.14
   147.7 1973.28   154.6 1970.42  173.881963.778   188.11957.757   207.3 1949.34
  224.881944.569   229.1 1943.63   232.3 1943.52   243.5 1943.66   250.71944.568
   257.8 1946.73   261.3 1947.19   286.4 1948.09   311.4 1947.47   354.5 1948.81
     407 1953.22   440.3 1957.24   533.5 1962.05   543.5 1964.45   560.1 1966.61
   606.7 1975.15     620 1979.54   626.5 1981.03   649.9 1985.08698.7128 1992.13
#Mann= 5 ,-1 , 0
       0      .1       0  173.88      .1       0   188.1     .05       0
  224.88    .045       0   250.7     .05       0
Bank Sta=224.88,250.7
XS Rating Curve= 0 ,0
Exp/Cntr(USF)=0,0
Exp/Cntr=0.3,0.1

Type RM Length L Ch R = 1 ,34214   ,243.2,283.2,302
XS GIS Cut Line= 4
2116523.21318449315974.4276459582116341.55118611315921.829991219
2116076.38273774316002.2788662152115886.26788641316053.137616252
#Sta/Elev= 30
       02004.906  19.4292002.079   42.041997.608  70.6621989.541  97.6631979.321
 108.2341977.283 118.4811974.271 137.3931973.446 149.2211971.546 227.9251951.917
 265.6391946.313 279.3531945.146   342.91945.463  354.781943.405 361.6371943.076
 376.3211943.218  399.351945.251 406.2071946.142 447.3491946.626 471.1061949.191
 518.8481947.625 539.2251949.165 549.4131952.063 559.6021956.387 569.7911962.363
 576.5831969.467 579.9791971.491 597.333  1977.3 613.9411985.938 663.0271993.999
#Mann= 4 ,-1 , 0
       0      .1       0 137.393     .05       0   342.9    .045       0
  399.35     .05       0
Bank Sta=342.9,399.35
XS Rating Curve= 0 ,0
Exp/Cntr(USF)=0,0
Exp/Cntr=0.3,0.1

Type RM Length L Ch R = 1 ,33930   ,272.3,271.7,270.8
XS GIS Cut Line= 5
2116540.16610116315890.873985184 2116383.0512492315850.536819803
 2116305.2471129315775.8363362932116179.31116043315651.111306442
2116090.91380918 315551.81565161
#Sta/Elev= 30
       02006.761  12.3232004.892  23.2212002.508  43.5441996.028  70.6421986.525
  79.7041982.985 103.9621976.662 141.6951965.666 151.9361963.713 164.2081959.679
 183.1571956.566 207.1991951.845 230.2821949.102 248.4751947.582 275.8511946.789
 298.9391943.317 308.1741943.567 310.4131943.084 319.7381940.874 339.4471940.476
 349.7321940.979 358.0071943.144 366.3621946.032 374.2461949.444 385.8461952.834
 476.468 1974.91 498.4311981.784 515.7351985.239 551.1421994.294 580.2581997.928
#Mann= 3 , 0 , 0
       0      .1       0 310.413    .045       0 358.007      .1       0
Bank Sta=310.413,358.007
XS Rating Curve= 0 ,0
Exp/Cntr(USF)=0,0
Exp/Cntr=0.3,0.1

Type RM Length L Ch R = 1 ,33659   ,231.1,226.8,221.1
XS GIS Cut Line= 3
 2116651.5709822315714.0792826772116492.94011899315573.612258768
2116264.07574383315395.606633642
#Sta/Elev= 30
       0 2007.83   17.732005.621    57.3  1995.9    73.5 1991.07    91.2 1986.71
   126.3 1976.36   148.2 1969.15   161.3 1963.65   172.4 1960.09   205.1 1948.37
     212 1946.79     234 1944.25  241.62  1941.7     244 1940.86   251.2 1940.45
   262.1 1941.09  265.62  1941.7     272 1943.44   280.8  1944.1   284.5 1944.75
   301.1 1949.16   334.9 1960.52   351.1 1967.11   360.3 1970.19   377.6 1977.27
   429.9  1992.8   435.1 1993.32   473.8 1994.36   495.9 1993.42501.8233  1993.7
#Mann= 4 ,-1 , 0
       0     .05       0   17.73      .1       0  241.62    .045       0
  265.62     .05       0
Bank Sta=241.62,265.62
XS Rating Curve= 0 ,0
Exp/Cntr(USF)=0,0
Exp/Cntr=0.3,0.1

Type RM Length L Ch R = 1 ,33432   ,177.5,170.6,163.7
XS GIS Cut Line= 4
2116824.73291684315427.0906217592116632.19622028315375.020949103
2116517.15857139315345.9588062252116310.09080338315315.685740728
#Sta/Elev= 30
       0 2019.08    25.8 2017.18    39.4 2015.44    50.7 2012.29    63.2 2009.73
    97.2 1999.34     155 1979.97   165.1 1975.28   205.9 1959.13   209.3 1957.42
   222.8 1948.52  239.131941.488   243.1 1940.51   249.1  1940.3     260 1940.65
  262.981941.488   266.8 1943.22   270.2 1943.87   280.4 1944.45   297.3 1947.26
   318.1 1948.34   327.5 1949.99   340.8 1953.85   370.6 1965.27   397.2 1973.54
     423 1982.89  452.19 1987.66   487.2 1994.07   504.6 1995.89527.3742    1997
#Mann= 4 ,-1 , 0
       0      .1       0  239.13    .045       0  262.98      .1       0
  452.19     .05       0
Bank Sta=239.13,262.98
XS Rating Curve= 0 ,0
Exp/Cntr(USF)=0,0
Exp/Cntr=0.3,0.1

Type RM Length L Ch R = 1 ,33261   ,225.4,222.6,220.2
XS GIS Cut Line= 3
2116802.93630968315137.6801156012116622.50883932315174.007794199
2116319.77818434315278.147139511
#Sta/Elev= 30
       0 2013.75    19.9 2013.05    33.3 2011.91    43.3 2010.13    56.7 2008.56
    63.4 2006.87   106.9 1992.13   130.6 1986.12   153.8 1978.86   167.2 1973.83
     192 1962.58   225.5 1945.56  237.911941.389   242.7 1940.13   253.1 1939.91
   256.7 1939.96  262.111941.389   267.2 1943.33  272.561944.503   289.2 1947.36
   309.9 1948.33   322.7 1950.54   338.3 1955.35   364.3    1966   383.6 1972.22
   405.4 1980.49   433.7 1986.06  464.55 1990.89  469.911991.812504.1902 1995.37
#Mann= 6 ,-1 , 0
       0      .1       0  237.91    .045       0  262.11      .1       0
  272.56     .05       0  464.55      .1       0  469.91     .05       0
Bank Sta=237.91,262.11
XS Rating Curve= 0 ,0
Exp/Cntr(USF)=0,0
Exp/Cntr=0.3,0.1

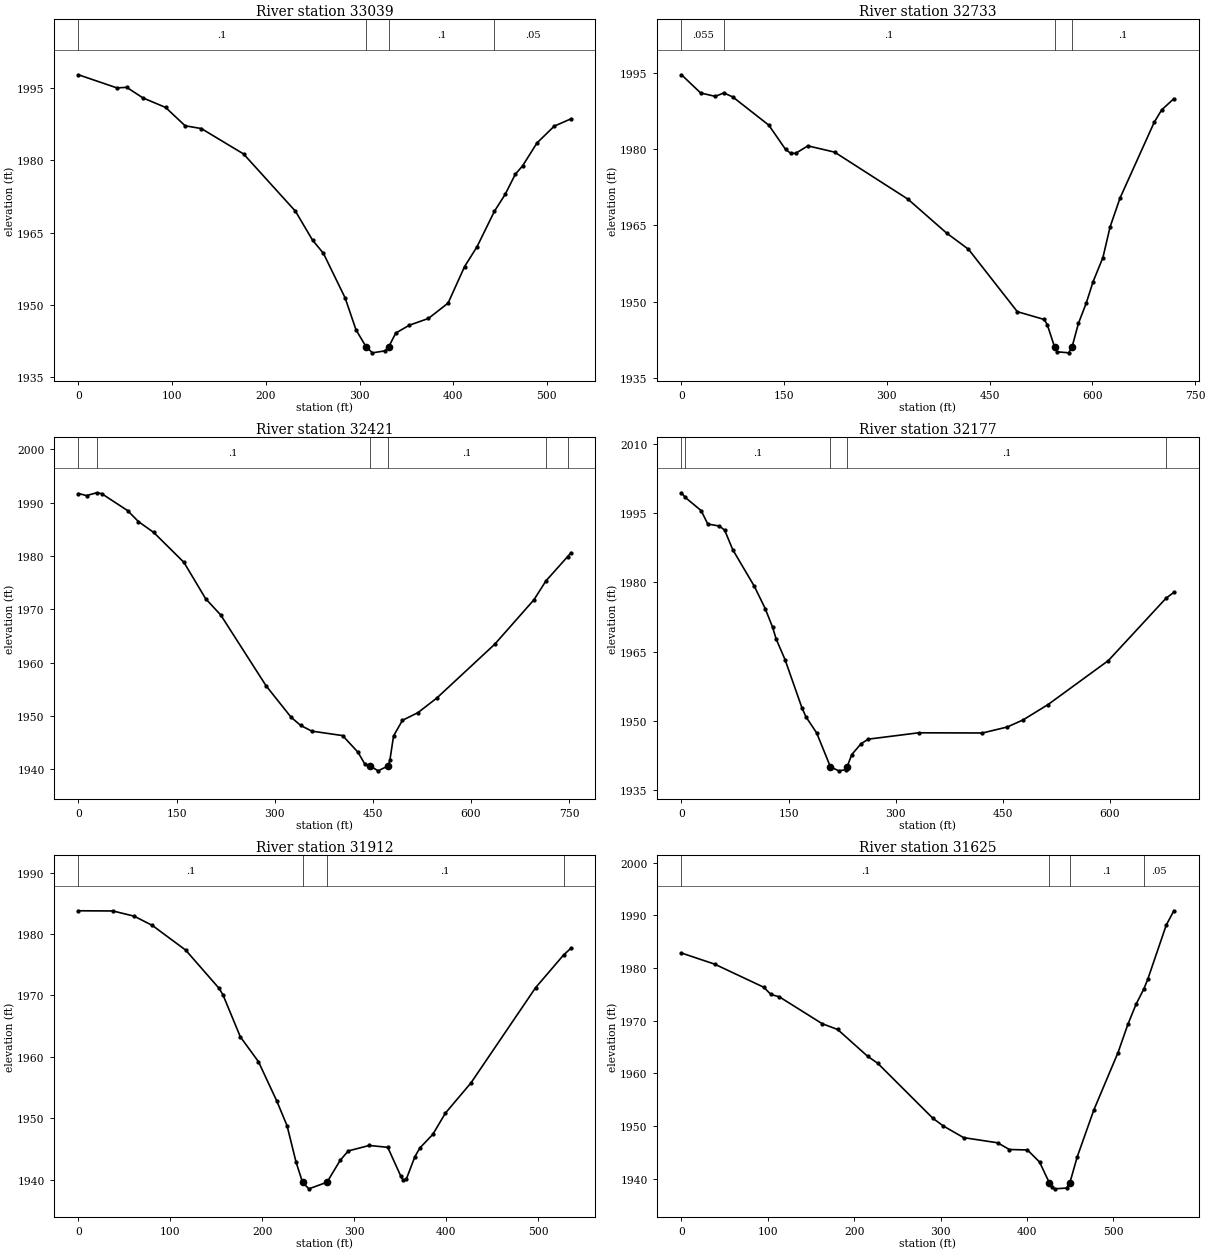
Type RM Length L Ch R = 1 ,33039   ,302.6,306,306.9
XS GIS Cut Line= 3
2116743.60110131 314887.019133282116514.73672615314964.518180954
2116273.76312478315114.672585823
#Sta/Elev= 30
       0  1997.8    41.1 1995.07    51.5 1995.19    68.8 1992.99      93 1991.01
   113.8  1987.2   131.1 1986.62   176.2 1981.34   231.6 1969.43   249.8 1963.43
   261.4 1960.69   284.6 1951.41   296.2 1944.78  306.911941.259   313.8 1939.99
   327.1  1940.4  331.191941.258   338.6 1944.09     353 1945.72   373.5 1947.14
   394.5 1950.33   412.1 1957.92   425.5 1962.09  443.971969.427   455.4 1972.93
   466.2  1977.1     474 1978.86   489.4 1983.63   507.8 1987.12 525.557 1988.63
#Mann= 4 ,-1 , 0
       0      .1       0  306.91    .045       0  331.19      .1       0
  443.97     .05       0
Bank Sta=306.91,331.19
XS Rating Curve= 0 ,0
Exp/Cntr(USF)=0,0
Exp/Cntr=0.3,0.1

Type RM Length L Ch R = 1 ,32733   ,305,311.7,321
XS GIS Cut Line= 3
2116789.61616087314546.749877086  2116371.847857314721.122734353
2116127.24148778314826.473002285
#Sta/Elev= 30
       0 1994.73      28 1991.14    49.4 1990.47   61.771991.146    74.9 1990.36
   127.6 1984.78     152    1980   159.6 1979.24   166.7 1979.23   184.5 1980.71
   223.6 1979.47   330.7 1970.19   387.1 1963.51   419.1 1960.31   490.4    1948
   529.7 1946.46   534.2 1945.41  544.851941.013   548.5 1940.09   565.4 1939.88
  570.261941.016   579.7 1945.71     591 1949.67   601.1 1953.94   615.4 1958.68
   625.9 1964.74   640.4 1970.42   690.4 1985.39   701.2 1987.81719.0275 1990.02
#Mann= 4 ,-1 , 0
       0    .055       0   61.77      .1       0  544.85    .045       0
  570.26      .1       0
Bank Sta=544.85,570.26
XS Rating Curve= 0 ,0
Exp/Cntr(USF)=0,0
Exp/Cntr=0.3,0.1

Type RM Length L Ch R = 1 ,32421   ,269,244.3,245
XS GIS Cut Line= 4
2116749.65571441314535.851573507 2116390.0116963314487.414668711
2116253.17744025314452.2979127332116127.24148778314666.631216457
#Sta/Elev= 30
       0  1991.7    12.3 1991.31   27.671991.836    35.4 1991.68    75.2 1988.49
    91.7 1986.43   114.9 1984.41   161.2 1978.79   194.4 1971.97   217.5 1968.91
   286.9 1955.62     325 1949.75   339.6 1948.21   356.6 1947.14   403.8  1946.3
   427.4 1943.17   437.7 1940.97  445.571940.634     458 1939.69  473.771940.632
   476.2 1941.79   481.7 1946.24   495.3 1949.17   518.9  1950.6   547.6 1953.32
   636.4 1963.44   696.3 1971.77  714.611975.309  747.591979.838752.7529 1980.58
#Mann= 6 ,-1 , 0
       0    .055       0   27.67      .1       0  445.57    .045       0
  473.77      .1       0  714.61     .05       0  747.59      .1       0
Bank Sta=445.57,473.77
XS Rating Curve= 0 ,0
Exp/Cntr(USF)=0,0
Exp/Cntr=0.3,0.1

Type RM Length L Ch R = 1 ,32177   ,286,264.9,265.9
XS GIS Cut Line= 3
2116513.52580353314080.5446684222116238.64636881314413.548388896
2116119.97595206314642.412764059
#Sta/Elev= 30
       0 1999.43    4.941998.469    27.5 1995.57    36.8 1992.66    53.2 1992.22
    60.5 1991.32    71.8  1987.1   102.1 1979.15   117.2 1974.36   127.5 1970.34
   132.6 1967.75     145 1963.29   168.7 1952.85   174.3  1950.9   189.3 1947.41
  208.53 1940.08   220.2  1939.2     230 1939.45  231.981940.081   238.5 1942.73
   251.3 1945.04   261.5 1946.06   332.1 1947.44   421.5  1947.4   456.1 1948.69
   478.3 1950.22   513.4 1953.56   597.8 1963.08  678.551976.586689.6002 1977.86
#Mann= 5 ,-1 , 0
       0    .055       0    4.94      .1       0  208.53    .045       0
  231.98      .1       0  678.55     .05       0
Bank Sta=208.53,231.98
XS Rating Curve= 0 ,0
Exp/Cntr(USF)=0,0
Exp/Cntr=0.3,0.1

Type RM Length L Ch R = 1 ,31912   ,275.5,286.7,291.6
XS GIS Cut Line= 4
 2116110.2885711314115.6614243992116132.08517826314328.783805503
2116162.35824375314412.3374662762116115.13226158314639.990918819
#Sta/Elev= 30
       0 1983.78    37.5 1983.75    60.6  1982.9    80.4 1981.39   116.6 1977.38
   152.9 1971.16   157.2 1970.09     176 1963.28   195.8 1959.21   215.7 1952.82
   226.9 1948.79   236.6 1942.91   243.71939.591   250.6 1938.52  270.311939.593
   284.7 1943.17   293.5 1944.69   316.3 1945.58   336.4 1945.28   350.6 1940.59
   353.2 1939.92   356.5 1940.05   365.9 1943.75   371.5  1945.2   385.4 1947.38
   399.2 1950.86     427 1955.78   497.2 1971.26   527.61976.573535.6032 1977.68
#Mann= 4 ,-1 , 0
       0      .1       0   243.7    .045       0  270.31      .1       0
   527.6     .05       0
Bank Sta=243.7,270.31
XS Rating Curve= 0 ,0
Exp/Cntr(USF)=0,0
Exp/Cntr=0.3,0.1

Type RM Length L Ch R = 1 ,31625   ,216.3,228.8,235.2
XS GIS Cut Line= 3
2116101.81211276314124.1378827382115966.18877933314446.243299634
2115889.90065427314653.311067638
#Sta/Elev= 30
       0 1982.84    38.4 1980.73    95.4 1976.34   103.5 1974.98   113.2 1974.54
   162.9 1969.44   180.8 1968.34   215.5 1963.26   227.1 1961.95   291.1  1951.5
   303.2 1950.04   326.7 1947.83   366.1 1946.85   379.6 1945.58   400.6 1945.49
   414.6 1943.21  425.811939.311   428.5 1938.46     432 1938.12     446 1938.27
  449.791939.312   458.1 1944.12   477.5 1953.09   505.5 1963.97   516.9 1969.32
   526.4 1973.14  535.431976.049   539.9 1977.86   561.4 1988.17570.1672 1990.85
#Mann= 4 ,-1 , 0
       0      .1       0  425.81    .045       0  449.79      .1       0
  535.43     .05       0
Bank Sta=425.81,449.79
XS Rating Curve= 0 ,0
Exp/Cntr(USF)=0,0
Exp/Cntr=0.3,0.1

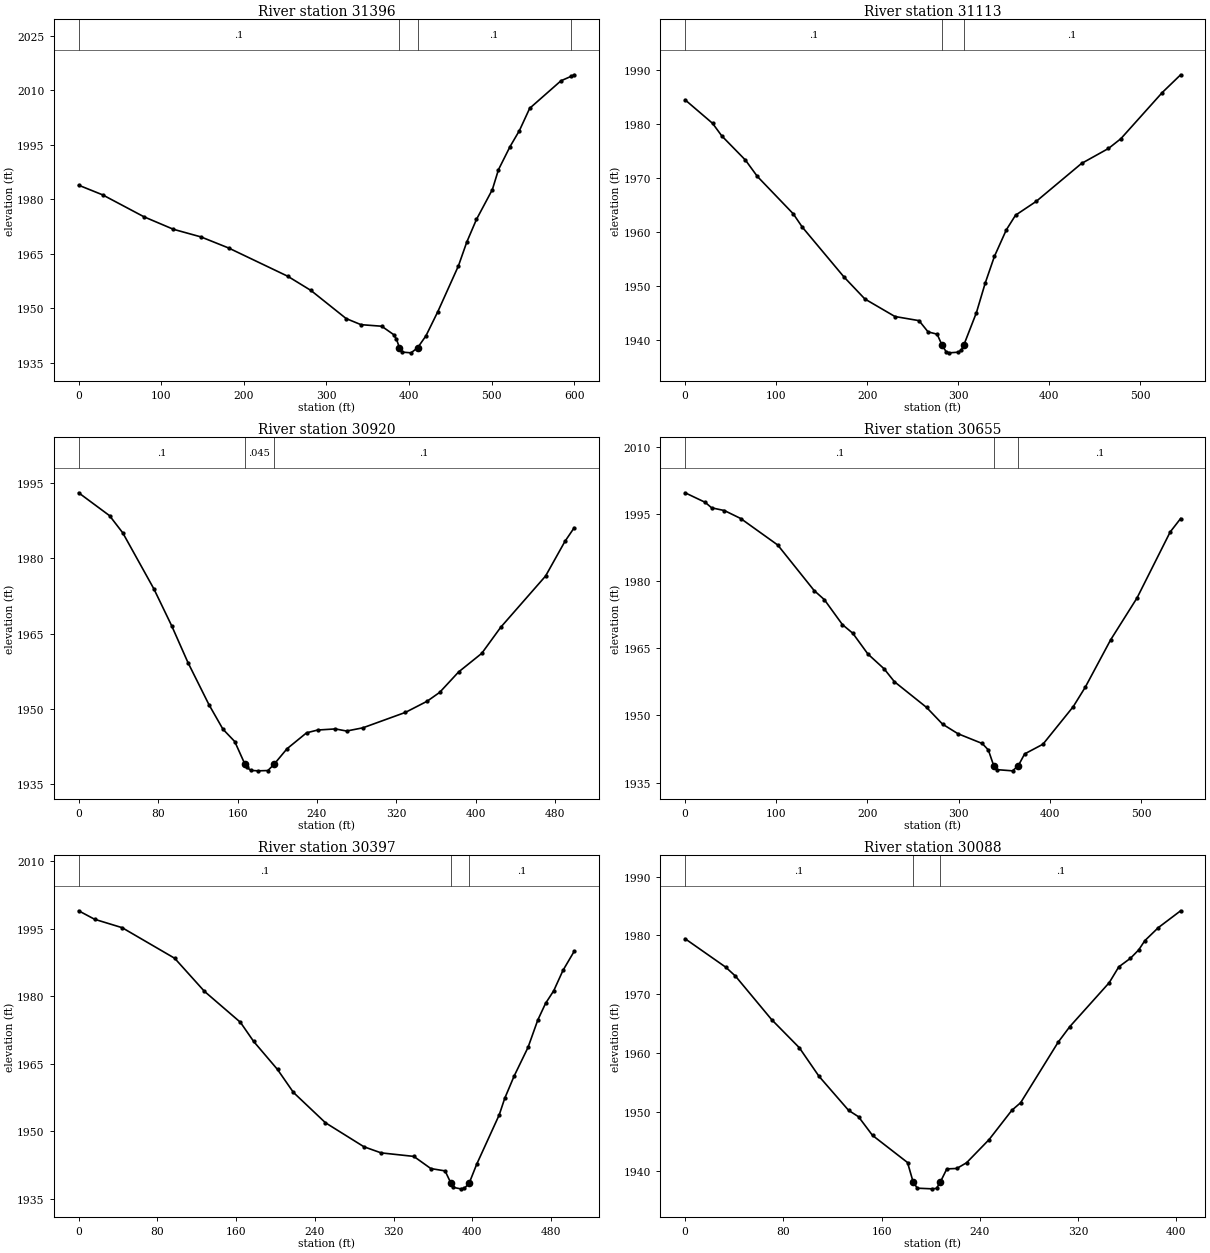
Type RM Length L Ch R = 1 ,31396   ,275.7,283.1,287.9
XS GIS Cut Line= 4
2116107.86672586314090.2320493812115905.64264833314303.354430485
2115747.01178512 314372.377019822115619.86491003314412.337466276
#Sta/Elev= 30
       0 1983.89      29 1981.24    79.4 1975.17   114.8 1971.76   148.2 1969.66
   181.5 1966.63   253.1 1958.86   281.3 1954.94     324  1947.2   341.9 1945.53
     367  1945.1   381.3 1942.82   384.9 1941.53  388.541939.148     392 1937.98
   402.5 1937.78  410.381939.149   420.6 1942.46     435 1949.13   459.9 1961.69
     470 1968.23   481.7 1974.46     501 1982.68   508.4 1988.16   522.3 1994.46
   533.8 1998.93   546.2 2005.04   584.1 2012.61  596.112013.801600.0706 2014.26
#Mann= 4 ,-1 , 0
       0      .1       0  388.54    .045       0  410.38      .1       0
  596.11      .1       0
Bank Sta=388.54,410.38
XS Rating Curve= 0 ,0
Exp/Cntr(USF)=0,0
Exp/Cntr=0.3,0.1

Type RM Length L Ch R = 1 ,31113   ,201.3,193,178.2
XS GIS Cut Line= 4
2116111.49949372314080.5446684222115897.16618999314080.544668422
2115727.63702321314056.326216024   2115569.00616314063.591751743
#Sta/Elev= 30
       0 1984.49    30.2 1980.13    40.3  1977.8    66.3 1973.31    79.4 1970.28
   118.8 1963.35   128.8 1960.87   174.5 1951.64   197.5 1947.55   230.5  1944.3
     257 1943.53   266.9 1941.45   276.9 1941.02  282.261938.987   286.8 1937.76
   290.1 1937.56   300.1 1937.68   303.4 1938.05  306.141938.987     320    1945
   329.7  1950.5   339.8 1955.45   352.9 1960.38     363 1963.09   385.6 1965.64
   435.5 1972.69   465.1 1975.47   478.7 1977.28   524.2 1985.85544.3808 1989.14
#Mann= 3 ,-1 , 0
       0      .1       0  282.26    .045       0  306.14      .1       0
Bank Sta=282.26,306.14
XS Rating Curve= 0 ,0
Exp/Cntr(USF)=0,0
Exp/Cntr=0.3,0.1

Type RM Length L Ch R = 1 ,30920   ,271.4,265,248.2
XS GIS Cut Line= 3
2115991.61815435313781.4467813042115754.27732084313954.608715951
2115577.48261834314058.748061263
#Sta/Elev= 30
       0 1993.08    31.1 1988.52    44.4  1985.1    75.8  1973.9    93.7 1966.55
   110.1 1959.21   131.2 1950.83   145.3 1945.93   157.2 1943.46  167.531938.908
   169.2 1938.34   173.5 1937.71   180.6 1937.62   190.6 1937.68  196.71 1938.91
   209.8 1942.02   229.5  1945.2   240.7 1945.76   258.5 1945.98   269.8 1945.56
   286.2  1946.2   329.1 1949.28   350.8 1951.49   363.5 1953.26   382.6 1957.34
   405.9 1961.05     425 1966.25   470.2 1976.48   489.7 1983.39498.9816  1986.1
#Mann= 3 ,-1 , 0
       0      .1       0  167.53    .045       0  196.71      .1       0
Bank Sta=167.53,196.71
XS Rating Curve= 0 ,0
Exp/Cntr(USF)=0,0
Exp/Cntr=0.3,0.1

Type RM Length L Ch R = 1 ,30655   ,248.9,257.9,266.7
XS GIS Cut Line= 4
2115703.41857081313555.004251382 2115599.2792255313823.829073001
2115577.48261834313959.4524064312115558.10785642314075.700977942
#Sta/Elev= 30
       0 1999.76      22 1997.63    29.1  1996.4    43.1 1995.79      61 1994.01
   101.6 1988.09   141.6  1977.9   152.7 1975.89   172.6 1970.29   183.9 1968.38
   200.5 1963.73   218.3 1960.42   229.6 1957.54   264.8 1951.81   282.4 1948.06
   299.3 1945.92   325.9 1943.74   332.6 1942.29  338.531938.764   342.5 1937.89
   359.1 1937.63  365.391938.763   372.4 1941.41   392.5 1943.58   425.7 1951.97
   438.9 1956.32   466.7 1966.89   495.7 1976.27     532 1990.99543.5069 1994.01
#Mann= 3 ,-1 , 0
       0      .1       0  338.53    .045       0  365.39      .1       0
Bank Sta=338.53,365.39
XS Rating Curve= 0 ,0
Exp/Cntr(USF)=0,0
Exp/Cntr=0.3,0.1

Type RM Length L Ch R = 1 ,30397   ,310.6,308.9,309.4
XS GIS Cut Line= 3
2115684.04380889313525.942108504 2115490.2961897 313703.94773363
 2115289.2830348  313835.9382992
#Sta/Elev= 30
       0 1998.97    16.3 1997.08    44.2 1995.22    97.6 1988.43   127.8  1981.1
   164.4 1974.22   177.8 1969.99   202.1 1963.75   218.3 1958.65   250.8 1951.93
     290 1946.59   307.4 1945.24   340.6 1944.46   357.9 1941.76   372.4 1941.24
  378.46 1938.46   380.9 1937.58   388.1 1937.26   392.1 1937.41  396.771938.458
   404.6 1942.76   427.4 1953.67     433 1957.34   442.5 1962.26   456.7 1968.66
   466.6 1974.72   474.5 1978.42   482.8 1981.22   492.2 1985.74503.5789 1989.97
#Mann= 3 ,-1 , 0
       0      .1       0  378.46    .045       0  396.77      .1       0
Bank Sta=378.46,396.77
XS Rating Curve= 0 ,0
Exp/Cntr(USF)=0,0
Exp/Cntr=0.3,0.1

Type RM Length L Ch R = 1 ,30088   ,203.8,201,200.1
XS GIS Cut Line= 2
2115412.79714203313383.0532393552115082.21526679313614.339459757
#Sta/Elev= 30
       0 1979.45      33 1974.63      41  1973.1    70.4 1965.72      93 1960.93
     109 1956.08   133.1 1950.29   141.2  1949.2   152.6 1946.03   181.1 1941.42
  185.691938.098   189.1 1937.06   201.1 1936.95   204.7 1937.03  207.781938.099
   213.1 1940.34   221.2 1940.41   229.2 1941.39   247.5 1945.32     266 1950.29
   273.2 1951.59   303.7 1961.86   313.2 1964.51   345.3 1971.98   353.1 1974.67
   362.6 1976.13   369.3 1977.55   374.3 1979.12   385.3 1981.34403.4572  1984.2
#Mann= 3 ,-1 , 0
       0      .1       0  185.69    .045       0  207.78      .1       0
Bank Sta=185.69,207.78
XS Rating Curve= 0 ,0
Exp/Cntr(USF)=0,0
Exp/Cntr=0.3,0.1

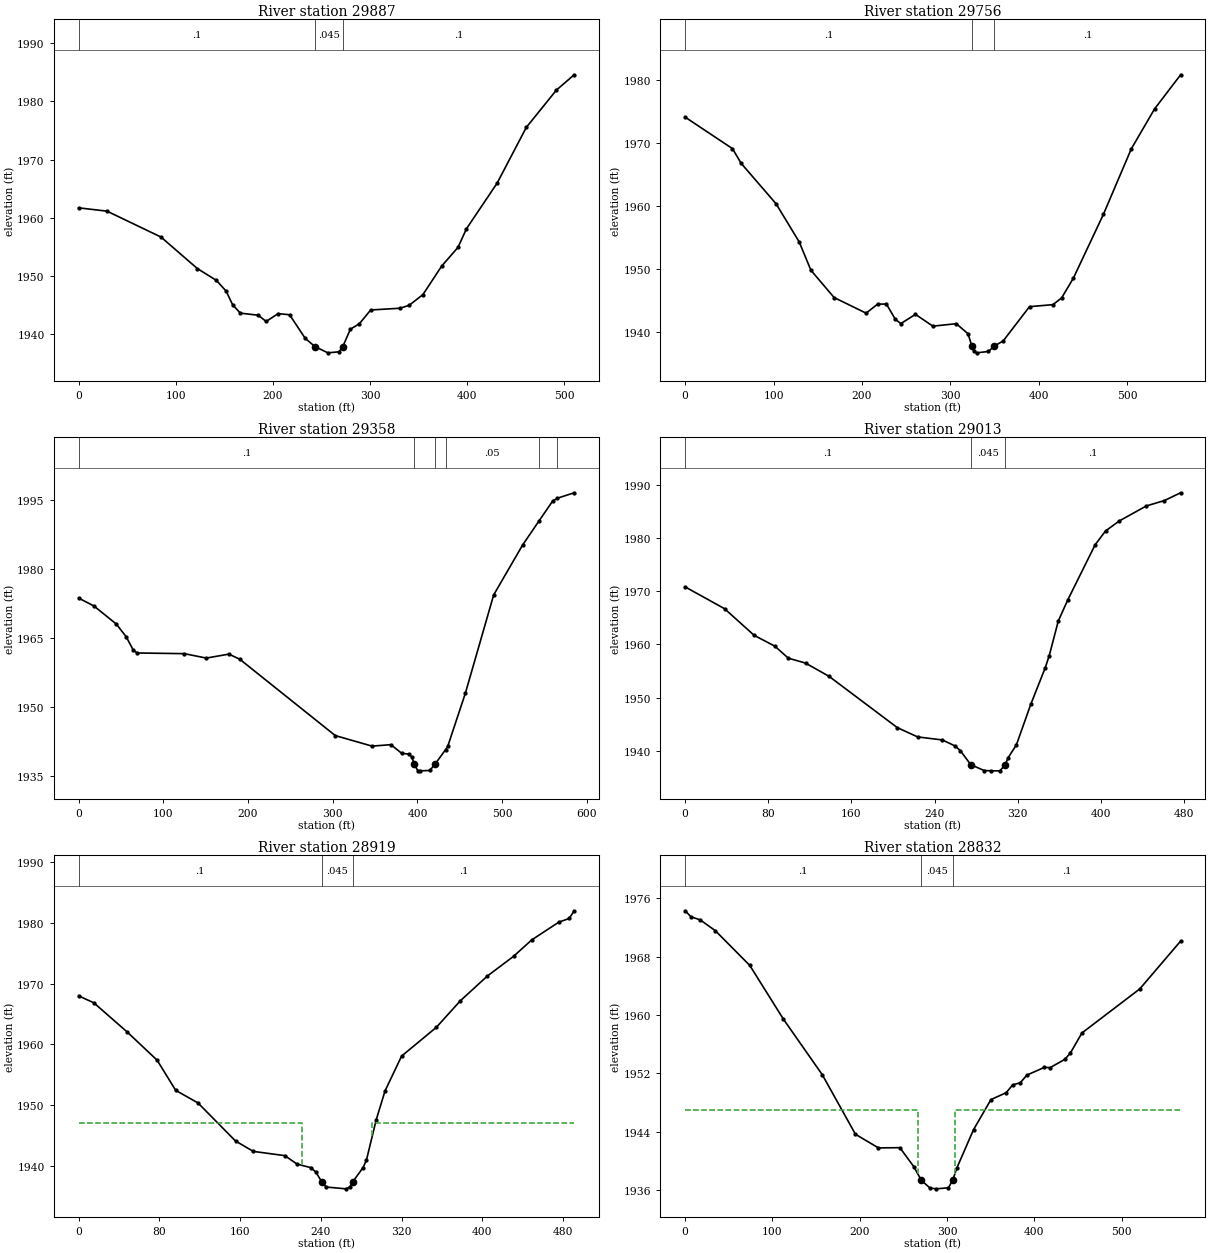
Type RM Length L Ch R = 1 ,29887   ,139.9,131.3,122.1
XS GIS Cut Line= 4
2115347.40732055313264.3828226042115158.50339185313304.343269061
 2115051.9422013313410.9044596132114970.81038576313556.215174002
#Sta/Elev= 30
       0 1961.72    29.2 1961.15    84.8 1956.71   122.2 1951.31   141.9 1949.27
   151.9 1947.43   158.6 1945.08   166.5 1943.66   184.9  1943.3   193.1 1942.23
   205.4 1943.58   217.2 1943.38   233.4 1939.31  243.391937.917   256.6 1936.85
   268.2 1937.03  271.971937.917   279.8  1940.9   289.1 1941.85   300.7  1944.2
   330.7  1944.5   340.1 1944.98   354.5 1946.84   373.7 1951.71   390.6 1954.94
   399.3 1958.13   430.9 1965.96   460.9 1975.51   491.9 1981.91510.2104 1984.54
#Mann= 3 ,-1 , 0
       0      .1       0  243.39    .045       0  271.97      .1       0
Bank Sta=243.39,271.97
XS Rating Curve= 0 ,0
Exp/Cntr(USF)=0,0
Exp/Cntr=0.3,0.1

Type RM Length L Ch R = 1 ,29756   ,383.4,397.9,409.4
XS GIS Cut Line= 4
2115016.82544532312977.394161686 2115003.5052965313255.906364264
2114981.70868934313415.7481500922114946.59193337313530.785798984
#Sta/Elev= 30
       0 1974.08    53.6 1969.08    63.4 1966.75   102.9 1960.34   129.1 1954.28
   142.3  1949.8   168.5 1945.48   204.7    1943   217.8 1944.44   227.7 1944.44
   237.8 1942.02     244 1941.35   260.5 1942.81   280.2 1940.94   306.7 1941.33
     320 1939.73  324.331937.774   326.6 1936.94   329.9 1936.71   343.1 1936.93
   349.51937.772   359.7 1938.59   389.5 1944.03     416 1944.35   425.9 1945.43
   439.2 1948.57   473.1 1958.67   504.6 1969.04   530.9 1975.37560.4298 1980.79
#Mann= 3 ,-1 , 0
       0      .1       0  324.33    .045       0   349.5      .1       0
Bank Sta=324.33,349.5
XS Rating Curve= 0 ,0
Exp/Cntr(USF)=0,0
Exp/Cntr=0.3,0.1

Type RM Length L Ch R = 1 ,29358   ,331.1,345.4,359.4
XS GIS Cut Line= 3
 2114985.3414572312959.230322387 2114748.0006237313163.876245152
2114496.12871876313265.593745224
#Sta/Elev= 30
       0 1973.62    18.1  1971.9    44.5 1967.97    56.1 1965.22    64.6 1962.28
    69.3 1961.68   124.9 1961.53   150.7 1960.57   177.4 1961.43   190.3 1960.31
     303 1943.71   346.3 1941.42   368.6 1941.73   381.6 1939.83   389.8  1939.7
   393.4 1939.02  396.141937.549   400.4 1936.06   403.2 1936.04   414.6 1936.12
  421.011937.553  433.141940.638   435.8 1941.39   456.6 1952.94     490 1974.32
   524.3 1985.21  543.741990.467   559.7 1994.75  565.09 1995.34585.0214 1996.53
#Mann= 6 ,-1 , 0
       0      .1       0  396.14    .045       0  421.01      .1       0
  433.14     .05       0  543.74      .1       0  565.09     .05       0
Bank Sta=396.14,421.01
XS Rating Curve= 0 ,0
Exp/Cntr(USF)=0,0
Exp/Cntr=0.3,0.1

Type RM Length L Ch R = 1 ,29013   ,90.3,93.9,97.7
XS GIS Cut Line= 3
2114959.91208218312959.2303223872114792.80476064312947.121096188
2114536.08916522312775.170084161
#Sta/Elev= 30
       0 1970.81    37.9 1966.71    66.4  1961.7    86.2 1959.67    99.3  1957.4
   115.8 1956.48   138.5 1953.98   204.1 1944.34   223.6  1942.6   247.3 1942.03
   259.4 1940.92   264.6 1940.04  274.641937.396   287.5 1936.28   294.6 1936.22
   302.8 1936.22  307.851937.395   310.7  1938.7   318.6 1941.11   332.4 1948.72
   346.3 1955.59   350.2  1957.9   358.9 1964.41   367.9 1968.32   394.3 1978.72
   404.3 1981.32   417.5  1983.2   443.6 1986.03   460.8 1987.03476.5278  1988.5
#Mann= 3 ,-1 , 0
       0      .1       0  274.64    .045       0  307.85      .1       0
Bank Sta=274.64,307.85
XS Rating Curve= 0 ,0
Exp/Cntr(USF)=0,0
Exp/Cntr=0.5,0.3

Type RM Length L Ch R = 1 ,28919   ,87.3,87,84.4
XS GIS Cut Line= 4
2114933.27178455312945.910173568 2114808.5467547312881.731274713
2114675.34526651312729.1550246052114531.24547474312694.038268627
#Sta/Elev= 30
       0 1967.97      15 1966.84    48.2 1962.02    77.8 1957.39    96.2 1952.43
   118.3 1950.36   155.5  1944.1   173.1 1942.39   204.4 1941.69   216.6 1940.29
   230.3 1939.71   235.3 1938.95  241.091937.334   245.3 1936.53   264.9 1936.23
   268.9 1936.53  271.481937.336   281.9 1939.73   285.2 1940.93     295 1947.63
   303.7 1952.35   320.1 1958.07   354.5 1962.79   378.1 1967.13   405.1 1971.24
     431 1974.47     449 1977.17     476 1980.11   486.2  1980.7491.1248 1981.97
#Mann= 3 ,-1 , 0
       0      .1       0  241.09    .045       0  271.48      .1       0
#XS Ineff= 2 , 0
             221    1947     291            1947
Permanent Ineff=
       F       F
Bank Sta=241.09,271.48
XS Rating Curve= 0 ,0
Exp/Cntr(USF)=0,0
Exp/Cntr=0.5,0.3

Type RM Length L Ch R = 1 ,28832   ,117.5,106.8,99.6
XS GIS Cut Line= 4
 2114979.2868441 312925.324489032114824.28874875312763.060857962
2114704.40740938 312657.71059003 2114522.7690164312629.859369772
#Sta/Elev= 30
       0  1974.3     6.8 1973.47    17.3 1973.05    34.6 1971.57    74.1  1966.8
   112.6 1959.43   157.2 1951.79   195.2 1943.62   221.5 1941.75   246.1 1941.78
   262.1 1939.16  270.721937.294   280.5 1936.25   287.7 1936.13   301.6 1936.27
  306.651937.295   311.1 1938.93   330.5 1944.26   350.4 1948.38   367.9 1949.33
   375.3  1950.4     384 1950.69   391.7 1951.75   411.6  1952.8   418.2 1952.77
   435.2 1953.91   441.5 1954.79   454.7 1957.53   520.9 1963.57567.7519 1970.14
#Mann= 3 ,-1 , 0
       0      .1       0  270.72    .045       0  306.65      .1       0
#XS Ineff= 2 , 0
             267    1947     309            1947
Permanent Ineff=
       F       F
Bank Sta=270.72,306.65
XS Rating Curve= 0 ,0
Exp/Cntr(USF)=0,0
Exp/Cntr=0.5,0.3

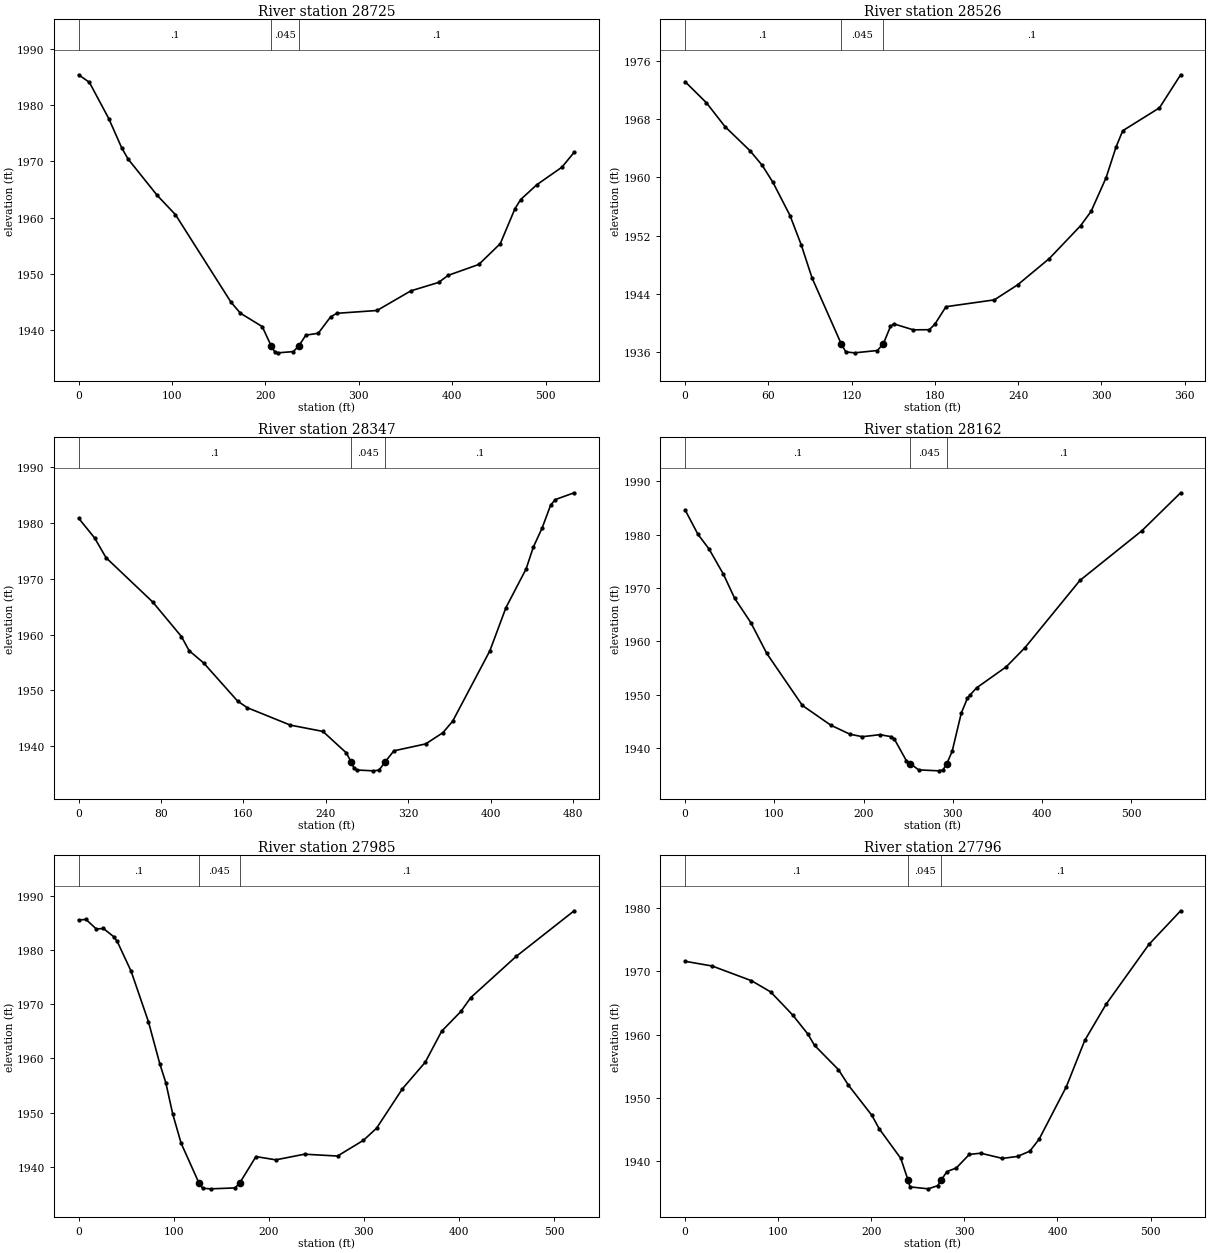
Type RM Length L Ch R = 1 ,28725   ,215.9,198.9,183.2
XS GIS Cut Line= 4
2115032.56743938312681.9290424282114887.25672499312633.492137632
2114734.68047488312606.8518399942114513.08163544312627.437524532
#Sta/Elev= 30
       0 1985.42    11.5 1984.08    32.3 1977.62    46.1 1972.43      53 1970.43
    84.2 1963.96   103.7 1960.54   163.3 1944.94   173.3 1943.01   196.6 1940.64
  206.04 1937.25   209.9 1936.15   213.3 1935.97   229.9 1936.19  235.971937.251
   243.3 1939.12   256.6 1939.45   269.9 1942.39   276.6    1943   319.5  1943.5
   355.7 1946.99   385.6  1948.5   395.5 1949.74   428.5 1951.69   451.5 1955.39
   467.2  1961.6   473.3 1963.23   490.7 1965.88   517.4 1968.97530.6084 1971.64
#Mann= 3 ,-1 , 0
       0      .1       0  206.04    .045       0  235.97      .1       0
Bank Sta=206.04,235.97
XS Rating Curve= 0 ,0
Exp/Cntr(USF)=0,0
Exp/Cntr=0.3,0.1

Type RM Length L Ch R = 1 ,28526   ,182.5,179.6,181.6
XS GIS Cut Line= 3
2114762.53169514 312394.940381512114649.91589149312554.782167338
2114526.37556686312615.358261074
#Sta/Elev= 30
       0 1973.16    15.4 1970.26    28.7    1967    46.8 1963.67    55.6 1961.66
    63.3 1959.33    75.6 1954.77    83.7 1950.74    91.5 1946.19  112.421937.177
   115.8 1936.03   122.1  1935.9   138.6 1936.22  142.971937.178     148 1939.53
   150.4 1939.88   164.5 1939.06     176 1939.08     180 1939.83     188 1942.24
   222.9 1943.18   239.7 1945.25   262.5 1948.86     285 1953.36   292.6 1955.34
   303.4 1959.96   310.6 1964.19   315.4 1966.42   341.9 1969.57 357.141 1974.11
#Mann= 3 ,-1 , 0
       0      .1       0  112.42    .045       0  142.97      .1       0
Bank Sta=112.42,142.97
XS Rating Curve= 0 ,0
Exp/Cntr(USF)=0,0
Exp/Cntr=0.3,0.1

Type RM Length L Ch R = 1 ,28347   ,171.1,185,197.2
XS GIS Cut Line= 4
 2114735.8913975312241.1532087822114560.30761761312367.089161252
2114487.65226042312484.5486553832114418.62967109312591.109845935
#Sta/Elev= 30
       0 1980.88    15.6 1977.32    26.6  1973.8      72 1965.84    99.8 1959.66
   107.3 1957.12   121.4 1954.92   154.3 1948.09   163.7  1946.9   205.6 1943.77
   237.2 1942.64   259.8 1938.81  264.711937.141   267.5 1936.01   270.2 1935.72
   286.3 1935.57   291.7  1935.7  297.471937.142   306.1 1939.16     337  1940.4
   353.7 1942.41   363.2 1944.48   399.3  1957.1   414.9 1964.84   434.5 1971.79
   441.4 1975.65   450.1 1979.15   458.3 1983.23   462.8 1984.22 481.154 1985.44
#Mann= 3 ,-1 , 0
       0      .1       0  264.71    .045       0  297.47      .1       0
Bank Sta=264.71,297.47
XS Rating Curve= 0 ,0
Exp/Cntr(USF)=0,0
Exp/Cntr=0.3,0.1

Type RM Length L Ch R = 1 ,28162   ,192.5,176.5,157.3
XS GIS Cut Line= 4
2114688.66541533312176.9743099272114485.23041518  312266.5825838
2114353.23984961312305.3321076372114298.74833171312493.025113723
#Sta/Elev= 30
       0 1984.61    14.4 1980.05    26.9 1977.28      43 1972.56    55.6 1968.05
    73.6 1963.54    91.5 1957.76   131.4 1948.02   163.2 1944.33   184.7 1942.64
   198.6 1942.17   218.5 1942.55   230.9 1942.17   234.3 1941.78     248 1937.66
  252.481937.112   261.7 1935.96   284.4 1935.78     289 1935.97   293.3 1937.11
   299.3 1939.46   309.5 1946.59   316.4 1949.39   319.8 1950.06   326.6 1951.31
   359.9 1955.25   380.9 1958.84   442.4 1971.41   511.9 1980.72555.2999 1987.82
#Mann= 3 ,-1 , 0
       0      .1       0  252.48    .045       0   293.3      .1       0
Bank Sta=252.48,293.3
XS Rating Curve= 0 ,0
Exp/Cntr(USF)=0,0
Exp/Cntr=0.3,0.1

Type RM Length L Ch R = 1 ,27985   ,196.5,189.5,181.3
XS GIS Cut Line= 3
2114435.58258776311990.4922264612114327.81047459312212.091065904
2114251.52234954312476.072197044
#Sta/Elev= 30
       0  1985.5     7.7 1985.62    18.7 1983.84      26 1983.95    36.9 1982.43
    40.6 1981.55    55.2 1976.06    73.4 1966.76    85.3 1959.03    91.7  1955.5
    98.9 1949.77   107.8 1944.33  126.371937.071   130.4 1936.03   138.7 1935.92
   164.6 1936.09  169.691937.073   186.5 1941.87   207.4 1941.27   237.6 1942.31
   272.3 1941.97   299.6 1944.88   313.3 1947.09   340.6 1954.39   364.5 1959.26
   381.8 1964.99   402.1 1968.65   412.3 1971.17   460.1 1978.78521.1995 1987.21
#Mann= 3 ,-1 , 0
       0      .1       0  126.37    .045       0  169.69      .1       0
Bank Sta=126.37,169.69
XS Rating Curve= 0 ,0
Exp/Cntr(USF)=0,0
Exp/Cntr=0.3,0.1

Type RM Length L Ch R = 1 ,27796   ,296,318.2,328.6
XS GIS Cut Line= 4
2114318.12309363311938.4225538052114192.18714116312094.631571773
2114175.23422448312231.4658278232114175.23422448312425.213447008
#Sta/Elev= 30
       0 1971.59    29.1 1970.84    71.3 1968.52    91.9 1966.75   115.7 1963.08
     132 1960.06     139 1958.31   164.7 1954.47   175.5    1952   200.7 1947.23
   208.5 1945.12   231.7 1940.44   239.41937.031   241.6 1935.94   261.2 1935.63
   271.3 1936.13  275.161937.032   281.3 1938.37   291.2 1938.91   305.3 1941.07
   317.6 1941.26   340.8 1940.44   357.1 1940.75   370.3 1941.59   380.2 1943.46
   409.6  1951.8   429.3 1959.09   452.2  1964.8   498.2 1974.25532.2798 1979.57
#Mann= 3 ,-1 , 0
       0      .1       0   239.4    .045       0  275.16      .1       0
Bank Sta=239.4,275.16
XS Rating Curve= 0 ,0
Exp/Cntr(USF)=0,0
Exp/Cntr=0.3,0.1