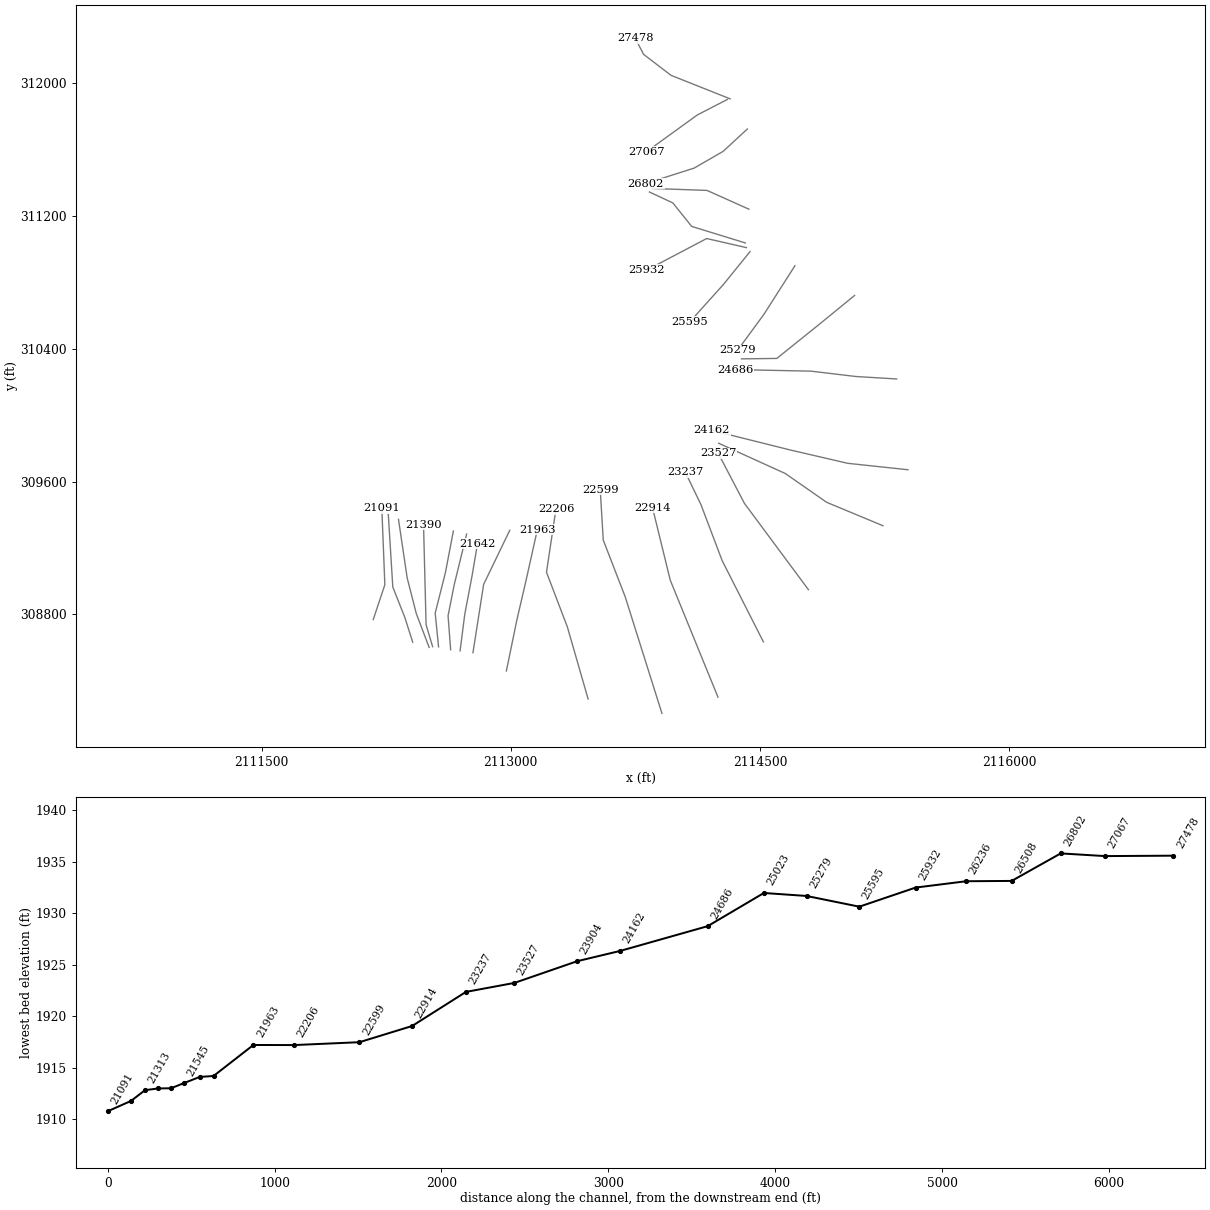
HEC-RAS study MLGNCK.prj: MLGNCK

--- MLGNCK.g01 (geometry) --- (continued)

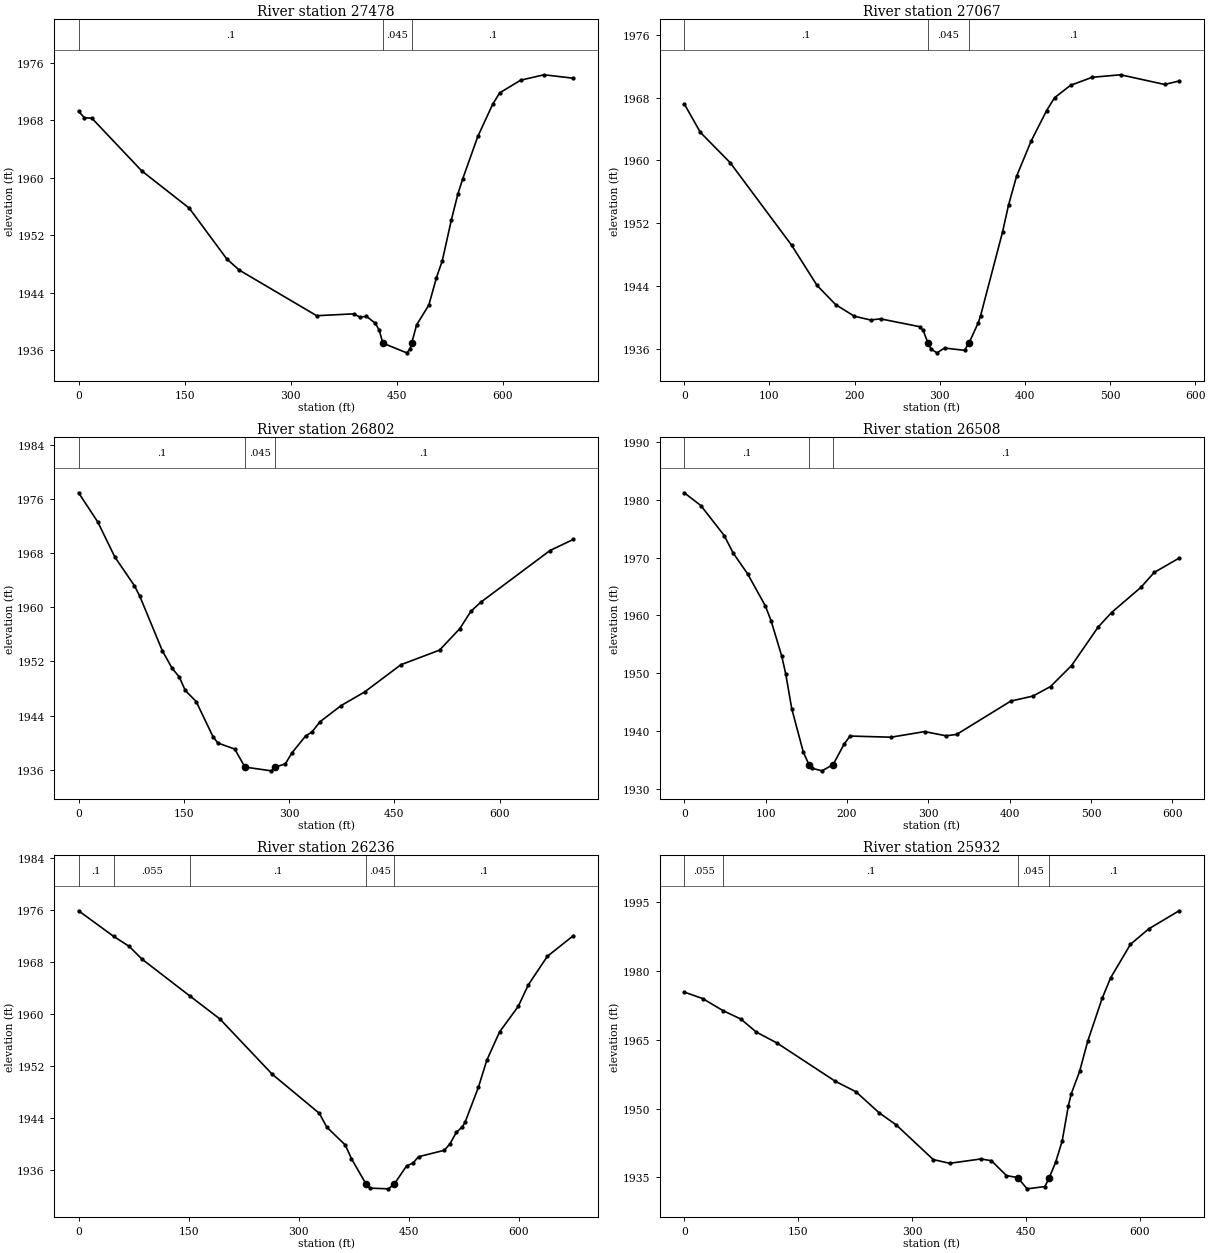
Type RM Length L Ch R = 1 ,27478   ,377.5,410.1,431.4
XS GIS Cut Line= 4
2114320.54493887311905.7276430672113964.53368862312047.405589596
2113799.84821231312173.3415420672113748.98946228 312270.21535166
#Sta/Elev= 30
       0 1969.24     8.2 1968.34    18.8 1968.27    89.4 1960.93   156.5 1955.75
   209.4  1948.7   227.1 1947.13   336.8 1940.77   389.2 1941.03   398.2 1940.56
   407.1 1940.69   419.8 1939.71   425.2 1938.76  430.371936.948   464.1  1935.6
   468.8 1936.12  471.151936.949   478.1 1939.49   495.4 1942.25   506.2 1946.08
   514.5 1948.45   527.3 1954.13   536.6 1957.76   543.4 1959.85   564.7 1965.74
   585.8 1970.23   595.6  1971.8   625.3 1973.57   658.3 1974.32699.8984 1973.84
#Mann= 3 ,-1 , 0
       0      .1       0  430.37    .045       0  471.15      .1       0
Bank Sta=430.37,471.15
XS Rating Curve= 0 ,0
Exp/Cntr(USF)=0,0
Exp/Cntr=0.3,0.1

Type RM Length L Ch R = 1 ,27067   ,268.3,265.5,264.9
XS GIS Cut Line= 3
2114303.59202219311902.0948752082114123.16455183311808.853833475
2113816.80112899311587.254994032
#Sta/Elev= 30
       0 1967.19      19 1963.56    53.8 1959.74   126.1 1949.23     156 1944.12
   177.8 1941.69   199.6 1940.22   218.8 1939.73   230.5 1939.88   276.6 1938.88
   280.6 1938.41  286.331936.793   289.9 1936.03   296.8 1935.56   305.7 1936.17
   329.2 1935.88  334.371936.793   345.4  1939.4     348 1940.26   373.8 1950.89
   380.9 1954.35   390.3 1957.99   407.5 1962.49   425.5 1966.32   434.9 1967.97
   453.7 1969.55   479.1 1970.57   512.5 1970.89   564.2 1969.66581.2025  1970.1
#Mann= 3 ,-1 , 0
       0      .1       0  286.33    .045       0  334.37      .1       0
Bank Sta=286.33,334.37
XS Rating Curve= 0 ,0
Exp/Cntr(USF)=0,0
Exp/Cntr=0.3,0.1

Type RM Length L Ch R = 1 ,26802   ,304.2,293.9,272
XS GIS Cut Line= 4
2114423.87700244311724.0892500812114278.56628805311589.542292314
2114103.65524295311488.6320739882113813.03381417311395.794673128
#Sta/Elev= 30
       0 1976.94    27.4 1972.61    51.6 1967.45    79.6 1963.19      87 1961.69
   119.5 1953.54   133.3 1950.99   143.3 1949.72     152 1947.71   167.5 1946.07
   191.5 1940.87   198.5 1939.93   222.5 1939.04     2371936.375   274.6 1935.82
   280.11936.375   294.6 1936.85   304.1 1938.49   323.4 1940.97   332.6 1941.57
   343.9 1943.07   373.8 1945.45   407.6 1947.49   459.2 1951.51   514.3 1953.67
   543.2 1956.85   559.1 1959.43   572.9 1960.74   671.7  1968.4705.0576 1970.05
#Mann= 3 ,-1 , 0
       0      .1       0     237    .045       0   280.1      .1       0
Bank Sta=237,280.1
XS Rating Curve= 0 ,0
Exp/Cntr(USF)=0,0
Exp/Cntr=0.3,0.1

Type RM Length L Ch R = 1 ,26508   ,273.2,272.1,261.7
XS GIS Cut Line= 3
2114433.29528948311241.0656716962114181.69247846 311354.08511622
2113849.36149277 311366.19434242
#Sta/Elev= 30
       0 1981.18    20.4 1978.97    49.2 1973.78      60  1970.8      78 1967.15
    99.6 1961.66   106.7 1959.09   119.7 1953.04   124.7 1949.93   132.1 1943.91
   146.3 1936.42  153.231934.231   157.1  1933.6   169.3 1933.15  183.031934.231
   196.5 1937.76   203.9 1939.16   254.2 1938.96   295.5 1939.93   321.8  1939.2
   334.9 1939.44   401.5  1945.2   428.8 1946.07   450.3 1947.71   476.1 1951.32
   508.9 1957.99   525.3 1960.49   561.4 1964.84   577.8 1967.42608.3728 1969.89
#Mann= 3 ,-1 , 0
       0      .1       0  153.23    .045       0  183.03      .1       0
Bank Sta=153.23,183.03
XS Rating Curve= 0 ,0
Exp/Cntr(USF)=0,0
Exp/Cntr=0.3,0.1

Type RM Length L Ch R = 1 ,26236   ,272.6,303.7,327.8
XS GIS Cut Line= 4
2114411.76777624311037.899765467 2114088.8550776311137.464514215
2113975.83563307311278.7388198712113834.56132742311344.666829177
#Sta/Elev= 30
       0 1975.91   47.931971.961    69.1 1970.43    86.2 1968.49  151.741962.796
   192.7 1959.26     264 1950.76   328.2 1944.75   338.4 1942.62   363.7 1939.86
   372.1 1937.75  391.881933.877   397.3 1933.23   422.5 1933.12  430.621933.876
   447.2 1936.65   456.1  1937.1   463.5 1938.06   498.6 1939.05   506.5 1940.05
     515  1941.8   523.3 1942.66   526.9 1943.34   545.1 1948.72   556.6  1952.9
     574 1957.26   599.4 1961.18   613.4 1964.54   639.2  1968.9674.7336 1972.09
#Mann= 5 ,-1 , 0
       0      .1       0   47.93    .055       0  151.74      .1       0
  391.88    .045       0  430.62      .1       0
Bank Sta=391.88,430.62
XS Rating Curve= 0 ,0
Exp/Cntr(USF)=0,0
Exp/Cntr=0.3,0.1

Type RM Length L Ch R = 1 ,25932   ,333.3,337.3,344.2
XS GIS Cut Line= 3
2114418.49512413311009.6449043352114179.30461409311064.405712795
2113819.76116206310875.097946568
#Sta/Elev= 30
       01975.411  24.128 1974.01  51.0541971.368  74.6141969.528  94.8081966.696
 121.7341964.349 199.1461955.945 226.0711953.685  256.691949.087 279.0671946.463
 327.9281938.888 349.5061938.074 390.7981939.024 404.5731938.635 424.3311935.398
 439.1621934.954 451.5211932.505 474.9941932.999 480.6681934.929 489.0781938.278
 497.671 1942.89 505.9031950.612 509.6111953.197 520.7341958.137 531.331 1964.68
 550.3971974.062  561.52 1978.51 587.6671985.835  611.83 1989.21 651.7151993.148
#Mann= 4 ,-1 , 0
       0    .055       0  51.054      .1       0 439.162    .045       0
 480.668      .1       0
Bank Sta=439.162,480.668
XS Rating Curve= 0 ,0
Exp/Cntr(USF)=0,0
Exp/Cntr=0.3,0.1

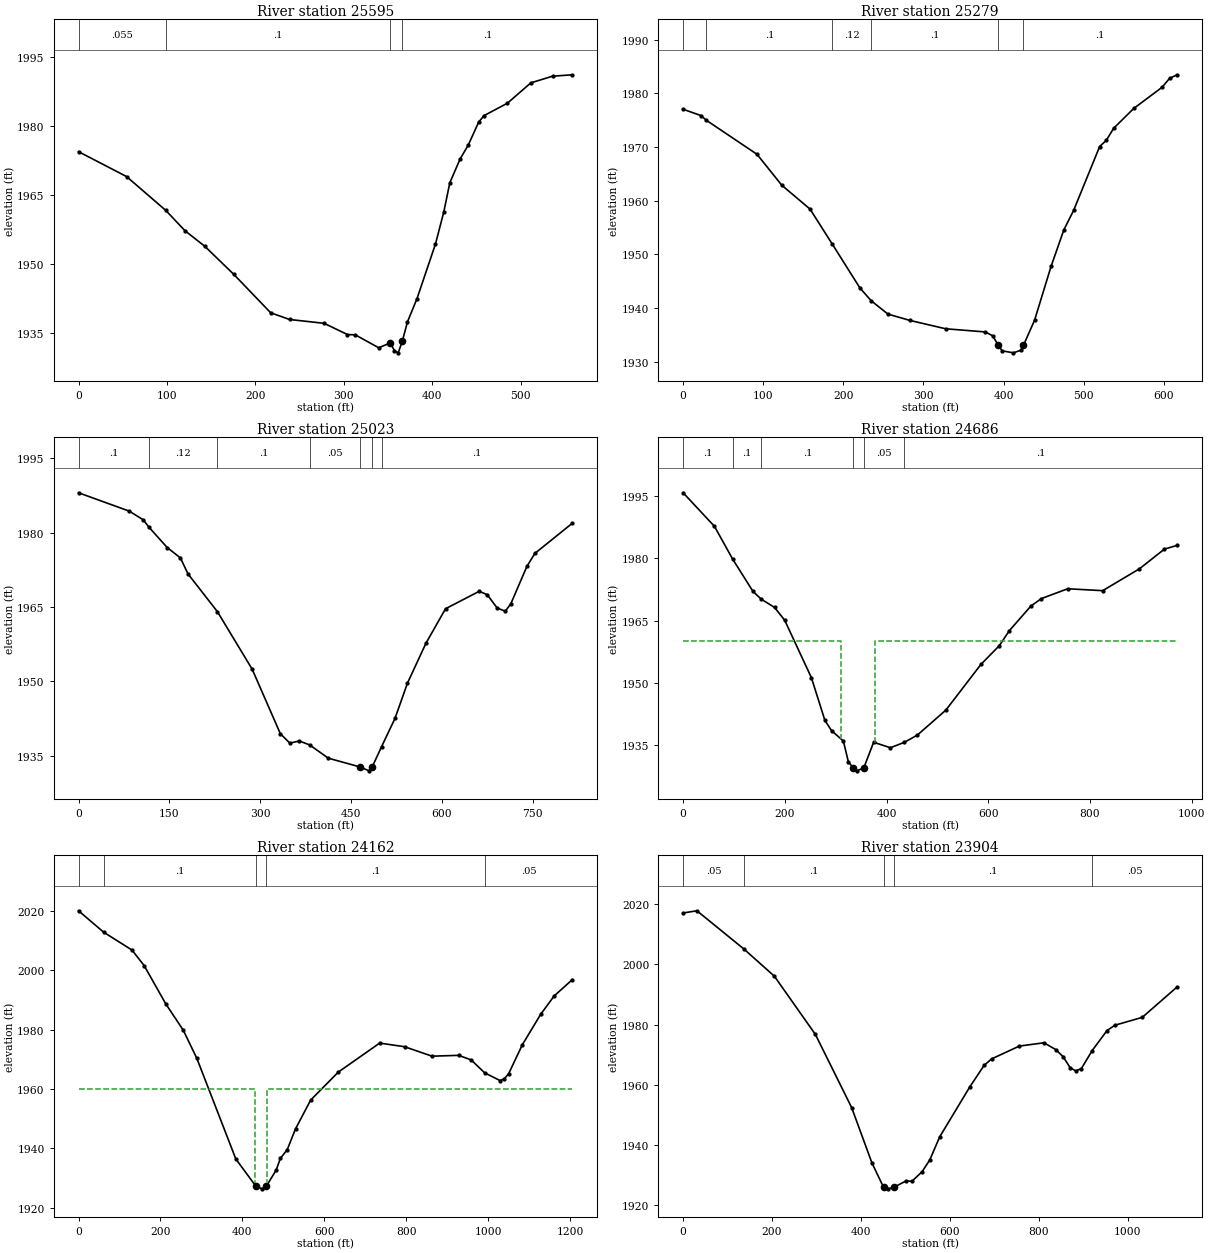
Type RM Length L Ch R = 1 ,25595   ,318.7,316.1,317.4
XS GIS Cut Line= 3
2114440.02263737310985.4264519372114279.91175763310787.642424019
 2114076.7458514 310561.60353497
#Sta/Elev= 30
       0 1974.45    54.3 1969.03   98.581961.673   120.4 1957.23   142.9 1953.82
   175.3 1947.78   217.2 1939.38   238.6 1937.91   277.6 1937.08   304.1 1934.63
     313 1934.56   339.4 1931.75   352.5 1932.81   352.6 1932.76   357.1 1931.15
   361.4 1930.65  366.051933.153   371.9 1937.39   382.7 1942.46   403.6 1954.36
   412.9 1961.27   419.8 1967.67   431.4 1972.85   440.6 1975.86   452.4 1980.89
   458.5  1982.3   484.9    1985   511.4 1989.43     536 1990.88558.3924 1991.19
#Mann= 4 ,-1 , 0
       0    .055       0   98.58      .1       0   352.6    .045       0
  366.05      .1       0
Bank Sta=352.5,366.05
XS Rating Curve= 0 ,0
Exp/Cntr(USF)=0,0
Exp/Cntr=0.3,0.1

Type RM Length L Ch R = 1 ,25279   ,257,255.8,252.2
XS GIS Cut Line= 3
2114710.46202248310900.6618685442114523.44175119310607.349500611
2114364.67634102310390.728898605
#Sta/Elev= 30
       0 1977.02    22.2 1975.85   29.071974.959    92.2 1968.64     123  1962.9
   158.4 1958.44  186.081951.943   220.6 1943.78  234.631941.394   255.6  1938.9
   282.9 1937.73   327.6 1936.17   377.1 1935.58   386.5 1934.85  393.461933.064
   398.2 1932.06   412.3 1931.69   421.7 1932.19   424.71933.063   438.6 1937.74
   459.2 1947.76   475.2 1954.58   487.4  1958.2   519.9 1970.09     528 1971.21
   537.4 1973.49   562.5 1977.18   597.7  1981.1   607.1 1982.76616.4351 1983.44
#Mann= 6 ,-1 , 0
       0    .055       0   29.07      .1       0  186.08     .12       0
  234.63      .1       0  393.46    .045       0   424.7      .1       0
Bank Sta=393.46,424.7
XS Rating Curve= 0 ,0
Exp/Cntr(USF)=0,0
Exp/Cntr=0.3,0.1

Type RM Length L Ch R = 1 ,25023   ,342.6,336.8,329.9
XS GIS Cut Line= 4
2115069.70239972310721.7144147132114862.50008476310552.185247926
2114601.47898669310342.2919938092114388.89479342310339.601054653
#Sta/Elev= 30
       0 1988.06    83.7 1984.36   106.8 1982.61  115.871981.171   146.4 1977.01
   168.1 1974.93   180.8 1971.68  229.261964.079   286.7 1952.46   333.1 1939.48
   348.8 1937.57   364.5    1938  381.361937.217   412.4 1934.53  464.511932.769
   479.7 1931.98  484.761932.768  500.29 1936.87   522.4 1942.56     543 1949.67
   573.4 1957.69   605.8 1964.67   661.5 1968.19   674.7  1967.5   691.1 1964.82
   704.6 1964.17   713.8 1965.72   740.2 1973.23   753.4 1975.84815.2628 1981.93
#Mann= 7 ,-1 , 0
       0      .1       0  115.87     .12       0  229.26      .1       0
  381.36     .05       0  464.51    .045       0  484.76     .05       0
  500.29      .1       0
Bank Sta=464.51,484.76
XS Rating Curve= 0 ,0
Exp/Cntr(USF)=0,0
Exp/Cntr=0.5,0.3

Type RM Length L Ch R = 1 ,24686   ,523.2,524,521.8
XS GIS Cut Line= 4
2115322.65068033310218.5087926622115077.77521719310233.308958017
2114807.33583208310265.600227881 2114353.9125844310275.018514925
#Sta/Elev= 30
       0  1995.8    61.6  1987.7   97.46 1979.79   137.2 1972.04  153.651970.136
   179.7 1968.17   199.7 1965.07   252.3 1951.19   278.8 1940.91     292 1938.43
   315.1 1935.95     325 1930.87  334.991929.461   341.5 1928.76   355.21929.462
   374.6 1935.65   407.6 1934.33  434.761935.621   460.5 1937.37   516.7 1943.41
   585.6 1954.42   621.7 1958.93   641.4 1962.54     684 1968.51   704.7  1970.3
   756.2 1972.66   825.1  1972.2   897.3 1977.47   946.5 1982.22971.2037 1983.11
#Mann= 6 ,-1 , 0
       0      .1       0   97.46      .1       0  153.65      .1       0
  334.99    .045       0   355.2     .05       0  434.76      .1       0
#XS Ineff= 2 , 0
          310.82    1960  376.62            1960
Permanent Ineff=
       F       F
Bank Sta=334.99,355.2
XS Rating Curve= 0 ,0
Exp/Cntr(USF)=0,0
Exp/Cntr=0.5,0.3

Type RM Length L Ch R = 1 ,24162   ,258,258.1,248.8
XS GIS Cut Line= 4
2115390.95238425309671.7406394452115028.66062173309710.476236696
2114684.59737556309790.2259957412114210.65595038309908.711352037
#Sta/Elev= 30
       0 2020.01   61.012012.828   130.6 2006.77   160.3 2001.53     213 1988.67
     256 1979.72     289 1970.27   384.1 1936.42  432.991927.249     449 1926.36
  458.72 1927.25   482.7  1932.7   492.8 1936.58   509.7 1939.58   529.9 1946.56
   566.9 1956.26   634.3 1965.67   735.4 1975.45   796.3 1974.22   863.2 1971.04
   928.2 1971.32   958.6  1969.8  991.961965.421  1029.6 1962.81  1039.7 1963.41
  1050.4 1965.14  1083.7 1974.86  1128.9  1985.2  1161.5 1991.311206.069 1996.85
#Mann= 5 ,-1 , 0
       0     .05       0   61.01      .1       0  432.99    .045       0
  458.72      .1       0  991.96     .05       0
#XS Ineff= 2 , 0
             430    1960     460            1960
Permanent Ineff=
       F       F
Bank Sta=432.99,458.72
XS Rating Curve= 0 ,0
Exp/Cntr(USF)=0,0
Exp/Cntr=0.5,0.3

Type RM Length L Ch R = 1 ,23904   ,380.4,376.9,373.9
XS GIS Cut Line= 4
2115240.56712433309334.5130869112114901.06100725309475.784088648
2114652.69747194309648.9549940042114251.67011217309831.240157536
#Sta/Elev= 30
       0 2017.11      31 2017.84  136.852005.101   205.2 1996.08   297.6  1976.7
   379.2 1952.34   424.7 1933.98  451.041925.834   460.7 1925.36  473.551925.834
   501.7    1928   514.6 1927.85   537.6 1931.07   554.8 1934.96   577.1 1942.64
   644.7 1959.22     677 1966.42   693.7 1968.56   756.3 1972.84   811.8 1973.94
   838.3 1971.65   854.8 1969.31   870.7 1965.64   883.2 1964.59   895.9 1965.36
  920.211971.356   953.6 1978.01   971.2 1979.77  1032.9  1982.41111.012 1992.48
#Mann= 5 ,-1 , 0
       0     .05       0  136.85      .1       0  451.04    .045       0
  473.55      .1       0  920.21     .05       0
Bank Sta=451.04,473.55
XS Rating Curve= 0 ,0
Exp/Cntr(USF)=0,0
Exp/Cntr=0.3,0.1

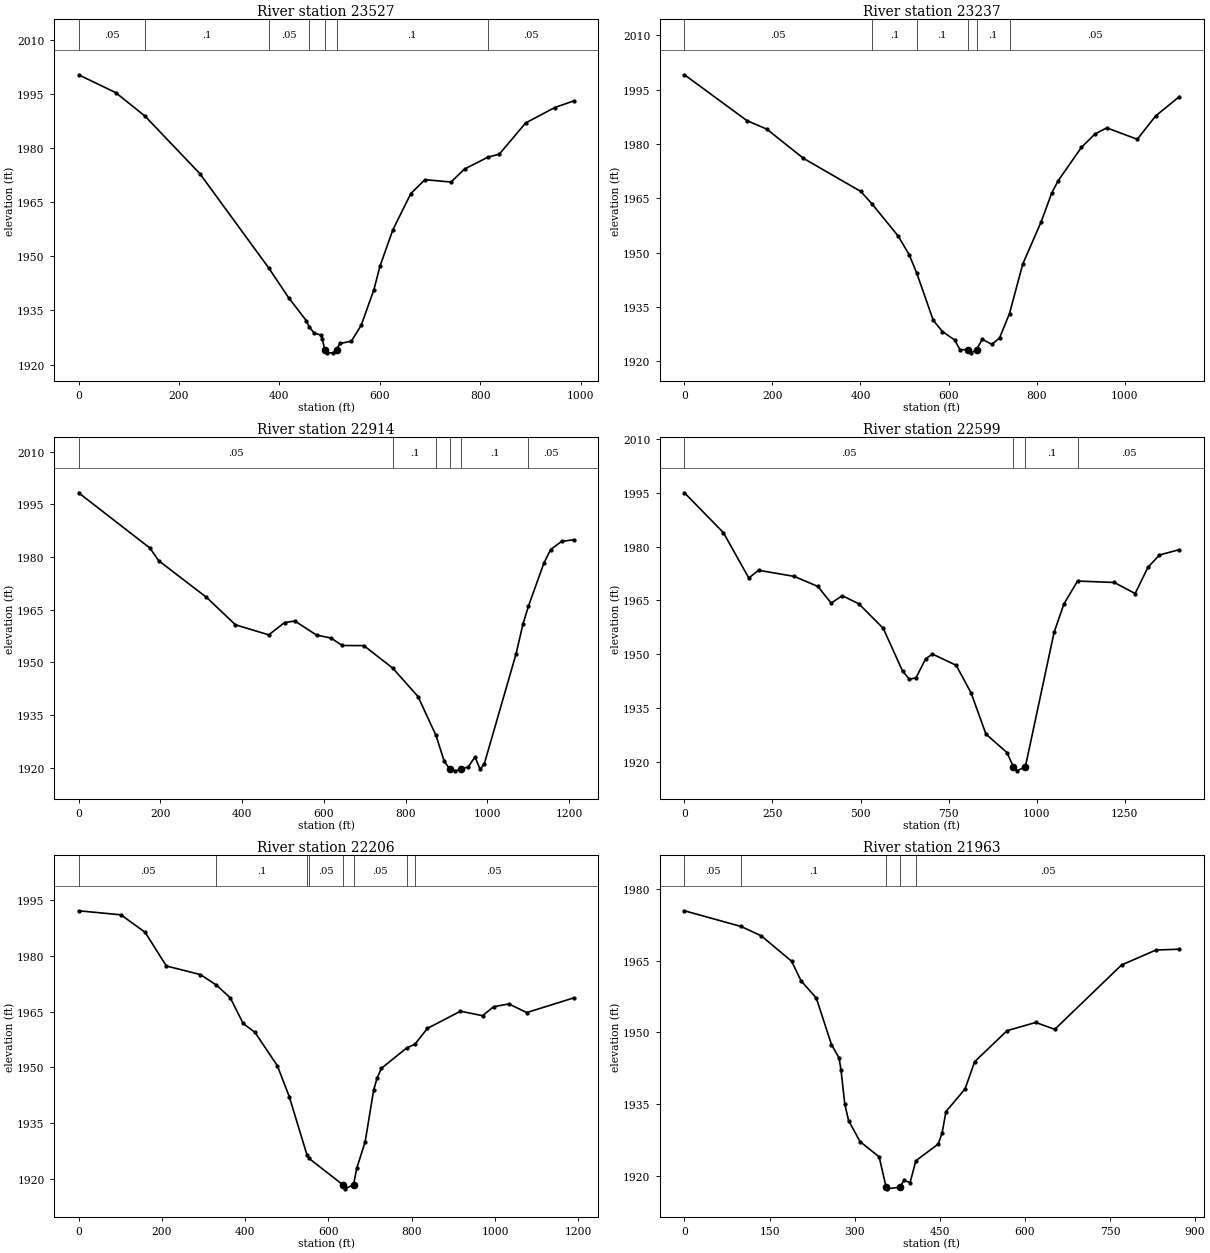
Type RM Length L Ch R = 1 ,23527   ,293.2,289.9,287
XS GIS Cut Line= 3
2114791.68990913 308949.435678952114406.61250117309468.948395016
2114249.39154763309769.718914844
#Sta/Elev= 30
       0 2000.31    73.7 1995.38  132.12 1988.88   241.5 1972.92  379.31 1946.66
   418.3 1938.55   453.5 1932.18   459.91930.357     469 1928.79     482 1928.18
   485.4 1927.16  490.281924.127   494.3 1923.26   506.4 1923.25  513.861924.126
   520.6 1925.85   543.3 1926.46   562.8 1930.84   588.2 1940.72   600.3 1947.25
   626.1 1957.37   661.8 1967.39   689.9 1971.24   741.8 1970.58   768.8 1974.19
  815.651977.489     838  1978.3   890.4 1986.95   948.7 1991.24986.0507 1993.05
#Mann= 7 ,-1 , 0
       0     .05       0  132.12      .1       0  379.31     .05       0
   459.9      .1       0  490.28    .045       0  513.86      .1       0
  815.65     .05       0
Bank Sta=490.28,513.86
XS Rating Curve= 0 ,0
Exp/Cntr(USF)=0,0
Exp/Cntr=0.3,0.1

Type RM Length L Ch R = 1 ,23237   ,322.9,322.8,320.6
XS GIS Cut Line= 4
2114520.54072838308634.9937718572114272.17719307309124.885148849
 2114144.5775786309462.1127013832114051.15643229309655.790687636
#Sta/Elev= 30
       0 1999.11   141.9 1986.47   187.2  1984.1   270.4 1976.05   400.7 1966.91
   425.91963.517   486.1 1954.53   510.9 1949.39  527.981944.326   565.3 1931.37
   586.3 1928.24   614.4  1925.9   625.9 1923.25   643.7 1923.23   651.4 1922.38
  663.64 1923.27   676.8 1926.14   698.5  1924.7   716.1 1926.52  738.621933.225
   768.7 1946.88   810.8  1958.6   834.6  1966.5   849.4 1969.91     902 1979.07
     933 1982.78   959.7 1984.46  1028.9 1981.31  1070.6 1987.741124.845 1993.11
#Mann= 6 ,-1 , 0
       0     .05       0   425.9      .1       0  527.98      .1       0
   643.7    .045       0  663.64      .1       0  738.62     .05       0
Bank Sta=643.7,663.64
XS Rating Curve= 0 ,0
Exp/Cntr(USF)=0,0
Exp/Cntr=0.3,0.1

Type RM Length L Ch R = 1 ,22914   ,315.8,315.5,320.4
XS GIS Cut Line= 3
2114247.11298308308302.3233484112113960.01385052309006.399792553
2113852.92131695 309443.88418503
#Sta/Elev= 30
       0 1998.26   174.6  1982.5   195.9 1978.91   312.8 1968.49   383.6 1960.66
   465.1  1957.8   503.9 1961.31   528.9 1961.73   581.9 1957.74   617.2  1956.9
   644.8 1954.77   697.7 1954.73   768.5 1948.31   830.2 1940.23  874.141929.166
   894.4 1921.76  908.771919.469   921.4 1919.07  935.26 1919.47   953.3 1920.24
   969.6 1923.02   982.2 1919.48   992.3 1921.05  1070.1 1952.42  1086.9 1960.87
 1100.391965.986  1137.8 1978.14  1154.5 1982.07  1181.2  1984.41210.763 1984.88
#Mann= 6 ,-1 , 0
       0     .05       0   768.5      .1       0  874.14      .1       0
  908.77    .045       0  935.26      .1       0 1100.39     .05       0
Bank Sta=908.77,935.26
XS Rating Curve= 0 ,0
Exp/Cntr(USF)=0,0
Exp/Cntr=0.3,0.1

Type RM Length L Ch R = 1 ,22599   ,393.9,393,395.1
XS GIS Cut Line= 4
2113909.88543055308204.3450730122113688.86466977308906.142952611
2113556.70792621309247.9276342332113538.47940985309550.976718605
#Sta/Elev= 30
       0    1995   110.6 1983.88   182.8 1971.23   210.3 1973.41     312 1971.69
   378.9 1968.89   416.6 1964.25   448.1 1966.32   495.1 1964.06   564.6 1957.21
   619.6 1945.25     639 1943.03   657.5 1943.43     685 1948.74   704.4 1950.05
   771.8 1946.91   814.4 1939.13   856.2 1927.74     916 1922.59  934.22 1918.61
   944.1  1917.5  968.09 1918.61  1049.7 1956.09  1077.8 1964.05 1116.461970.402
  1220.7    1970  1279.9 1966.91  1316.1 1974.19  1348.9 1977.661405.821 1979.16
#Mann= 4 ,-1 , 0
       0     .05       0  934.22    .045       0  968.09      .1       0
 1116.46     .05       0
Bank Sta=934.22,968.09
XS Rating Curve= 0 ,0
Exp/Cntr(USF)=0,0
Exp/Cntr=0.3,0.1

Type RM Length L Ch R = 1 ,22206   ,253.7,242.5,239.7
XS GIS Cut Line= 4
2113465.56534444 308290.930525692113340.24429451308726.136353623
2113214.92324458 309054.249647982113271.88735819309434.769926854
#Sta/Elev= 30
       0 1992.17   101.6 1991.08   159.6 1986.39   210.8 1977.29   292.7 1974.97
  330.881972.142   364.5 1968.69   395.2 1961.79   423.5 1959.41   477.3 1950.42
   505.9 1942.09   548.71926.283  553.491925.419  634.331918.345     640 1917.22
  660.381918.348   667.9 1922.71   688.3 1929.94   708.6 1943.79   716.6 1946.98
   727.2  1949.7  788.031955.197  807.891956.214   837.6 1960.45   917.2  1965.1
   970.3 1963.89   996.8 1966.31  1033.3 1967.06  1076.4 1964.731188.882 1968.68
#Mann= 8 ,-1 , 0
       0     .05       0  330.88      .1       0   548.7      .1       0
  553.49     .05       0  634.33    .045       0  660.38     .05       0
  788.03      .1       0  807.89     .05       0
Bank Sta=634.33,660.38
XS Rating Curve= 0 ,0
Exp/Cntr(USF)=0,0
Exp/Cntr=0.3,0.1

Type RM Length L Ch R = 1 ,21963   ,237.1,238.9,239.2
XS GIS Cut Line= 4
 2112973.3954029308459.5443019572113037.19521014308769.429079962
2113089.60219465308995.0069698332113160.23769552309311.727441469
#Sta/Elev= 30
       0 1975.42   99.631972.138   135.2 1970.19   188.8 1964.87   205.5 1960.76
   232.4 1957.15   259.1 1947.43   272.5 1944.61   275.9 1942.12   282.6 1934.92
   289.3 1931.51   309.4 1927.12   343.1 1923.93  355.481917.572   356.5 1917.23
  379.771917.573   386.8    1919   397.7 1918.55  407.861923.115   447.4 1926.62
   454.2 1928.99   460.9 1933.39   494.6 1938.15   511.4 1943.82   568.6 1950.33
   619.1 1952.05   652.7 1950.61   770.3 1964.07   831.1 1967.21872.4713 1967.38
#Mann= 5 ,-1 , 0
       0     .05       0   99.63      .1       0  355.48    .045       0
  379.77      .1       0  407.86     .05       0
Bank Sta=355.48,379.77
XS Rating Curve= 0 ,0
Exp/Cntr(USF)=0,0
Exp/Cntr=0.3,0.1

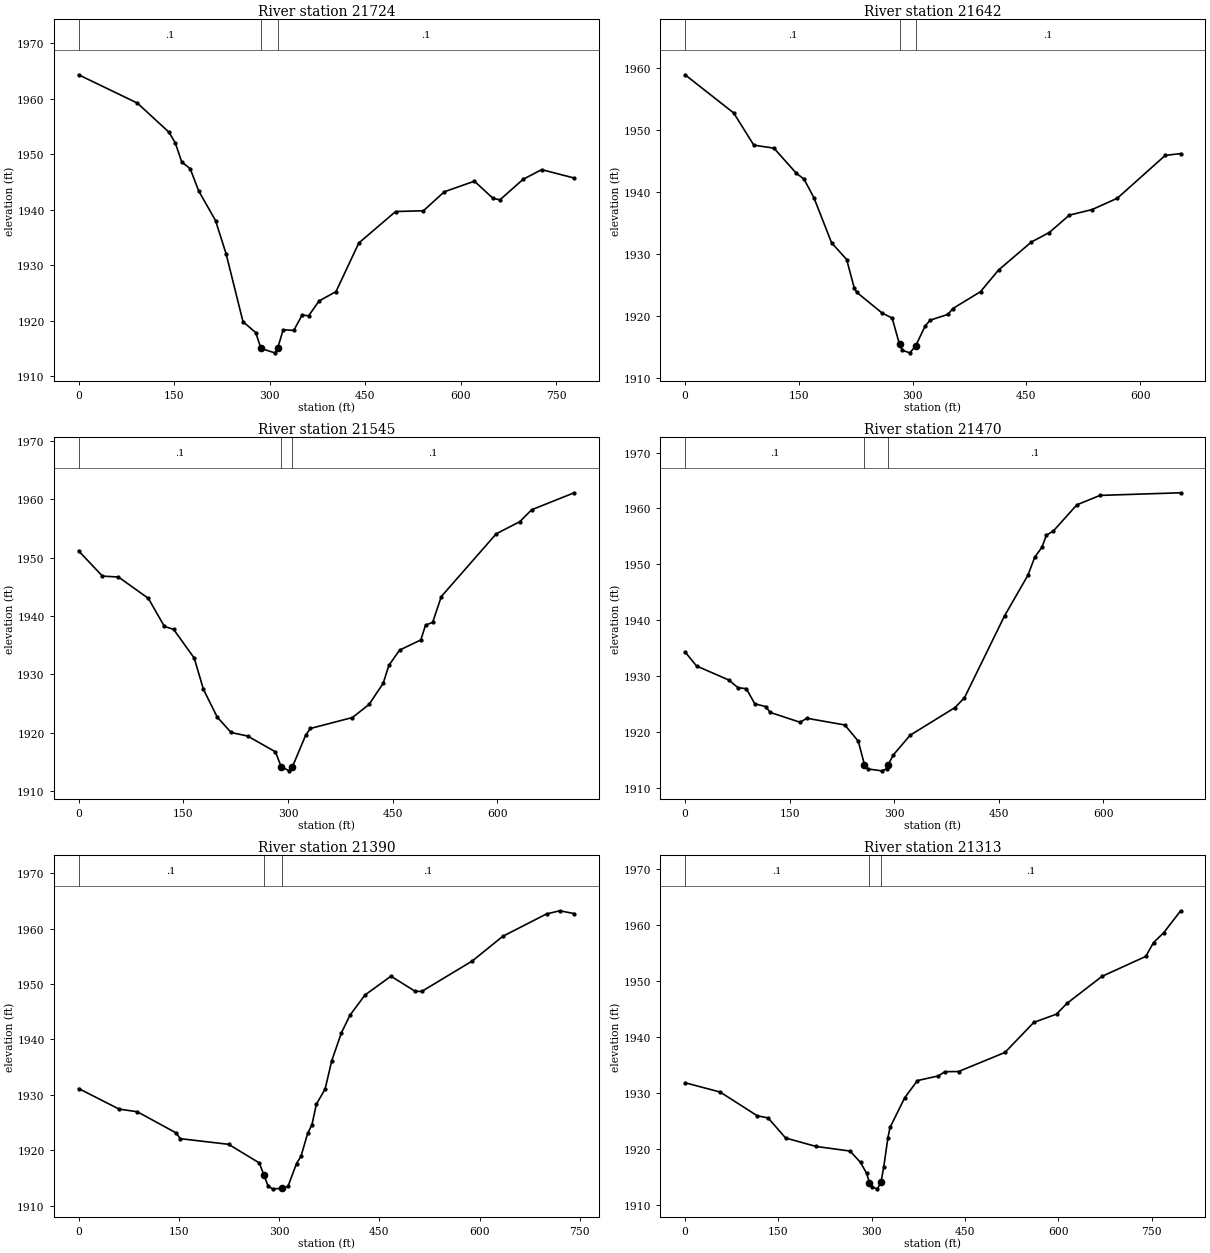
Type RM Length L Ch R = 1 ,21724   ,82.7,82.7,82.5
XS GIS Cut Line= 3
2112772.31178342308569.7593225192112836.68153025308981.335582568
 2112993.9024838309307.170312381
#Sta/Elev= 30
       0 1964.34    92.2 1959.24     142 1953.98     152 1952.02   161.9 1948.63
   175.2 1947.42   188.5 1943.43   215.1 1938.05   231.7 1932.04   258.2 1919.83
   278.2 1917.87   286.41915.015     308 1914.22   312.51915.004   321.3 1918.39
   337.9 1918.26   351.2 1921.05   361.2 1920.88   377.8 1923.58   404.3 1925.26
   440.1 1934.02   497.9 1939.69   541.6 1939.83   574.4 1943.25   621.7 1945.16
   650.9 1942.07   661.8  1941.8   698.2  1945.5   727.4 1947.24   778.4 1945.73
#Mann= 3 , 0 , 0
       0      .1       0   286.4    .045       0   312.5      .1       0
Bank Sta=286.4,312.5
XS Rating Curve= 0 ,0
Exp/Cntr(USF)=0,0
Exp/Cntr=0.3,0.1

Type RM Length L Ch R = 1 ,21642   ,96.5,96.6,96.7
XS GIS Cut Line= 4
2112694.82925477308580.8224514312112723.15574993308802.123194899
2112766.67260245 309031.575690012112799.63991497309225.423487604
#Sta/Elev= 30
       0 1958.97    64.1 1952.81    90.6 1947.62   117.1 1947.14   146.8 1943.07
   156.8 1942.15     170  1939.1   193.1 1931.88     213 1929.18   222.9 1924.63
   226.2  1923.9   259.6 1920.56     273 1919.74   282.71915.475   286.4 1914.53
   296.4 1914.13   304.21915.302   316.4 1918.44   323.1  1919.4   346.5 1920.33
   353.1 1921.28   389.5    1924   413.2 1927.48   456.6 1932.01     480 1933.52
   506.6 1936.34   536.5 1937.23   569.8 1939.06     633 1945.97   653.3 1946.26
#Mann= 3 , 0 , 0
       0      .1       0   282.7    .045       0   304.2      .1       0
Bank Sta=282.7,304.2
XS Rating Curve= 0 ,0
Exp/Cntr(USF)=0,0
Exp/Cntr=0.3,0.1

Type RM Length L Ch R = 1 ,21545   ,82.9,75.3,75.8
XS GIS Cut Line= 4
2112638.13311854308587.516690572 2112622.4964631308792.214725403
2112658.95349581308976.7784534792112734.14612577 309284.38466694
#Sta/Elev= 30
       0 1951.14    34.1 1946.83    57.1 1946.67    99.9 1943.02   122.9 1938.22
   136.1 1937.72   165.7 1932.79   178.8 1927.47   198.6 1922.71   218.5 1920.08
   242.2 1919.47   282.1 1916.76   290.31914.194   302.1 1913.52   306.3 1914.19
   325.5 1919.66   332.2 1920.77   392.4 1922.64   416.1 1924.87   436.4 1928.49
   444.6 1931.57     460 1934.18   490.4 1935.91   497.1 1938.45   507.3 1938.91
   519.7 1943.33   598.4 1954.06   632.2 1956.14   649.1 1958.17   710.1 1961.08
#Mann= 3 , 0 , 0
       0      .1       0   290.3    .045       0   306.3      .1       0
Bank Sta=290.3,306.3
XS Rating Curve= 0 ,0
Exp/Cntr(USF)=0,0
Exp/Cntr=0.3,0.1

Type RM Length L Ch R = 1 ,21470   ,73.7,79.7,81.4
XS GIS Cut Line= 4
2112565.33084794308605.108883833 2112545.0252686308808.164677212
2112606.54651129309051.9710834362112654.39636672309302.613183293
#Sta/Elev= 30
       0 1934.31    16.4  1931.8    62.6 1929.29    75.8 1927.92    87.9 1927.73
    99.9 1925.03   115.4 1924.54     122 1923.49   164.8 1921.73   174.7 1922.44
   229.1 1921.24   248.4 1918.33   257.2 1914.15   261.9 1913.37   282.1 1913.03
     289 1913.39   291.31914.123   298.5 1915.86   322.8 1919.41   387.1 1924.36
   400.7 1926.12   458.1 1940.76   491.5    1948   501.6 1951.31   511.6 1953.01
   518.3 1955.22   528.2 1955.96   561.8 1960.64   595.1 1962.33   710.7  1962.8
#Mann= 3 , 0 , 0
       0      .1       0   257.2    .045       0   291.3      .1       0
Bank Sta=257.2,291.3
XS Rating Curve= 0 ,0
Exp/Cntr(USF)=0,0
Exp/Cntr=0.3,0.1

Type RM Length L Ch R = 1 ,21390   ,75.1,76.7,79
XS GIS Cut Line= 3
2112529.47316713308606.1135068572112490.15601547308738.493274379
2112474.83693738309341.769175499
#Sta/Elev= 30
       0 1931.13    60.5 1927.42    87.9 1926.93   145.8 1923.12   152.3 1922.07
   224.5 1921.05   270.5 1917.68   277.31915.482   283.6 1913.49   290.2 1913.01
   304.71913.086   313.3 1913.45   326.1 1917.58   332.8  1918.9   342.7 1923.01
   349.2 1924.61   355.8  1928.3   368.9 1931.05   378.8 1936.16   393.3  1941.2
   406.1 1944.38   428.5 1948.02   467.4 1951.42   503.5 1948.71   513.3 1948.66
   589.1 1954.17   634.8 1958.63   700.2 1962.67   720.1 1963.24   741.6 1962.73
#Mann= 3 , 0 , 0
       0      .1       0   277.3    .045       0   304.7      .1       0
Bank Sta=277.3,304.7
XS Rating Curve= 0 ,0
Exp/Cntr(USF)=0,0
Exp/Cntr=0.3,0.1

Type RM Length L Ch R = 1 ,21313   ,83.3,83.5,85
XS GIS Cut Line= 4
2112508.55263323308601.685006934 2112431.0970414308805.886112668
2112376.41149234309020.0711798182112324.00450782309373.248684162
#Sta/Elev= 30
       0 1931.82    56.3 1930.16   115.9 1925.92   133.5 1925.52   161.5 1921.94
   210.6 1920.42   265.1  1919.6     282 1917.56   291.8 1915.61   296.31913.952
   299.9 1913.16   309.1 1912.84   314.8 1913.98   319.3 1916.75     326    1922
   329.4 1923.82   353.1 1929.16   373.5 1932.21   407.3 1933.05   417.5  1933.8
   439.5 1933.83   514.1 1937.24   560.5 1942.62     597  1944.1   613.6 1946.01
     670 1950.85   740.5 1954.43   752.9  1956.9   769.5 1958.69   796.5 1962.59
#Mann= 3 , 0 , 0
       0      .1       0   296.3    .045       0   314.8      .1       0
Bank Sta=296.3,314.8
XS Rating Curve= 0 ,0
Exp/Cntr(USF)=0,0
Exp/Cntr=0.3,0.1

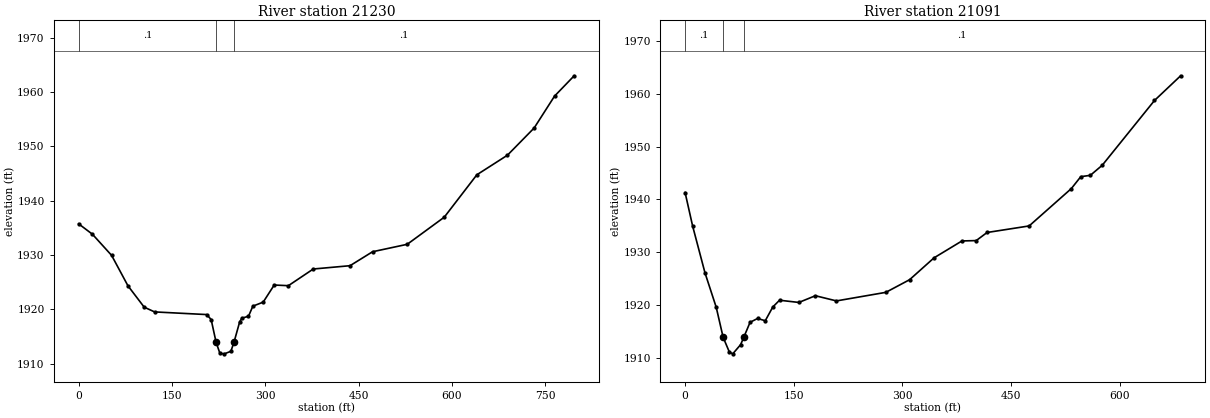
Type RM Length L Ch R = 1 ,21230   ,155.3,139.4,136.8
XS GIS Cut Line= 4
2112409.74339102 308633.097289712112362.74010507308780.821902682
2112289.82603966308965.3856307592112262.48326513309407.427152324
#Sta/Elev= 30
       0 1935.74    22.2 1933.82      53 1929.93    79.3 1924.32   105.4 1920.39
   122.1 1919.52   205.9 1919.03     213 1918.11   220.91913.935   227.1 1911.88
   234.2  1911.8   244.7 1912.27   249.71913.941   258.8 1917.68   262.4 1918.37
     273 1918.72     280 1920.58   296.6 1921.32   314.3 1924.47   337.1 1924.35
   377.1 1927.42   436.2 1928.03   472.4  1930.6   528.1 1931.97   587.6 1936.96
     640 1944.77   689.2 1948.38   732.1 1953.39   764.9 1959.26   796.4    1963
#Mann= 3 , 0 , 0
       0      .1       0   220.9    .045       0   249.7      .1       0
Bank Sta=220.9,249.7
XS Rating Curve= 0 ,0
Exp/Cntr(USF)=0,0
Exp/Cntr=0.3,0.1

Type RM Length L Ch R = 1 ,21091   ,240.4,227.7,231.6
XS GIS Cut Line= 3
 2112171.9778195308769.0619238392112241.97618423308979.057018023
2112223.74766788309441.605620486
#Sta/Elev= 30
       0 1941.31    10.4 1934.97    27.5  1926.1      43  1919.6    52.5 1913.94
    61.2 1911.11    65.8  1910.8    76.7 1912.54    81.11913.952    89.7 1916.76
   100.1 1917.49   110.7 1917.06   121.1 1919.66   130.4 1920.94   157.1 1920.52
   179.9 1921.79     209 1920.81   277.2 1922.43     310 1924.82   343.8 1928.96
   382.3 1932.15     402 1932.22     417 1933.75   475.1 1934.99   533.4 1942.06
   546.4 1944.31   559.6 1944.56     576 1946.46   648.2 1958.72   684.3 1963.39
#Mann= 3 , 0 , 0
       0      .1       0    52.5    .045       0    81.1      .1       0
Bank Sta=52.5,81.1
XS Rating Curve= 0 ,0
Exp/Cntr(USF)=0,0
Exp/Cntr=0.3,0.1