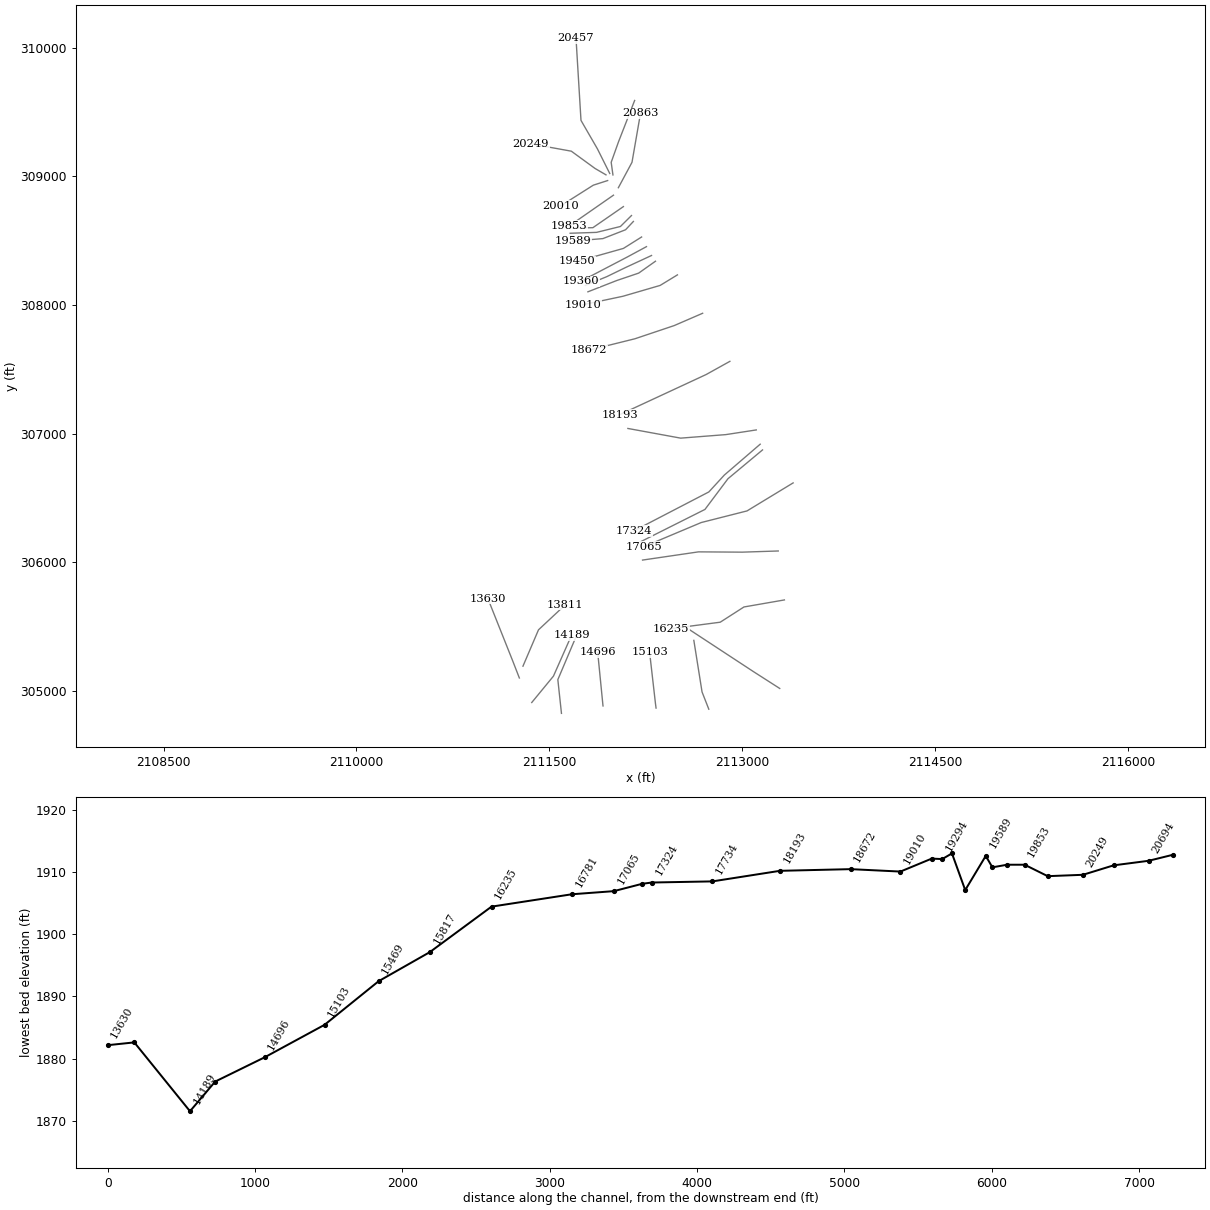
HEC-RAS study MLGNCK.prj: MLGNCK

--- MLGNCK.g01 (geometry) --- (continued)

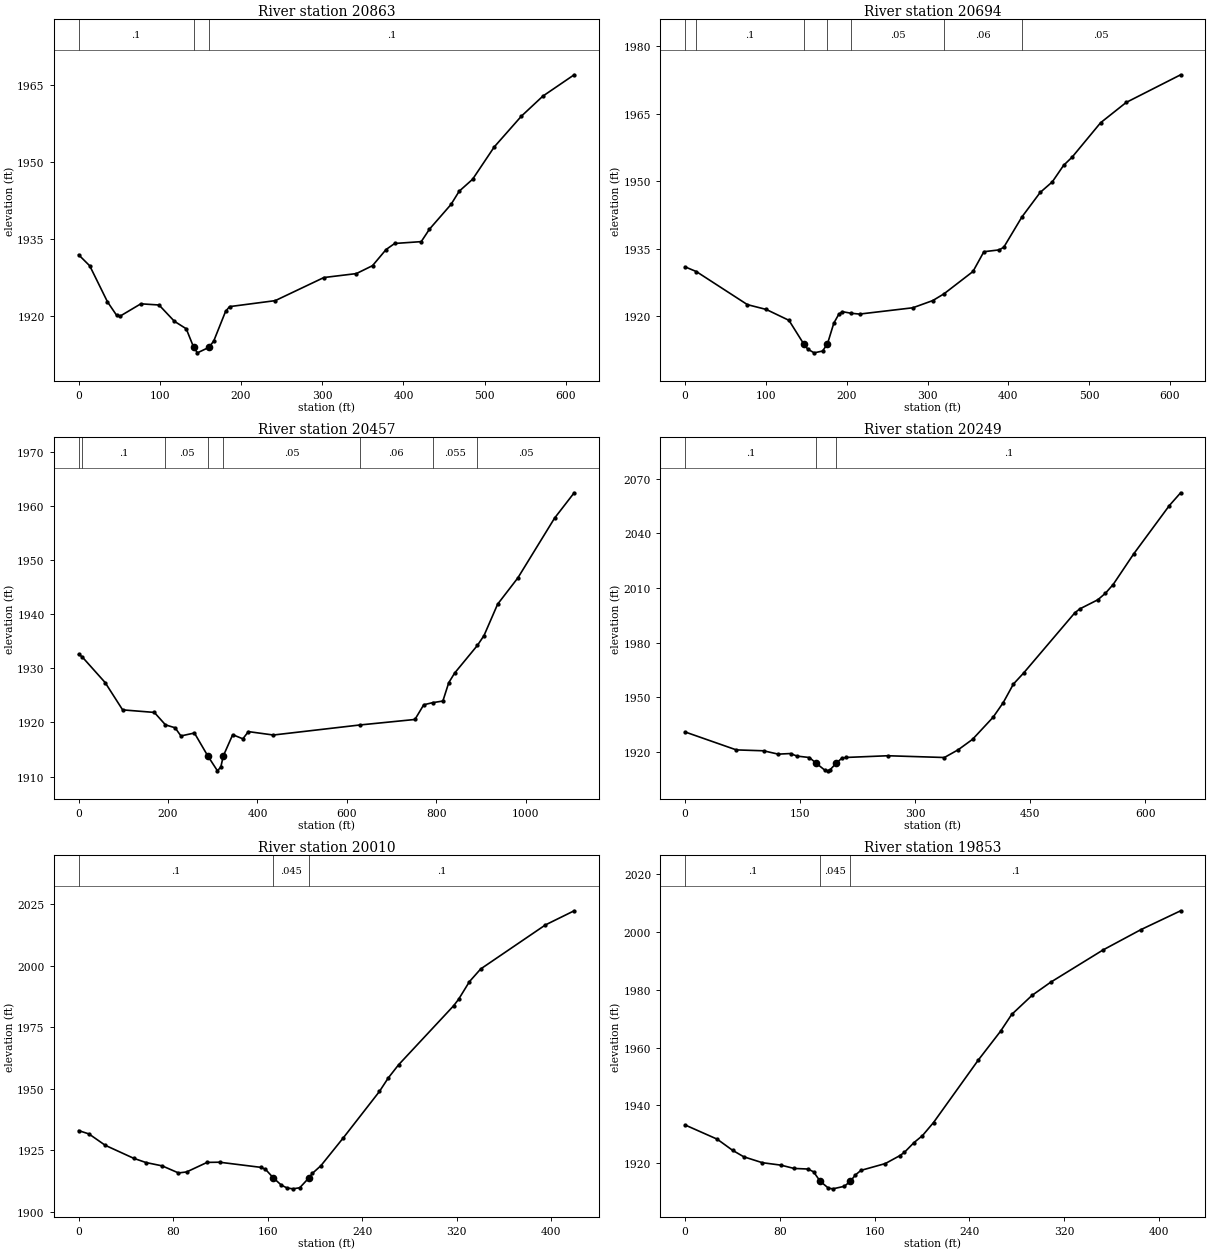
Type RM Length L Ch R = 1 ,20863   ,159.3,169,168.3
XS GIS Cut Line= 3
2112035.76821059308911.5752421072112141.71934429 309108.93519704
2112207.79771607309489.455475913
#Sta/Elev= 30
       0 1931.94    13.7 1929.78    35.5 1922.76    46.8 1920.12    50.6 1919.92
    76.6 1922.37      99 1922.14   117.9 1918.96   132.5  1917.5   141.71913.867
   146.3  1912.8   160.51913.876   166.4 1915.12   180.9 1920.87   185.8 1921.82
   242.1 1922.99     302  1927.5     342 1928.27   361.9 1929.82   378.6 1932.97
   389.2 1934.15   421.9 1934.51     432 1936.94   458.5 1941.76   468.6 1944.35
   485.1 1946.68   511.8    1953   545.2    1959   571.7 1962.92   610.2 1967.08
#Mann= 3 , 0 , 0
       0      .1       0   141.7    .045       0   160.5      .1       0
Bank Sta=141.7,160.5
XS Rating Curve= 0 ,0
Exp/Cntr(USF)=0,0
Exp/Cntr=0.3,0.1

Type RM Length L Ch R = 1 ,20694   ,210.3,237.1,245
XS GIS Cut Line= 4
2111993.61264892309010.9569216422111979.94126165 309108.93519704
2112036.90537526309268.4347151312112162.22642519309589.712315856
#Sta/Elev= 30
       0 1930.93   13.881929.888    77.1 1922.53   100.4 1921.46   128.5 1919.04
  146.651913.828   151.6 1912.66   159.6 1911.81   170.1 1912.21  176.191913.831
     184 1918.41   190.1 1920.37   194.5 1920.97  205.251920.618   215.8 1920.43
   281.7 1921.83   306.4 1923.43  320.311924.931   356.2  1929.9   369.7  1934.3
   388.8 1934.71   394.4 1935.32  416.811942.046   439.4 1947.49   454.3 1949.82
   468.3  1953.5   478.9 1955.34   514.1 1962.98   545.8  1967.5613.1486 1973.65
#Mann= 7 ,-1 , 0
       0      .1       0   13.88      .1       0  146.65    .045       0
  176.19      .1       0  205.25     .05       0  320.31     .06       0
  416.81     .05       0
Bank Sta=146.65,176.19
XS Rating Curve= 0 ,0
Exp/Cntr(USF)=0,0
Exp/Cntr=0.3,0.1

Type RM Length L Ch R = 1 ,20457   ,189.5,208,208.4
XS GIS Cut Line= 4
2111968.54843893309022.3497443622111872.84872808309213.749166071
2111745.24911361309434.7699268542111706.51351636310072.767999216
#Sta/Elev= 30
       0 1932.56    7.231932.177    59.3 1927.37    98.4 1922.33   169.3 1921.86
  194.281919.561   215.7 1919.03   228.8 1917.52     259 1918.06  289.05 1913.81
   310.5 1911.08   318.1  1911.8  323.47 1913.81   344.6 1917.75   367.3 1916.99
   379.7 1918.32   435.5 1917.69  628.681919.541   752.2 1920.56   771.9 1923.27
  792.041923.663   814.7 1923.96   827.8 1927.34     841 1929.12  891.851934.217
   906.7 1936.04   937.2 1941.84   982.3 1946.67  1064.5 1957.711108.373 1962.39
#Mann= 8 ,-1 , 0
       0      .1       0    7.23      .1       0  194.28     .05       0
  289.05    .045       0  323.47     .05       0  628.68     .06       0
  792.04    .055       0  891.85     .05       0
Bank Sta=289.05,323.47
XS Rating Curve= 0 ,0
Exp/Cntr(USF)=0,0
Exp/Cntr=0.3,0.1

Type RM Length L Ch R = 1 ,20249   ,226.6,239.1,258.6
XS GIS Cut Line= 4
2111939.52892128309011.5552610362111854.62021173309061.085341613
2111670.05648365309195.5206497182111355.61457656309252.484763322
#Sta/Elev= 30
       0 1930.91    66.8 1921.06   102.3 1920.57   121.4 1918.73   137.5 1919.06
   145.8 1917.67     162 1916.88   170.8  1913.8   182.1 1909.96   186.4 1909.56
   189.2 1910.19   197.21913.814   204.2 1916.43   209.8 1916.91   264.3 1917.85
   338.1 1916.88   356.2 1921.15   374.8 1926.85   401.5 1938.92   414.8 1946.98
   428.1  1957.2   441.5  1963.3   508.2 1996.34   514.8 1998.51   538.2  2003.5
   548.2 2007.12   558.2 2011.88   584.8 2028.59   631.5 2055.26   646.2 2062.26
#Mann= 3 , 0 , 0
       0      .1       0   170.8    .045       0   197.2      .1       0
Bank Sta=170.8,197.2
XS Rating Curve= 0 ,0
Exp/Cntr(USF)=0,0
Exp/Cntr=0.3,0.1

Type RM Length L Ch R = 1 ,20010   ,157.2,156.6,158.5
XS GIS Cut Line= 3
2111952.45411936308967.1766125642111840.94882446308931.207162596
2111585.74959552308769.429079962
#Sta/Elev= 30
       0 1933.01     8.7 1931.66    22.5 1927.04    46.6 1921.75    56.9 1920.04
    70.7 1918.67    84.5  1915.8    91.4 1916.21   108.7 1920.09   119.2 1920.16
   154.2 1918.07   158.1 1917.28   164.71913.823   171.5 1910.85   176.4 1909.69
   181.4 1909.34   187.1 1909.79   194.91913.821   197.8 1915.63     205 1918.75
   224.1 1930.15   254.5  1948.9     262 1954.41   270.7 1959.74   317.3 1983.74
   321.5 1986.37   330.7 1993.56   340.2  1998.7     395  2016.6   419.3 2022.34
#Mann= 3 , 0 , 0
       0      .1       0   164.7    .045       0   194.9      .1       0
Bank Sta=164.7,194.9
XS Rating Curve= 0 ,0
Exp/Cntr(USF)=0,0
Exp/Cntr=0.3,0.1

Type RM Length L Ch R = 1 ,19853   ,118.7,119.1,118.8
XS GIS Cut Line= 2
2111997.68332814308853.4966362132111654.10653184308614.486690959
#Sta/Elev= 30
       0 1933.26    27.1 1928.35    40.1  1924.5    49.6 1922.25    65.2 1920.22
    81.1 1919.36      92 1918.23   103.8 1918.03   108.5 1917.06   114.1 1913.79
   121.1  1911.4   124.8 1911.18   134.4 1912.05   139.5 1913.75   143.8 1915.97
   148.5 1917.56   169.1 1919.92   181.1  1922.6   185.1 1923.75   193.3 1927.16
   200.4 1929.55   209.8  1934.1   247.5 1955.64   266.4 1965.66   275.8 1971.45
     293 1978.06   308.8 1982.62   352.9 1993.74   384.9 2000.77   418.5  2007.3
#Mann= 3 , 0 , 0
       0      .1       0   114.1    .045       0   139.5      .1       0
Bank Sta=114.1,139.5
XS Rating Curve= 0 ,0
Exp/Cntr(USF)=0,0
Exp/Cntr=0.3,0.1

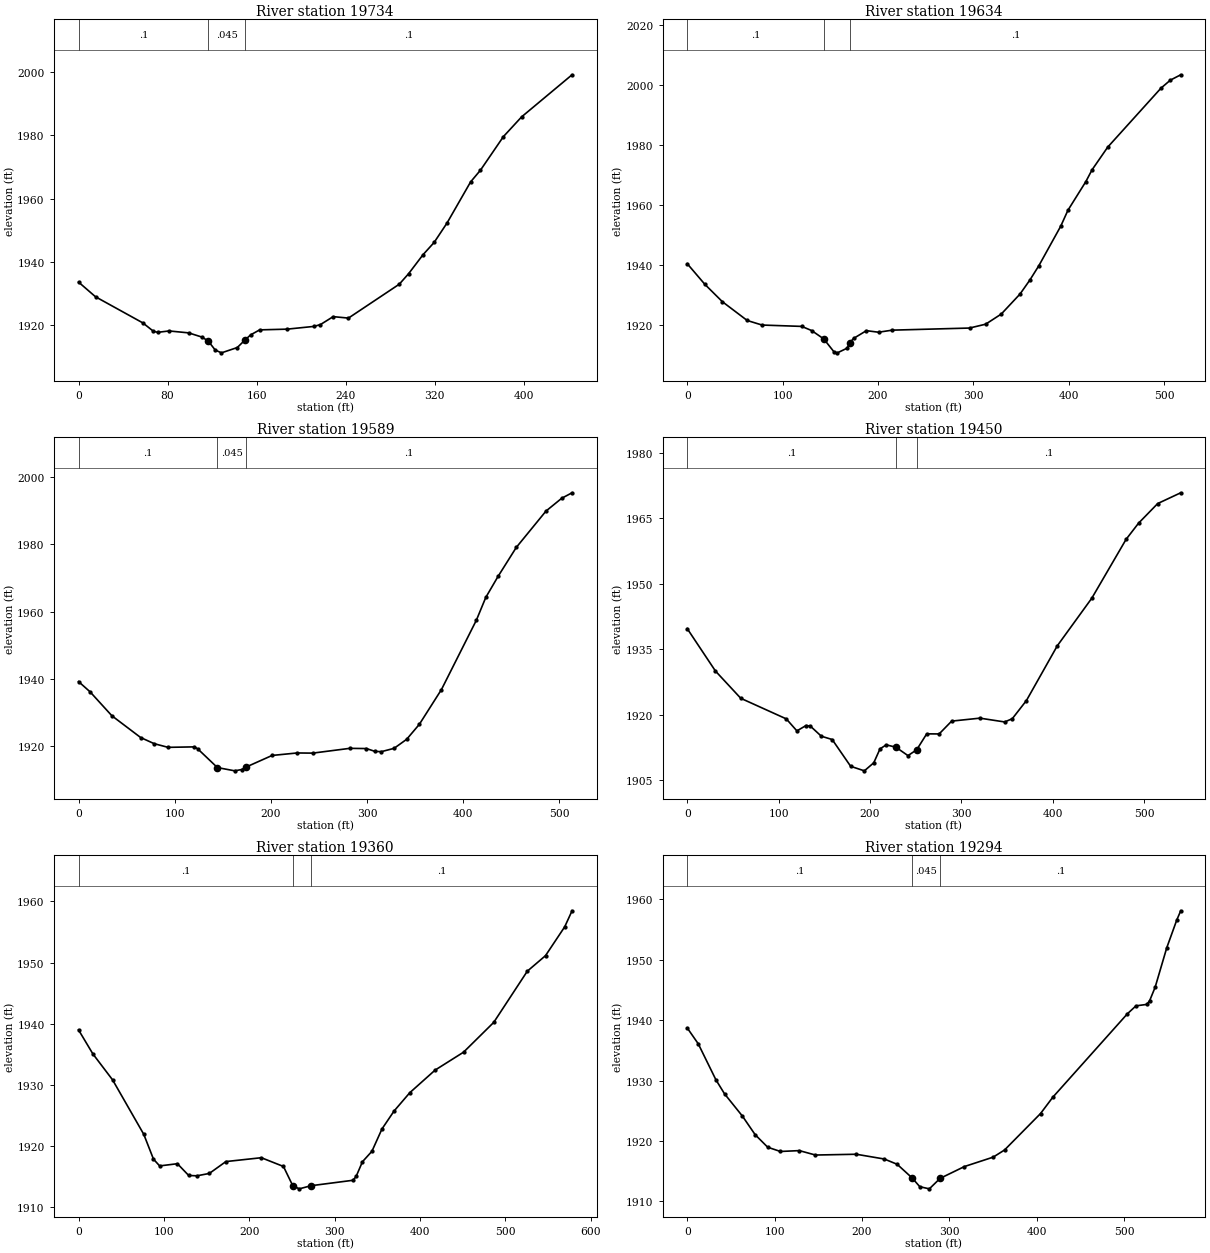
Type RM Length L Ch R = 1 ,19734   ,107.1,99.7,97
XS GIS Cut Line= 3
2112074.86672037308764.7376740022111837.69881843308600.851988954
2111682.38614613308597.921561174
#Sta/Elev= 30
       0 1933.58    15.3 1928.92    57.8 1920.66    67.2 1918.04    71.1 1917.67
    81.4 1918.11      99  1917.5     111 1916.16   116.61914.907   122.9 1912.05
   128.5 1911.18   142.7 1912.86   149.7 1915.28   154.8 1916.89   162.8 1918.45
   187.5 1918.68   211.6 1919.55   217.4 1920.12   228.9 1922.64   242.6 1922.18
   288.3 1932.91   296.6  1936.2   309.7 1942.27   319.6 1946.12   331.2 1952.27
   352.4 1965.29   361.3 1969.02   381.9 1979.64   398.3  1985.9   443.6 1999.21
#Mann= 3 , 0 , 0
       0      .1       0   116.6    .045       0   149.7      .1       0
Bank Sta=116.6,149.7
XS Rating Curve= 0 ,0
Exp/Cntr(USF)=0,0
Exp/Cntr=0.3,0.1

Type RM Length L Ch R = 1 ,19634   ,41.5,45,45.7
XS GIS Cut Line= 4
 2112137.7518264308695.2959882912112051.85200196308610.112414562
2111866.01303445308564.3582709882111660.94222547308557.522577356
#Sta/Elev= 30
       0 1940.47    18.5 1933.59    36.9 1927.79    62.9 1921.54    78.5 1920.02
   120.1 1919.57   130.5 1918.18   143.21915.393   154.1 1911.01   157.5 1910.76
   167.7 1912.32   170.7  1914.2   174.4 1915.55   187.9 1918.15   200.6 1917.63
     215 1918.32     296 1919.02   312.9  1920.3   329.3 1923.68     349 1930.36
   359.3 1935.02   368.7 1939.78   391.7 1952.98   399.2 1958.26     418 1967.82
   424.5 1971.74   440.9 1979.29   496.8 1998.96   506.6 2001.62   517.5 2003.41
#Mann= 3 , 0 , 0
       0      .1       0   143.2    .045       0   170.7      .1       0
Bank Sta=143.2,170.7
XS Rating Curve= 0 ,0
Exp/Cntr(USF)=0,0
Exp/Cntr=0.3,0.1

Type RM Length L Ch R = 1 ,19589   ,147,139.4,141.9
XS GIS Cut Line= 4
2112152.56585393308649.2114823382112091.79908106308584.745862418
2111915.41375186308515.9125632192111680.95032646308496.553197819
#Sta/Elev= 30
       0 1939.16      12 1936.11    34.7 1928.98    64.6 1922.51    78.7 1920.68
    93.1 1919.59   120.3 1919.73   123.8 1919.18   144.41913.572   162.5  1912.6
   169.6 1912.99   174.2 1913.72   201.3 1917.18   227.4 1917.92   243.5 1917.87
     282 1919.29   299.4 1919.23   308.3 1918.38   314.9 1918.31   328.1 1919.29
   341.2 1921.98   354.4 1926.44   377.4 1936.79   413.7 1957.42   423.5  1964.2
   436.2 1970.43   455.2 1979.07   486.1 1989.89   502.5 1993.71   513.2 1995.33
#Mann= 3 , 0 , 0
       0      .1       0   144.4    .045       0   174.2      .1       0
Bank Sta=144.4,174.2
XS Rating Curve= 0 ,0
Exp/Cntr(USF)=0,0
Exp/Cntr=0.3,0.1

Type RM Length L Ch R = 1 ,19450   ,89.5,89.9,93.8
XS GIS Cut Line= 3
2112216.43368504308528.4658531682112075.06346854308439.678461098
2111716.08606559308338.578702717
#Sta/Elev= 30
       0 1939.71    30.9 1929.98    58.6 1923.73   108.4 1919.01     120 1916.26
     130 1917.49   134.8 1917.34   146.7 1915.04   158.6 1914.28   178.8 1908.14
   193.8  1907.1   204.1 1908.95   210.9 1912.13   217.7 1913.06   228.31912.518
   241.5 1910.59     2511911.914     262 1915.58   275.6 1915.56   289.3  1918.5
   320.2 1919.18   347.2 1918.31   355.6 1919.05   371.1 1923.22   404.9 1935.78
   442.6 1946.68   480.1 1960.17   493.8 1963.89   514.7 1968.38   539.9 1970.85
#Mann= 3 , 0 , 0
       0      .1       0   228.3    .045       0     251      .1       0
Bank Sta=228.3,251
XS Rating Curve= 0 ,0
Exp/Cntr(USF)=0,0
Exp/Cntr=0.3,0.1

Type RM Length L Ch R = 1 ,19360   ,66.4,66.3,66.2
XS GIS Cut Line= 3
2112254.22602325308453.4334981132112105.26231158308372.958849279
2111742.97054906308183.837992115
#Sta/Elev= 30
       0    1939    16.8 1935.07    39.9 1930.82    76.4 1921.92    87.8 1917.85
      95 1916.75   115.8 1917.11     129 1915.19   138.7 1915.13   153.2 1915.52
   172.6 1917.46   214.1 1918.09     240 1916.66   250.91913.513   258.5    1913
   272.31913.511   321.4  1914.4   325.1 1915.02   332.5 1917.43   343.6 1919.14
   355.4  1922.8   369.5 1925.72     388 1928.73   417.6 1932.42   450.9 1935.35
   486.3 1940.23   525.6  1948.6   546.9 1951.14   569.4 1955.86     578 1958.48
#Mann= 3 , 0 , 0
       0      .1       0   250.9    .045       0   272.3      .1       0
Bank Sta=250.9,272.3
XS Rating Curve= 0 ,0
Exp/Cntr(USF)=0,0
Exp/Cntr=0.3,0.1

Type RM Length L Ch R = 1 ,19294   ,72,71.2,68.1
XS GIS Cut Line= 4
2112293.52467456308384.6135888152112093.32343655 308291.79301483
2111944.90163515 308219.733154732111779.27150895 308151.97537583
#Sta/Elev= 30
       0  1938.7    12.6 1936.08    32.8 1930.13    42.7  1927.8    63.2 1924.11
    77.7 1921.05    92.1 1918.97   106.6 1918.27   128.3 1918.41   146.7 1917.68
   193.4 1917.81   225.5 1917.02   240.2 1916.15   257.4 1913.88   266.1 1912.44
     277 1912.09   289.3 1913.82   317.2 1915.78     350 1917.33     363 1918.51
   404.2 1924.54   418.3 1927.25   503.6 1941.04   513.4 1942.35   525.9 1942.59
   529.1 1943.23   535.3 1945.42   548.6 1951.95   560.1 1956.56   564.6 1958.07
#Mann= 3 , 0 , 0
       0      .1       0   257.4    .045       0   289.3      .1       0
Bank Sta=257.4,289.3
XS Rating Curve= 0 ,0
Exp/Cntr(USF)=0,0
Exp/Cntr=0.3,0.1

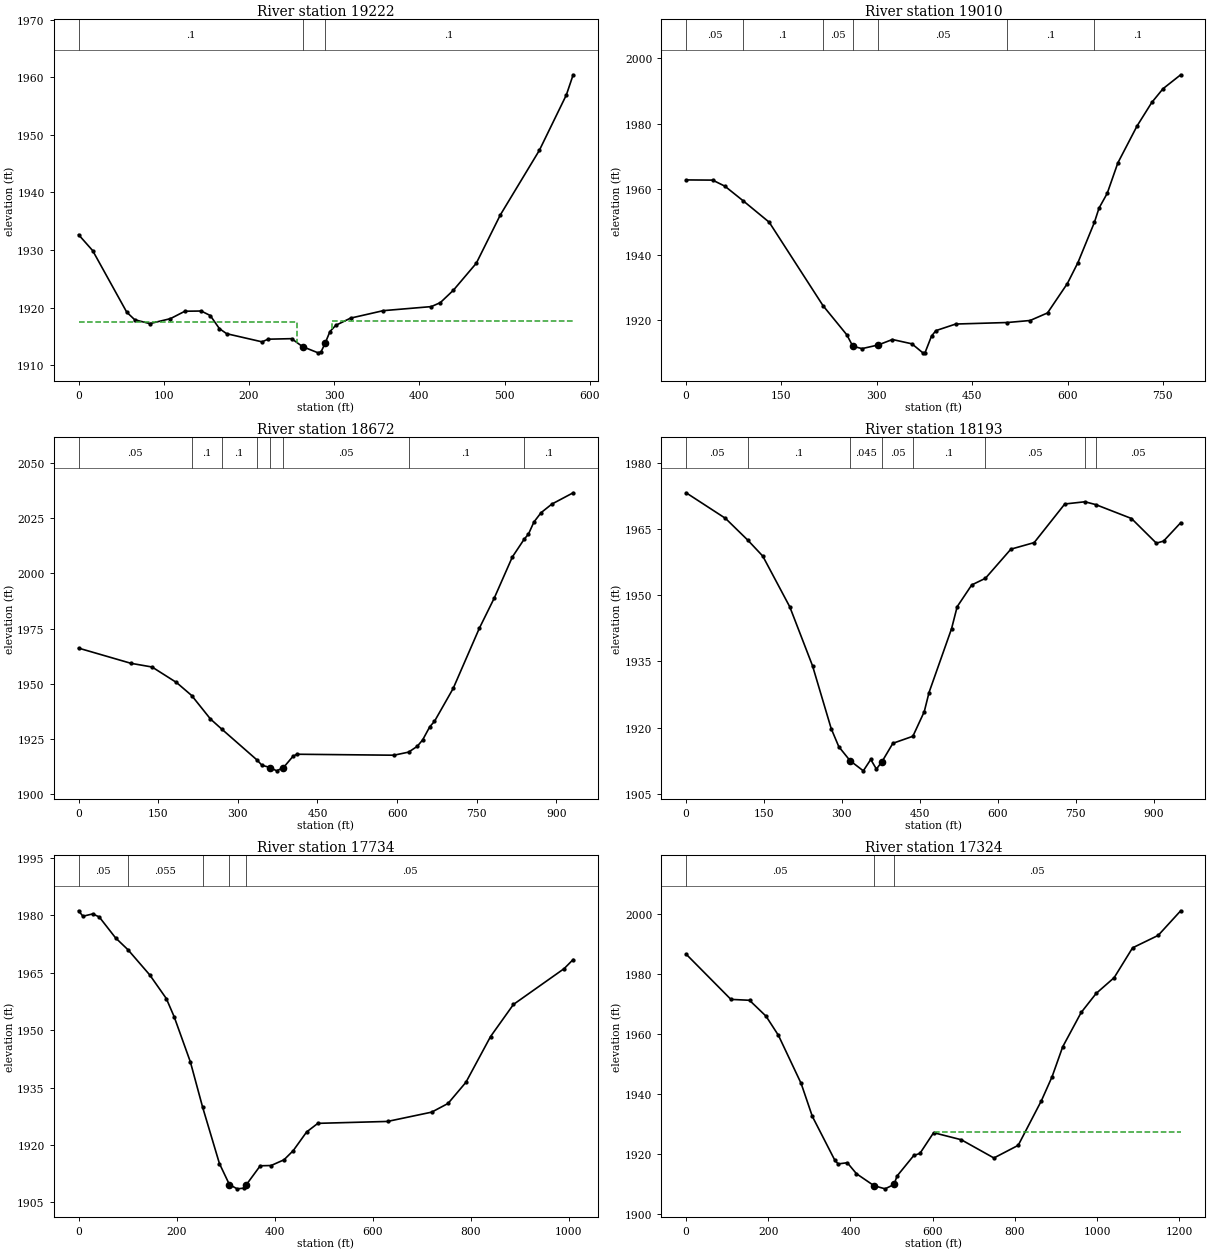
Type RM Length L Ch R = 1 ,19222   ,211.3,212.2,193.2
XS GIS Cut Line= 4
2112324.14982977308340.043916606 2112193.7457936308247.735441562
 2112023.1377034308190.0221340092111798.96362096308102.298884513
#Sta/Elev= 30
       01932.666  16.5461929.903  56.5571919.217  65.972  1917.9  83.6531917.236
 107.7711918.094 124.8111919.385 143.9471919.421 154.5631918.639 165.3261916.366
 173.8441915.484 215.406 1914.07 222.3331914.532  250.041914.623 263.0061913.235
 281.2121912.163 284.6751912.339  289.551913.868 295.0651915.856 301.9921916.945
  319.311918.188  357.711919.485 414.0791920.188 424.6481920.877 440.0341923.036
 466.9251927.723  495.111936.102  540.91 1947.31 572.6181956.928 580.6011960.424
#Mann= 3 , 0 , 0
       0      .1       0 263.006    .045       0  289.55      .1       0
#XS Ineff= 2 , 0
          256.33 1917.53   297.4         1917.67
Permanent Ineff=
       F       F
Bank Sta=263.006,289.55
XS Rating Curve= 0 ,0
Exp/Cntr(USF)=0,0
Exp/Cntr=0.3,0.1

Type RM Length L Ch R = 1 ,19010   ,336.9,338.1,338.5
XS GIS Cut Line= 4
2112494.89684863308233.9664120862112360.46154053308151.938088497
2112071.08384342308067.6312003632111758.92050087308001.552828583
#Sta/Elev= 30
       0 1962.86    41.7  1962.8    60.9 1960.96   90.111956.429   130.7 1949.95
  215.36 1924.48   252.8 1915.58  262.191912.106   276.7 1911.37   302.1 1912.48
   324.5 1914.15   355.2 1912.83   372.4 1910.08   375.8 1910.11     386 1915.18
   392.9 1916.86   424.1 1918.87  505.261919.336   541.1 1919.95   568.5 1922.26
   599.7 1931.23   616.3  1937.6  642.241949.904   649.5 1954.25   662.4 1958.76
   679.1 1968.04   709.3 1979.31   732.5  1986.5   750.2  1990.7777.9739 1994.95
#Mann= 7 ,-1 , 0
       0     .05       0   90.11      .1       0  215.36     .05       0
  262.19    .045       0   302.1     .05       0  505.26      .1       0
  642.24      .1       0
Bank Sta=262.19,302.1
XS Rating Curve= 0 ,0
Exp/Cntr(USF)=0,0
Exp/Cntr=0.3,0.1

Type RM Length L Ch R = 1 ,18672   ,477.2,479.5,473.1
XS GIS Cut Line= 4
2112690.85339943307935.4744568022112469.83263865307839.774745948
2112164.50498973307737.239341461 2111806.7703563307648.375324239
#Sta/Elev= 30
       0 1966.14    98.6 1959.25   138.4 1957.57   184.4 1950.55  213.051944.634
   248.4 1933.98  269.48 1929.44  335.961915.417   345.4    1913  360.881911.962
   373.1 1910.47  385.921911.962   403.9 1917.07   411.2    1918   593.9 1917.56
  621.59 1918.96   637.8 1921.58     648 1924.48   661.5 1930.48   670.3 1932.91
   705.5 1947.83   754.8 1975.14   783.2 1988.99     817 2007.49  838.97 2015.44
   847.4 2017.89   857.6 2023.33   871.1 2027.58   891.4 2031.48 931.541 2036.61
#Mann= 8 ,-1 , 0
       0     .05       0  213.05      .1       0  269.48      .1       0
  335.96     .05       0  360.88    .045       0  385.92     .05       0
  621.59      .1       0  838.97      .1       0
Bank Sta=360.88,385.92
XS Rating Curve= 0 ,0
Exp/Cntr(USF)=0,0
Exp/Cntr=0.3,0.1

Type RM Length L Ch R = 1 ,18193   ,466.6,458.5,454.7
XS GIS Cut Line= 3
2112902.75990203307561.7898715622112718.19617396307459.254467075
2112046.01963343307147.091124526
#Sta/Elev= 30
       0 1973.22    75.7 1967.43  118.841962.476   147.6 1958.87   199.6 1947.37
   243.4 1934.01   279.3 1919.79     294 1915.67   315.7  1912.5   341.2  1910.2
   355.5 1912.78   366.4  1910.6   377.2 1912.29   398.1 1916.44  436.631918.037
   458.5  1923.6   467.7 1927.95   511.1 1942.42   521.9  1947.4   549.9 1952.33
  576.271953.836   625.3 1960.44   670.2 1961.93   729.1 1970.68  767.861971.181
  788.591970.546   857.5 1967.39   905.4  1961.8   919.3 1962.27 952.259 1966.43
#Mann= 8 ,-1 , 0
       0     .05       0  118.84      .1       0   315.7    .045       0
   377.2     .05       0  436.63      .1       0  576.27     .05       0
  767.86      .1       0  788.59     .05       0
Bank Sta=315.7,377.2
XS Rating Curve= 0 ,0
Exp/Cntr(USF)=0,0
Exp/Cntr=0.3,0.1

Type RM Length L Ch R = 1 ,17734   ,387.7,409.7,424.1
XS GIS Cut Line= 4
2113107.83071101 307028.605768232112870.85999842306992.148735524
2112519.96105862306964.8059609942112109.81944067307039.998590951
#Sta/Elev= 30
       0 1981.23     8.9  1979.8    28.8 1980.41    42.1 1979.62    75.3 1974.16
  100.951971.013     145 1964.47   178.9 1958.28   194.8 1953.56     228  1941.7
  252.941929.876   287.3  1915.1  307.651909.605   323.5  1908.5   336.7 1908.68
  342.291909.605   370.5 1914.53   392.6  1914.6   418.9 1916.09   437.7 1918.48
   465.1 1923.38     488 1925.63   630.1 1926.13   720.1 1928.56   753.5 1930.83
     790 1936.37   840.2 1948.33   886.9 1956.73   990.3  1966.11008.699 1968.48
#Mann= 5 ,-1 , 0
       0     .05       0  100.95    .055       0  252.94     .05       0
  307.65    .045       0  342.29     .05       0
Bank Sta=307.65,342.29
XS Rating Curve= 0 ,0
Exp/Cntr(USF)=0,0
Exp/Cntr=0.3,0.1

Type RM Length L Ch R = 1 ,17324   ,73.8,66.3,87.4
XS GIS Cut Line= 4
2113138.28033295306917.6893974232112859.72057525306677.848370524
2112739.26230165306546.6348939242112155.25477875306243.338169325
#Sta/Elev= 30
       0 1986.49     109 1971.42   154.3 1971.12   194.5 1965.83   224.7 1959.44
     280 1943.41   307.2 1932.46   362.1 1917.81   370.2 1916.62   392.3 1917.02
   414.7 1913.35   457.3 1909.37   484.3 1908.32   506.1 1909.78   513.4 1912.58
   554.3 1919.45   569.1 1920.11   602.4 1927.02   669.6 1924.68   749.2  1918.6
   808.3 1922.81   864.9 1937.71   890.8 1945.67   916.6 1955.62   961.6 1967.06
   998.1 1973.41  1041.9 1978.66  1086.7 1988.59    1149 1992.73  1203.8 2000.93
#Mann= 3 , 0 , 0
       0     .05       0   457.3    .045       0   506.1     .05       0
#XS Ineff= 2 , 0
                           604.9         1927.38
Permanent Ineff=
       F       F
Bank Sta=457.3,506.1
XS Rating Curve= 0 ,0
Exp/Cntr(USF)=0,0
Exp/Cntr=0.3,0.1

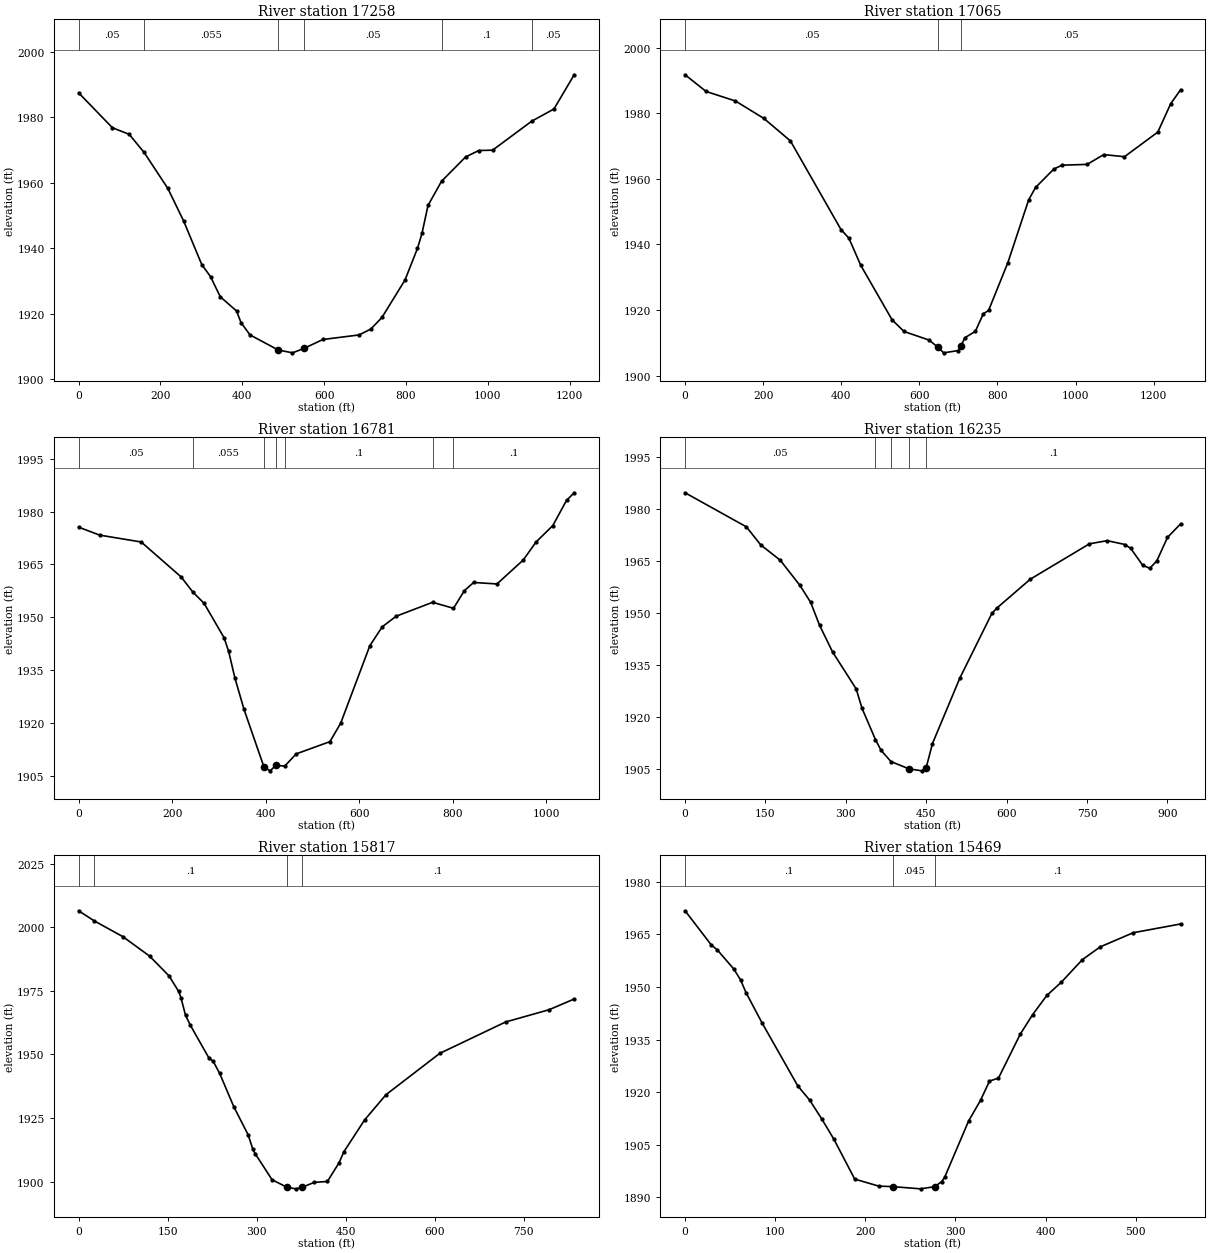
Type RM Length L Ch R = 1 ,17258   ,198.3,193,162.7
XS GIS Cut Line= 4
2113156.40114663306873.1729805632112887.95739136306649.479429751
2112708.96769164306410.6226448712112205.66687776306157.897793291
#Sta/Elev= 30
       01987.527  82.5931976.857 123.5931974.857  160.071969.316 218.0331958.324
 256.8411948.328 301.0011935.058 322.3541931.386 346.1541925.246 385.8671920.905
 396.8091917.376 418.693  1913.6   487.71908.992 522.6431908.115   550.61909.454
 596.898 1912.19 685.4171913.584 714.3721915.401 741.3531918.932 797.5651930.336
  828.181940.031 839.1931944.617 853.8781953.125 886.919 1960.51 945.659 1967.93
 977.8661969.9061011.7411970.0141107.1931978.8571161.7211982.5931211.097 1993.04
#Mann= 6 ,-1 , 0
       0     .05       0  160.07    .055       0   487.7    .045       0
   550.6     .05       0 886.919      .1       01107.193     .05       0
Bank Sta=487.7,550.6
XS Rating Curve= 0 ,0
Exp/Cntr(USF)=0,0
Exp/Cntr=0.3,0.1

Type RM Length L Ch R = 1 ,17065   ,282.6,284.5,278.1
XS GIS Cut Line= 4
2113394.33383252306616.7561618782113035.82706586  306398.9964962
2112679.97590487306308.7059031132112235.16195364306121.485702743
#Sta/Elev= 30
       0 1991.73    53.8 1986.64   128.9 1983.74     202  1978.4   269.8 1971.55
   399.2 1944.54   419.5  1941.9     450  1933.6   530.2 1916.99   560.7 1913.44
     625 1910.82   646.9  1908.7   662.3 1906.93   699.5 1907.62   706.5 1909.06
   716.4 1911.51   743.5  1913.5   763.8 1918.84   777.3 1919.86   826.7 1934.44
     880  1953.6   897.6 1957.36   944.2 1962.96   965.5 1964.16  1029.6  1964.4
  1072.3 1967.39  1125.4 1966.74  1210.8 1974.26  1243.8 1982.92  1269.2 1987.18
#Mann= 3 , 0 , 0
       0     .05       0   646.9    .045       0   706.5     .05       0
Bank Sta=646.9,706.5
XS Rating Curve= 0 ,0
Exp/Cntr(USF)=0,0
Exp/Cntr=0.3,0.1

Type RM Length L Ch R = 1 ,16781   ,536.5,545.3,552.7
XS GIS Cut Line= 4
2113278.72305182306087.5586114962112998.45961289 306078.44435332
2112658.95349581306080.7229178642112223.74766788306016.923110628
#Sta/Elev= 30
       0 1975.56    45.2  1973.3   133.8 1971.36   219.2 1961.45  244.191957.159
   268.4 1953.94   311.1 1944.17   320.8 1940.34     334 1932.88   353.7 1923.87
  396.251907.551   409.5 1906.43     422    1908  440.791907.769   465.3 1911.24
   537.4 1914.71   560.4 1919.93   622.8 1941.93   649.3 1947.29   679.1  1950.3
  757.051954.245  801.691952.545     825 1957.56   844.9 1959.88   894.7 1959.45
   950.9 1966.25   978.5 1971.39  1014.1 1976.01  1043.4 1983.161059.783 1985.32
#Mann= 7 ,-1 , 0
       0     .05       0  244.19    .055       0  396.25    .045       0
     422    .055       0  440.79      .1       0  757.05     .05       0
  801.69      .1       0
Bank Sta=396.25,422
XS Rating Curve= 0 ,0
Exp/Cntr(USF)=0,0
Exp/Cntr=0.3,0.1

Type RM Length L Ch R = 1 ,16235   ,432.5,418.4,400.4
XS GIS Cut Line= 4
2113326.57290725305707.0383326232113012.13100015305652.352783563
2112827.56727208305533.8674272682112444.76842866305483.739007296
#Sta/Elev= 30
       0 1984.64   114.4 1974.81     141 1969.62   177.7 1965.16   214.3 1957.92
   234.3 1953.02   250.9 1946.42   275.2 1938.71   319.2 1928.08   329.9 1922.55
  355.111913.465   365.5 1910.38     3841907.121  417.451905.027   441.5 1904.44
   449.8 1905.36   461.5  1912.3   512.7 1931.22   572.4 1949.85   581.7 1951.39
   644.2 1959.73   754.4 1969.92   787.6 1970.83   820.6 1969.72   831.5 1968.58
   853.7 1963.75   866.9 1962.85   880.1 1964.99     900 1971.77924.5518 1975.68
#Mann= 5 ,-1 , 0
       0     .05       0  355.11      .1       0     384      .1       0
  417.45    .045       0   449.8      .1       0
Bank Sta=417.45,449.8
XS Rating Curve= 0 ,0
Exp/Cntr(USF)=0,0
Exp/Cntr=0.3,0.1

Type RM Length L Ch R = 1 ,15817   ,357.8,347.7,332.1
XS GIS Cut Line= 3
2113290.11587454 305018.911840292113087.32363011305148.790019306
2112590.59655949 305474.62474912
#Sta/Elev= 30
       0 2006.49    26.62002.473    74.3 1996.35   119.5 1988.67   152.5 1980.83
   168.5 1974.76   172.4 1972.33   180.1 1965.35   188.3 1961.45   219.2 1948.71
   226.9 1947.22   237.6 1942.53   261.6 1929.33   285.6 1918.38   293.5 1912.69
   297.4 1910.98   325.9 1900.71  350.711897.777   366.2 1897.13  376.871897.777
     397 1899.68   419.1 1900.02   438.7 1907.35     447 1911.75   481.8 1924.23
   517.8 1934.15   608.5 1950.42   719.2 1962.74   792.7 1967.58834.8764 1971.79
#Mann= 4 ,-1 , 0
       0     .05       0    26.6      .1       0  350.71    .045       0
  376.87      .1       0
Bank Sta=350.71,376.87
XS Rating Curve= 0 ,0
Exp/Cntr(USF)=0,0
Exp/Cntr=0.3,0.1

Type RM Length L Ch R = 1 ,15469   ,367.2,366.6,364.2
XS GIS Cut Line= 3
2112738.73841678304857.7511748312112686.29627034 304991.56906576
 2112622.4964631 305392.59642553
#Sta/Elev= 30
       0 1971.75    28.8 1962.09    35.9 1960.54    54.1 1955.13    61.7 1951.94
    67.6 1948.41    85.2 1939.86     125 1921.82   138.1 1917.79   151.7 1912.35
     165 1906.64   188.2 1895.23   214.8 1893.23   230.31893.083   261.3 1892.45
     2771893.071   284.6 1894.48   287.9  1895.7   314.5 1911.78   327.8  1917.7
   337.7 1923.18   347.7 1924.03   371.8 1936.53   385.5  1942.1   401.3 1947.59
   417.5  1951.4   440.7  1957.8   460.6 1961.46   497.2 1965.49   549.8 1967.99
#Mann= 3 , 0 , 0
       0      .1       0   230.3    .045       0     277      .1       0
Bank Sta=230.3,277
XS Rating Curve= 0 ,0
Exp/Cntr(USF)=0,0
Exp/Cntr=0.3,0.1

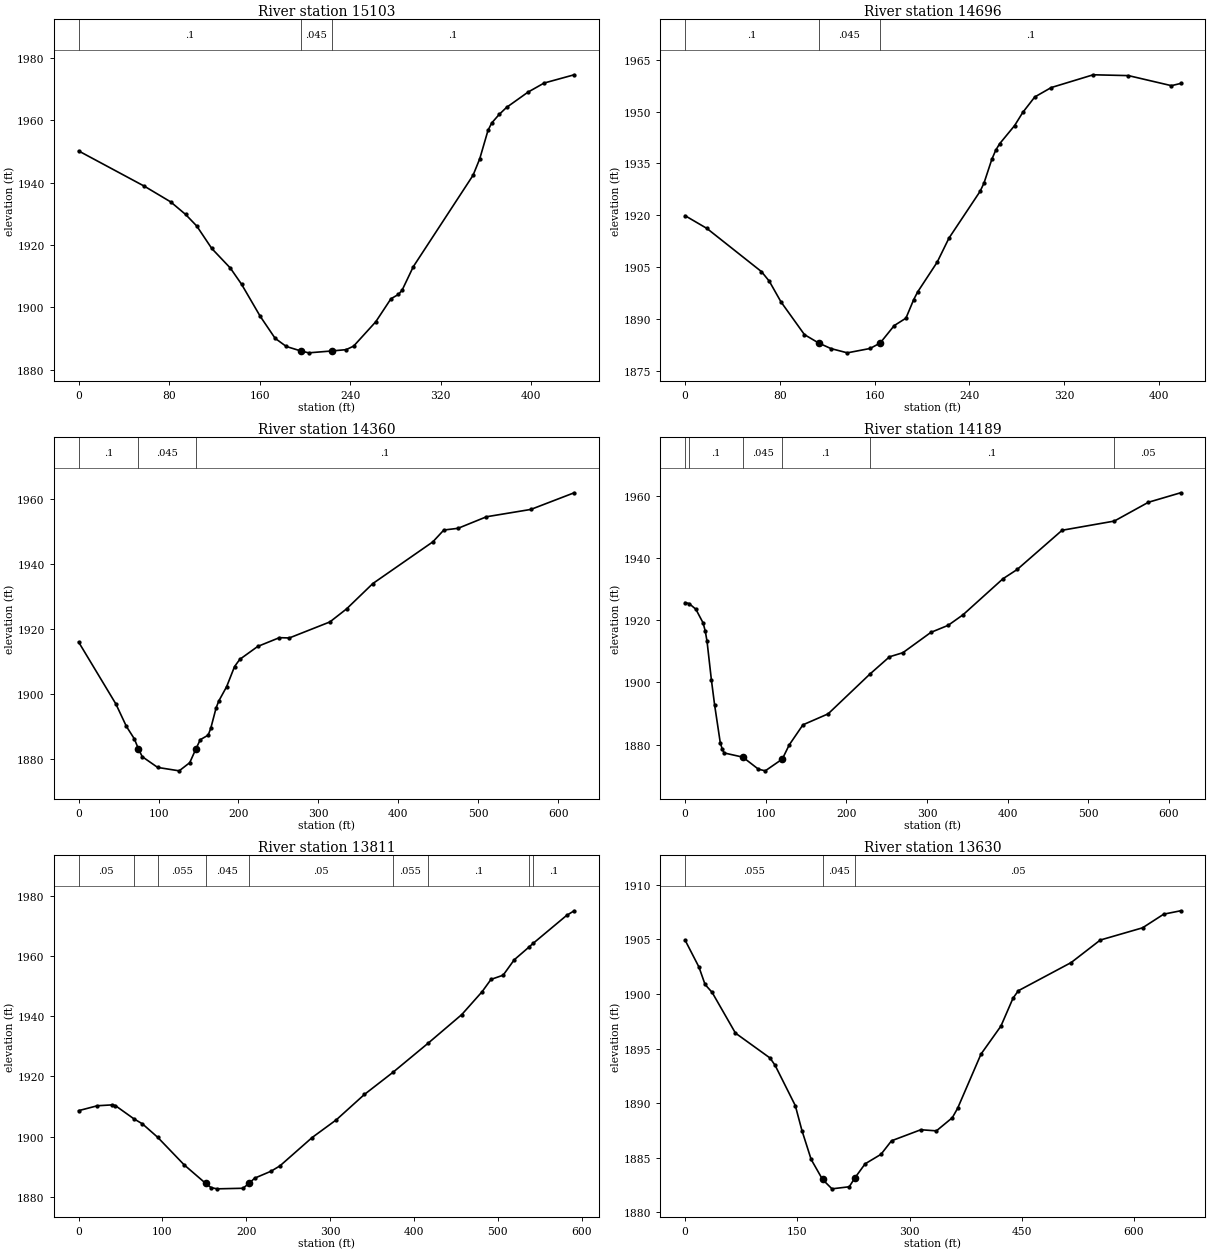
Type RM Length L Ch R = 1 ,15103   ,407.4,406.8,406.2
XS GIS Cut Line= 3
 2112328.7635212 304866.288250472112324.00450782304902.705048538
2112278.43321694305301.453843764
#Sta/Elev= 30
       0 1950.15    58.1 1938.85    81.3 1933.84    94.5 1929.82   104.4  1926.1
   117.7 1918.89   134.1 1912.62     144 1907.45   160.5 1897.17   173.7  1890.1
   183.6 1887.48   196.51886.039   203.4 1885.44   223.61886.034   236.5 1886.46
   243.1 1887.59   262.7  1895.4   276.1 1902.77   282.7 1904.15     286 1905.54
   295.9 1913.07   348.7 1942.35   354.6 1947.62   361.9 1956.72   365.2 1959.11
   371.8 1961.85   378.3  1964.1   397.3    1969   411.5 1971.91   438.1 1974.56
#Mann= 3 , 0 , 0
       0      .1       0   196.5    .045       0   223.6      .1       0
Bank Sta=196.5,223.6
XS Rating Curve= 0 ,0
Exp/Cntr(USF)=0,0
Exp/Cntr=0.3,0.1

Type RM Length L Ch R = 1 ,14696   ,335.5,335.7,332.5
XS GIS Cut Line= 3
2111916.54536226304882.7801192522111916.14145442304884.476532185
2111875.12729262 305299.17527922
#Sta/Elev= 30
       0 1919.89    18.4 1916.21    64.5 1903.71    71.1 1900.94      81 1894.94
   100.8 1885.48   112.71883.072   123.2 1881.44     137 1880.21   156.2 1881.47
   164.71883.034   176.6 1888.09   186.5 1890.24   193.1 1895.64   196.4 1897.83
   212.9 1906.45   222.8 1913.38   249.1 1926.92   252.4  1929.3     259 1936.16
   262.3 1938.81   265.6 1940.69   278.3 1945.97   285.2 1949.78   295.3 1954.24
   309.2 1956.96   344.7 1960.66   374.4 1960.42   410.7 1957.51   418.5 1958.15
#Mann= 3 , 0 , 0
       0      .1       0   112.7    .045       0   164.7      .1       0
Bank Sta=112.7,164.7
XS Rating Curve= 0 ,0
Exp/Cntr(USF)=0,0
Exp/Cntr=0.3,0.1

Type RM Length L Ch R = 1 ,14360   ,195.6,170.9,149.9
XS GIS Cut Line= 3
2111593.40582646 304825.133335592111565.24251462305087.268776614
2111704.23495181305415.382070972
#Sta/Elev= 30
       0 1915.99    46.6 1896.92    59.8 1889.99    69.7 1886.17    74.91883.022
    79.6 1880.67    98.9 1877.36   125.8 1876.31     139 1878.82   146.71883.053
   152.2 1885.91   162.1 1887.31   165.4 1889.49     172  1895.7   175.3 1897.81
   185.2 1902.26   195.1 1908.46   201.7 1910.68   224.1 1914.65   251.2 1917.35
   263.6 1917.26   314.3 1922.19   335.2 1926.21   368.1 1934.03   443.2 1946.88
   456.9 1950.52   474.7 1951.05   510.3 1954.61   565.8 1956.87     620    1962
#Mann= 3 , 0 , 0
       0      .1       0    74.9    .045       0   146.7      .1       0
Bank Sta=74.9,146.7
XS Rating Curve= 0 ,0
Exp/Cntr(USF)=0,0
Exp/Cntr=0.3,0.1

Type RM Length L Ch R = 1 ,14189   ,387.8,377.9,407.2
XS GIS Cut Line= 3
2111362.45027019 304909.540742172111531.06404646305114.611551144
2111672.33504819305433.610587325
#Sta/Elev= 30
       0 1925.61    4.891925.316    13.3  1923.5    22.3 1919.09      25 1916.45
    27.2 1913.17    32.6 1900.77    36.6 1892.71    43.6 1880.59      46 1878.57
    48.4 1877.29    71.6 1875.94    90.9 1872.07    99.4 1871.54   120.5 1875.32
   129.1 1879.88   146.1 1886.33   177.3 1889.85  228.961902.596   253.4 1908.19
     270 1909.51   304.8 1916.05   326.1  1918.3   344.6  1921.7   394.1 1933.28
   411.8 1936.27   467.4 1948.86  532.141951.817   574.4 1957.86614.3704 1960.91
#Mann= 6 ,-1 , 0
       0    .055       0    4.89      .1       0    71.6    .045       0
   120.5      .1       0  228.96      .1       0  532.14     .05       0
Bank Sta=71.6,120.5
XS Rating Curve= 0 ,0
Exp/Cntr(USF)=0,0
Exp/Cntr=0.3,0.1

Type RM Length L Ch R = 1 ,13811   ,168,180.9,206.7
XS GIS Cut Line= 3
2111294.09333386305192.082745645 2111414.8572547 305474.62474912
2111622.20662822305668.302735373
#Sta/Elev= 30
       0 1908.62    22.4 1910.25    40.3 1910.54    43.8  1910.3   65.891905.906
    76.1 1904.22   94.171899.787   125.9 1890.58   151.5 1884.43     158 1883.01
   165.1 1882.61     196  1882.8   203.5 1884.49   209.9 1886.16   229.4 1888.46
   240.1 1890.25   278.5 1899.68   307.3 1905.56   340.9 1914.02  374.651921.316
  416.581930.994     457 1940.59   481.1 1948.15   491.8 1952.27   506.3 1953.68
   519.5 1958.79  536.941962.986  541.991964.245     582 1973.56591.0024  1975.1
#Mann= 9 ,-1 , 0
       0     .05       0   65.89      .1       0   94.17    .055       0
   151.5    .045       0   203.5     .05       0  374.65    .055       0
  416.58      .1       0  536.94     .05       0  541.99      .1       0
Bank Sta=151.5,203.5
XS Rating Curve= 0 ,0
Exp/Cntr(USF)=0,0
Exp/Cntr=0.3,0.1

Type RM Length L Ch R = 1 ,13630   ,64.2,64.6,65.8
XS GIS Cut Line= 3
2111266.01800751305100.335238038 2111215.0187215305231.476259224
2111021.94999586305715.969476381
#Sta/Elev= 30
       0 1904.93    18.5 1902.47    26.7 1900.87    36.1 1900.15    67.3 1896.42
   113.5 1894.14   120.3 1893.47   147.3 1889.78   156.2 1887.49   168.5 1884.85
   183.7 1883.02   196.3 1882.16   219.4 1882.35   226.9 1883.16   240.6 1884.45
   261.8 1885.32   275.9 1886.56     315 1887.57   335.9 1887.47   357.1 1888.67
   364.2 1889.53   395.5  1894.5   422.1 1897.06   438.3 1899.62   445.4  1900.3
     516 1902.88   554.9 1904.94   611.4 1906.06   639.7 1907.31   662.3 1907.62
#Mann= 3 , 0 , 0
       0    .055       0   183.7    .045       0   226.9     .05       0
Bank Sta=183.7,226.9
XS Rating Curve= 0 ,0
Exp/Cntr(USF)=0,0
Exp/Cntr=0.3,0.1