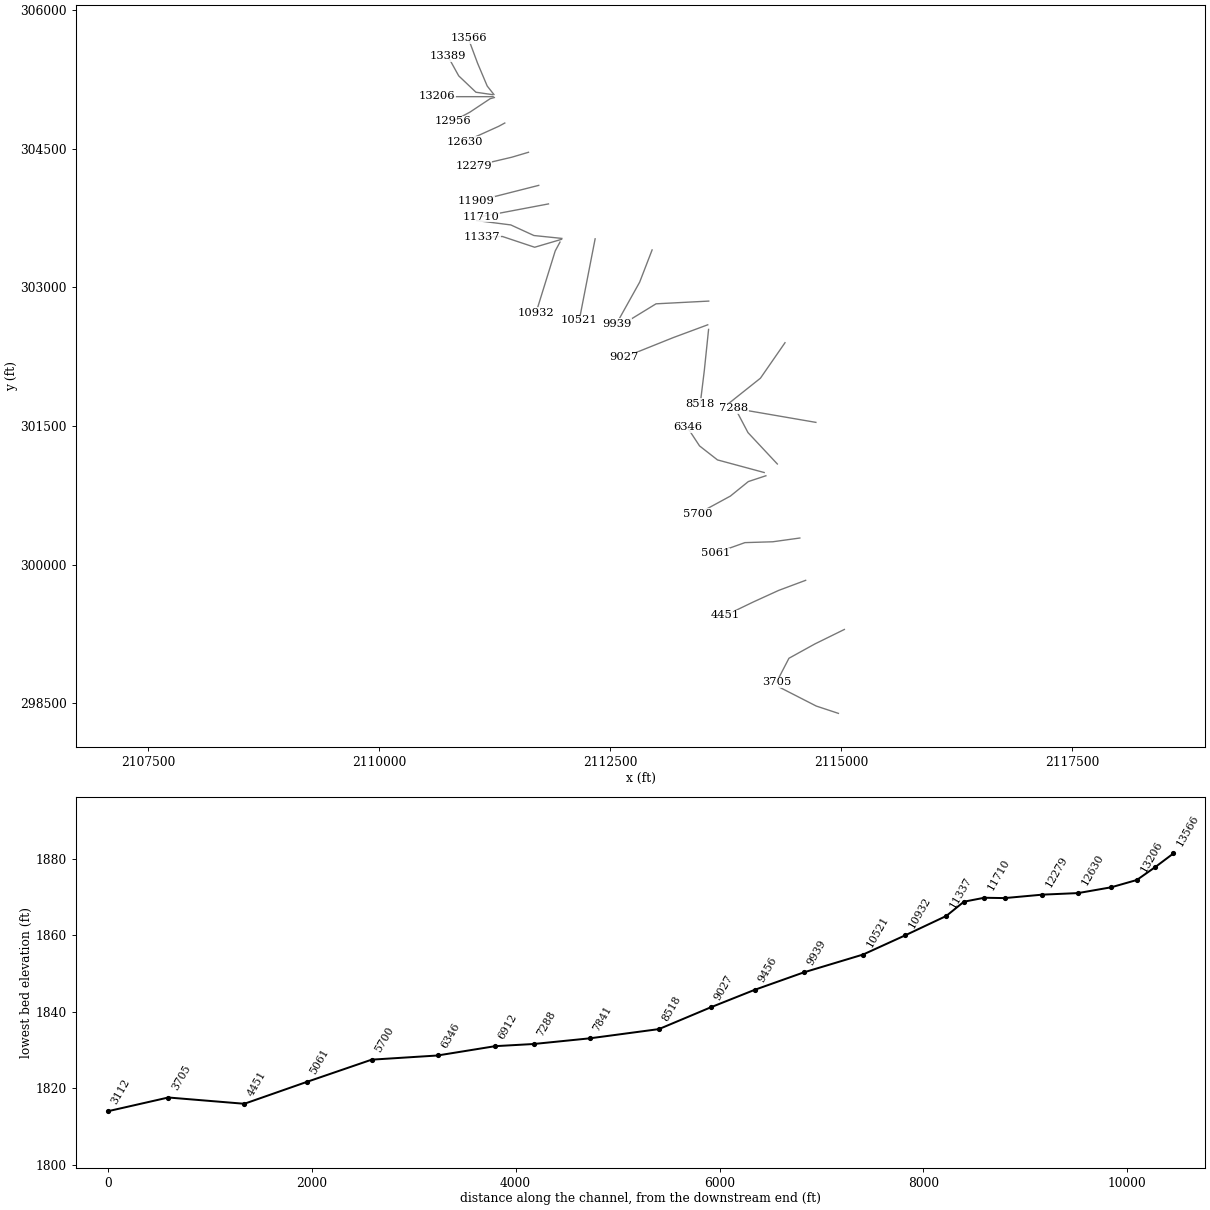
HEC-RAS study MLGNCK.prj: MLGNCK

--- MLGNCK.g01 (geometry) --- (continued)

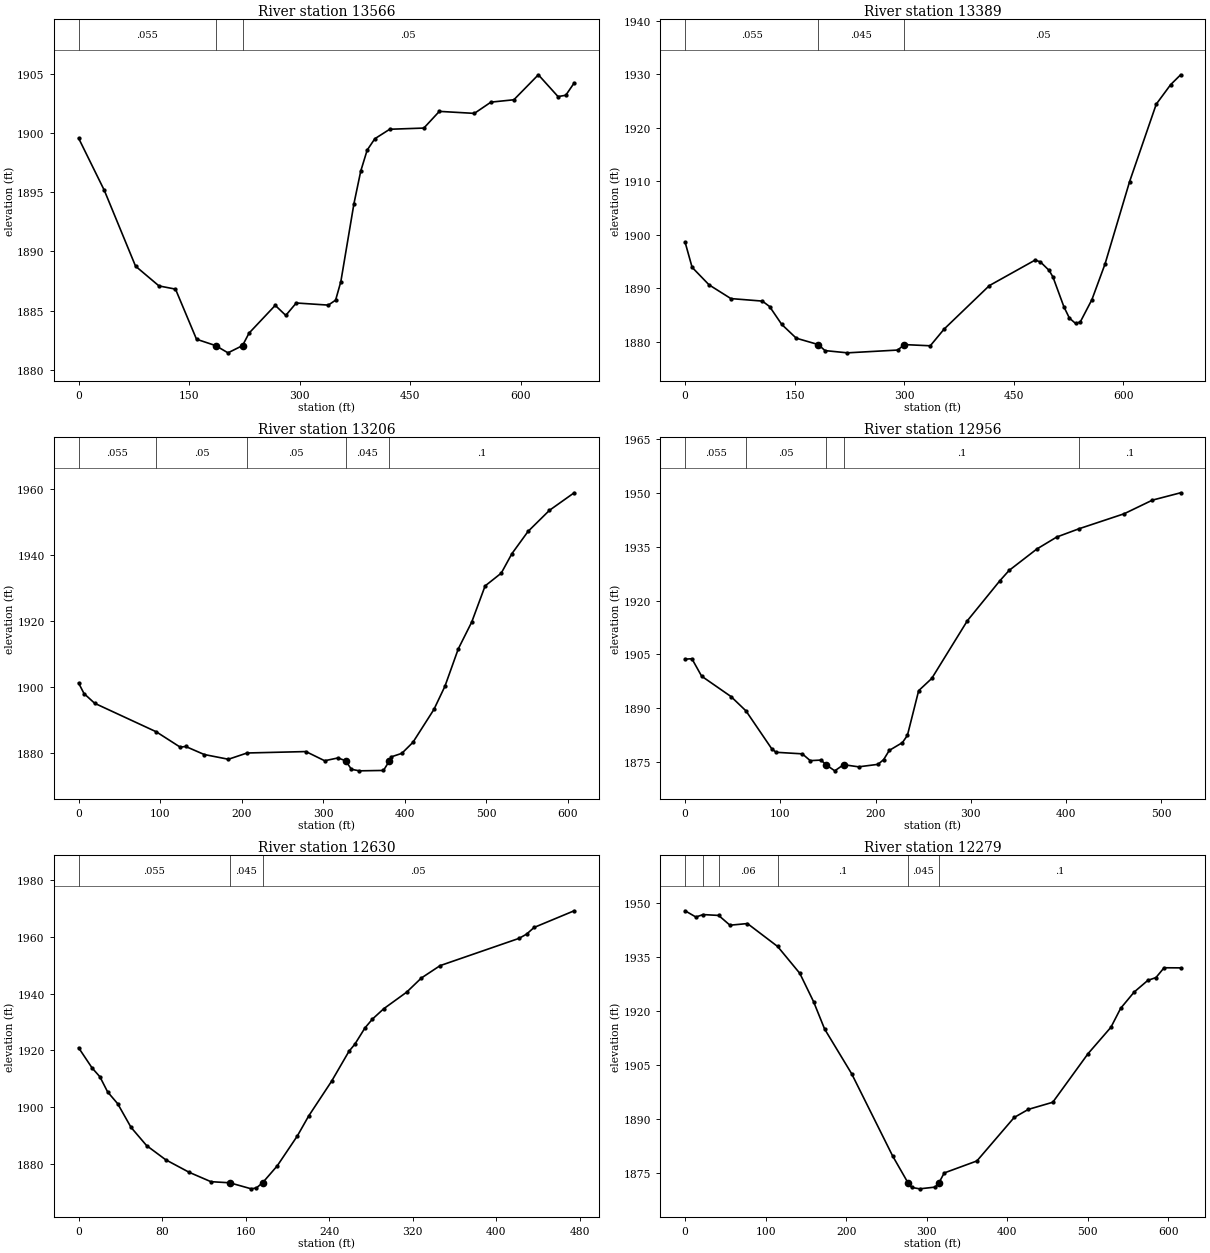
Type RM Length L Ch R = 1 ,13566   ,163.2,176.4,186.8
XS GIS Cut Line= 4
2111240.74743144305087.9178845232111168.14981119305179.874870172
2111063.60923803305427.6747472922110963.90850622305695.801958081
#Sta/Elev= 30
       0 1899.56    34.9 1895.15    77.2 1888.76     109 1887.09   131.4 1886.82
   159.9 1882.59   185.9 1882.05   202.6 1881.44   222.3 1882.05   231.1  1883.1
   266.7 1885.45     281  1884.6   295.2 1885.65   338.7 1885.47   348.6 1885.89
   355.7 1887.46   373.5 1894.05   382.7 1896.79   391.4 1898.56   401.8 1899.52
     422 1900.32   468.3 1900.42   489.3 1901.83   536.8 1901.66   559.3 1902.61
   590.4 1902.81   623.6 1904.92   650.3 1903.08   660.8 1903.19   672.2 1904.23
#Mann= 3 , 0 , 0
       0    .055       0   185.9    .045       0   222.3     .05       0
Bank Sta=185.9,222.3
XS Rating Curve= 0 ,0
Exp/Cntr(USF)=0,0
Exp/Cntr=0.3,0.1

Type RM Length L Ch R = 1 ,13389   ,161.4,183,195.2
XS GIS Cut Line= 4
2111225.37806552305086.5155060282111046.37068357305112.625321874
2110859.96131821305289.8065008272110743.68616952305500.209150834
#Sta/Elev= 30
       0 1898.61     9.6 1893.91    32.8 1890.63    62.7 1888.06   105.8 1887.59
   115.7 1886.57   132.3 1883.23   152.2 1880.65   182.5 1879.45   191.5 1878.33
   222.3 1877.91   291.1 1878.43   300.21879.454   335.7 1879.23   354.7 1882.36
   416.6 1890.49   479.2 1895.26   486.4 1894.93   498.5 1893.32   503.7 1892.09
   518.7 1886.51   526.2 1884.41   534.7  1883.4   541.1 1883.69     557 1887.86
   574.9  1894.5   608.6 1909.94   645.1 1924.43   664.8 1928.08   678.5 1929.93
#Mann= 3 , 0 , 0
       0    .055       0   182.5    .045       0   300.2     .05       0
#XS Ineff= 2 , 0
                          477.84         1894.97
Permanent Ineff=
       F       F
Bank Sta=182.5,300.2
XS Rating Curve= 0 ,0
Exp/Cntr(USF)=0,0
Exp/Cntr=0.3,0.1

Type RM Length L Ch R = 1 ,13206   ,233.4,250.7,285.9
XS GIS Cut Line= 4
2111232.30081535305064.6084978812110966.45240722305064.608497881
2110759.94516162305064.6084978812110624.64731106305075.289907136
#Sta/Elev= 30
       0 1901.08     6.6 1897.91    19.7 1894.96    95.2 1886.33   124.7 1881.66
   131.3 1881.88   154.2 1879.43   183.8    1878   206.7  1879.9   278.9 1880.33
   301.9 1877.55   318.3  1878.4   327.7 1877.53   334.7 1874.96   344.5 1874.49
   374.1 1874.61   381.1  1877.4   383.9 1878.75   396.6 1879.79   410.2 1883.12
     436  1893.1   449.5 1900.12   465.9 1911.46   482.4 1919.59   498.8 1930.53
   518.6  1934.4   531.7 1940.31   551.5 1947.05   577.8 1953.45   608.1 1958.76
#Mann= 5 ,-1 , 0
       0    .055       0    95.2     .05       0   206.7     .05       0
   327.7    .045       0   381.1      .1       0
Bank Sta=327.7,381.1
XS Rating Curve= 0 ,0
Exp/Cntr(USF)=0,0
Exp/Cntr=0.3,0.1

Type RM Length L Ch R = 1 ,12956   ,325.5,325.4,324.1
XS GIS Cut Line= 4
2111245.69950989 305055.410566172111200.27487168305042.747924844
2110981.11935469304897.0685944922110796.01324745304798.348554886
#Sta/Elev= 30
       01903.696   7.1481903.804  17.3661898.949  48.2321893.267  63.9131889.277
  90.8291878.772  95.4291877.755 123.0061877.319  131.321875.427 142.7041875.584
 147.6241874.339  157.091872.586 166.3411874.301 182.0991873.702 202.4391874.395
 208.3651875.709 214.2921878.272 228.0851880.451 233.3141882.454 245.1321894.914
 258.8491898.314 296.3461914.432 330.3261925.517 340.0261928.398 369.1261934.358
 390.087 1937.71 413.4851940.014 460.734 1944.18  490.481947.984 520.0991950.031
#Mann= 5 ,-1 , 0
       0    .055       0  63.913     .05       0 147.624    .045       0
 166.341      .1       0 413.485      .1       0
Bank Sta=147.624,166.341
XS Rating Curve= 0 ,0
Exp/Cntr(USF)=0,0
Exp/Cntr=0.3,0.1

Type RM Length L Ch R = 1 ,12630   ,353.2,350.9,346.3
XS GIS Cut Line= 3
2111358.44649483304779.5306484512111291.84044191304743.497865721
 2110928.2498976304579.236147733
#Sta/Elev= 30
       0 1920.88    12.9 1913.76    20.4 1910.63    27.8 1905.28    37.4 1901.14
    50.2 1892.78    65.1 1886.35    83.4 1881.34   105.9 1876.91   126.7  1873.6
   144.81873.205   165.4 1871.07   170.3 1871.39   176.21873.211   190.2 1879.16
   209.5 1889.74   220.3 1896.76   242.3 1909.06   258.9  1919.6   264.6 1922.15
   274.3 1927.91   281.5 1931.04   292.3 1934.68   314.2 1940.52   328.3 1945.52
   346.3  1949.9   421.9 1959.53   429.1 1961.02   436.3 1963.38   474.7 1969.27
#Mann= 3 , 0 , 0
       0    .055       0   144.8    .045       0   176.2     .05       0
Bank Sta=144.8,176.2
XS Rating Curve= 0 ,0
Exp/Cntr(USF)=0,0
Exp/Cntr=0.3,0.1

Type RM Length L Ch R = 1 ,12279   ,369.3,369.9,370
XS GIS Cut Line= 3
2111614.82696604304462.9609990452111433.95451253304409.437517903
2111018.68612435304311.618742023
#Sta/Elev= 30
       0 1947.71    13.4 1945.98   22.411946.657   41.67 1946.42    55.7 1943.71
    77.4 1944.17  114.921937.812   142.4 1930.38   159.5 1922.53   173.2 1914.95
   206.8 1902.55   257.7 1879.76  276.741872.333   281.2 1871.06   291.2 1870.66
   310.4 1871.14  315.181872.334   321.7 1875.06   362.3 1878.39   408.6 1890.44
   426.2 1892.68   456.5 1894.65   500.3 1908.12   528.7 1915.43   540.8 1920.69
   557.6  1925.2   574.5 1928.42   584.6  1929.2   594.7 1931.92615.2593 1931.89
#Mann= 6 ,-1 , 0
       0     .05       0   22.41    .055       0   41.67     .06       0
  114.92      .1       0  276.74    .045       0  315.18      .1       0
Bank Sta=276.74,315.18
XS Rating Curve= 0 ,0
Exp/Cntr(USF)=0,0
Exp/Cntr=0.3,0.1

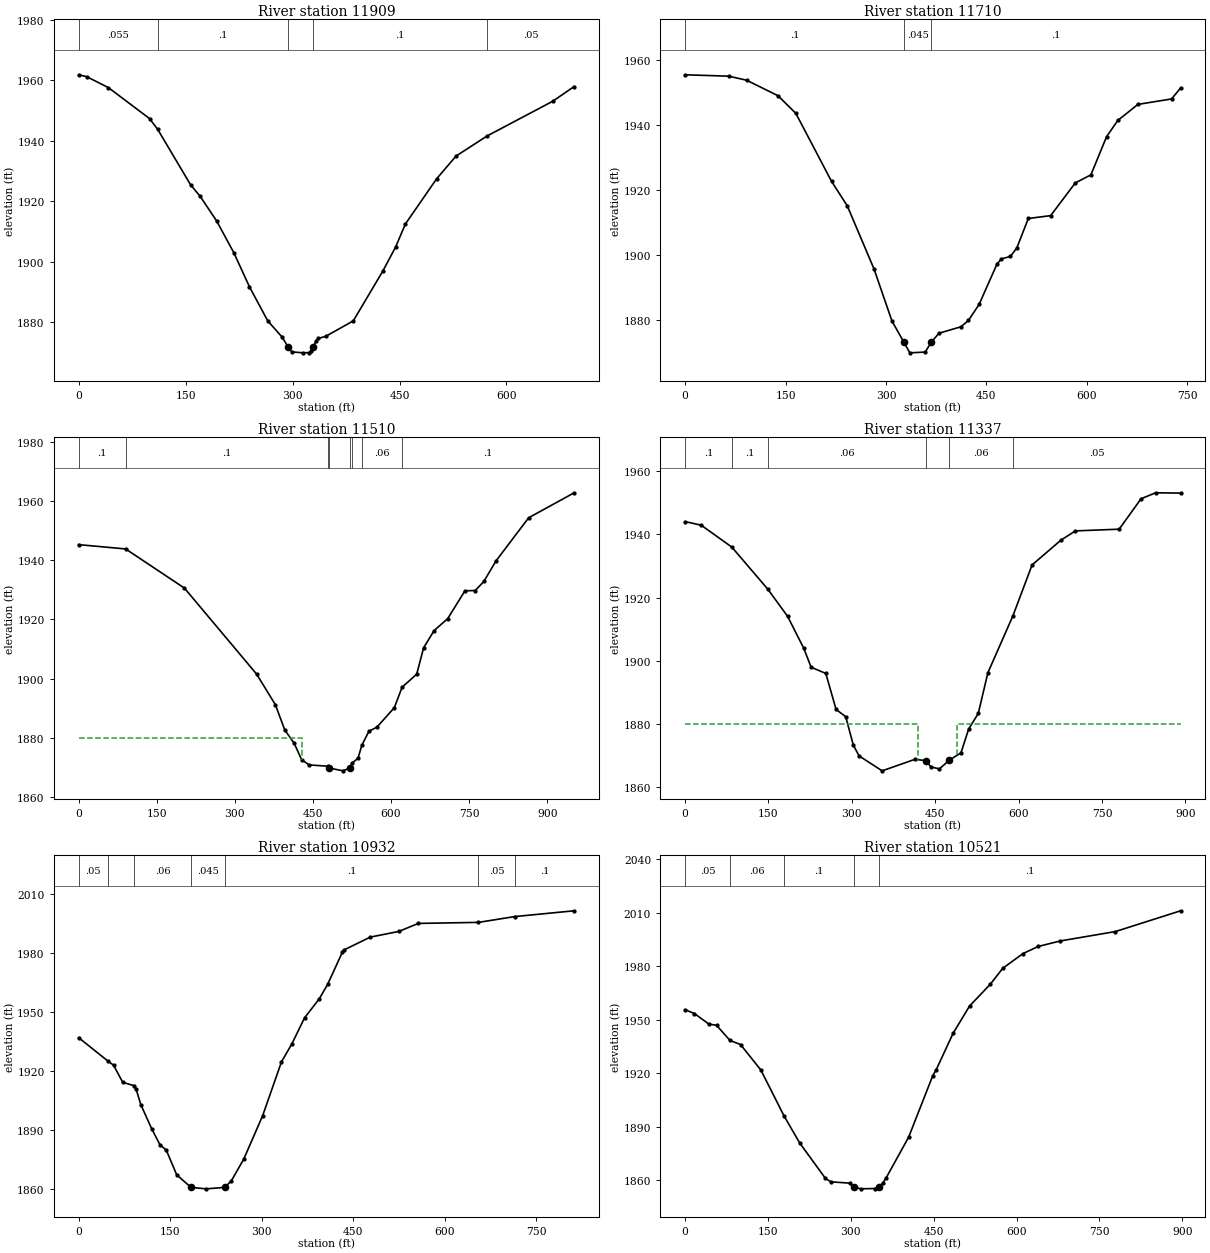
Type RM Length L Ch R = 1 ,11909   ,201.5,199.1,198.4
XS GIS Cut Line= 2
2111725.56520289304104.907366577 2111051.9802622303933.863555575
#Sta/Elev= 30
       0 1961.86    11.4 1961.22    41.8  1957.6    99.4 1947.36  110.781943.823
   156.9 1925.46   170.5 1921.58   193.6 1913.42   217.9 1902.81   239.5 1891.66
   265.3 1880.32   285.6 1874.92  293.731871.674   299.1 1870.08   315.1 1869.76
   323.2 1869.85   326.2 1870.27  329.121871.675     333 1873.73   336.3 1874.54
   346.5 1875.22   385.2 1880.35   426.6 1896.84   444.7 1904.88   458.2 1912.42
   502.2 1927.45   529.3 1934.94  573.121941.634   664.7 1953.06694.9623 1957.97
#Mann= 5 ,-1 , 0
       0    .055       0  110.78      .1       0  293.73    .045       0
  329.12      .1       0  573.12     .05       0
Bank Sta=293.73,329.12
XS Rating Curve= 0 ,0
Exp/Cntr(USF)=0,0
Exp/Cntr=0.3,0.1

Type RM Length L Ch R = 1 ,11710   ,210.2,200,186.3
XS GIS Cut Line= 2
2111831.08813276 303904.262975142111103.90790608303766.786116363
#Sta/Elev= 30
       0 1955.55    65.2 1955.12    91.9 1953.87   138.7  1949.1   165.4 1943.66
   218.8 1922.67   242.2 1915.16   282.2 1895.68   308.9 1879.69   326.7 1873.13
   335.7 1869.85   358.6 1870.09   367.8 1873.15   379.1 1875.88     412 1877.89
   423.2 1879.83   439.2 1884.81   465.9 1897.25   472.5 1898.82   485.9 1899.56
   495.5 1902.21   512.6 1911.26     546 1912.14   582.7 1922.21   606.1 1924.72
   629.5 1936.48   646.2 1941.46   676.2 1946.42   726.5  1948.1   740.1 1951.49
#Mann= 3 , 0 , 0
       0      .1       0   326.7    .045       0   367.8      .1       0
Bank Sta=326.7,367.8
XS Rating Curve= 0 ,0
Exp/Cntr(USF)=0,0
Exp/Cntr=0.5,0.3

Type RM Length L Ch R = 1 ,11510   ,169,173.4,170.1
XS GIS Cut Line= 4
2111975.76957594303531.0080653732111673.62795829303562.264094785
2111423.57972299303676.8695359632111053.65798129303724.231716767
#Sta/Elev= 30
       01945.219   90.281943.765 203.2591930.529 341.7631901.503 377.8531891.153
 395.8981882.644 413.9431878.129  428.381872.583 442.8161870.814  478.431870.387
  481.651869.749 507.7781868.817  520.441869.754 525.8231871.508  536.65 1873.09
 543.868 1877.43 557.6221882.215  572.74 1883.54 606.3241890.146  621.291897.068
 649.3231901.471 662.5531910.356 682.721 1916.19  708.861920.225 741.9361929.621
 761.7821929.726  778.321932.793 801.4731939.688 864.3181954.288 951.7561962.735
#Mann= 8 ,-1 , 0
       0      .1       0   90.28      .1       0  478.43    .045       0
  481.65    .045       0  520.44    .045       0 525.823      .1       0
 543.868     .06       0  621.29      .1       0
#XS Ineff= 2 , 0
          429.81    1880  571.92            1880
Permanent Ineff=
       F       F
Bank Sta=481.65,520.44
XS Rating Curve= 0 ,0
Exp/Cntr(USF)=0,0
Exp/Cntr=0.5,0.3

Type RM Length L Ch R = 1 ,11337   ,385,404.7,444
XS GIS Cut Line= 4
2111971.96270656303520.8656149272111681.65867136303435.394478112
2111332.62460854303551.7447664142111111.89185243303545.347047176
#Sta/Elev= 30
       01944.073  28.9481942.935  84.0071935.998 148.6511922.682  184.41 1914.04
 213.633 1903.86 226.6841897.921 253.1061895.949 271.6011884.537 288.8741882.249
 302.6251873.231 312.9291869.831 354.4281865.085  413.221868.724  433.971868.317
 441.9081866.338 457.4711865.713  475.471868.485  496.221870.786 510.0531878.329
 527.3441883.269 544.6361896.165  589.751914.243 624.1771930.346 675.7711938.152
 702.0291941.124 780.8021941.669 820.1891951.314 846.4461953.204 891.3661953.094
#Mann= 6 ,-1 , 0
       0      .1       0  84.007      .1       0 148.651     .06       0
  433.97    .045       0  475.47     .06       0  589.75     .05       0
#XS Ineff= 2 , 0
          419.41    1880  488.73            1880
Permanent Ineff=
       F       F
Bank Sta=433.97,475.47
XS Rating Curve= 0 ,0
Exp/Cntr(USF)=0,0
Exp/Cntr=0.5,0.3

Type RM Length L Ch R = 1 ,10932   ,408,410.7,413.6
XS GIS Cut Line= 3
2111955.71943351303491.3735228952111904.04158965303395.400384295
2111695.48457692302723.588414098
#Sta/Elev= 30
       0 1936.79   47.841924.941    57.2 1922.81    72.3  1914.1   90.651912.418
    94.4 1910.52   101.9 1902.81   119.6 1890.62   133.4 1882.35   143.7 1879.68
   160.8 1867.11  184.311860.728   208.9    1860  239.521860.728   250.2 1863.97
   270.8 1875.15   301.7 1897.16   332.6 1924.52   349.8 1933.74   370.4 1946.86
   394.6 1956.53   408.2 1963.81   432.2 1980.06   435.7 1981.44   478.2 1987.86
     525 1990.74   556.9 1994.81  655.581995.341  715.011998.286812.4417 2001.23
#Mann= 7 ,-1 , 0
       0     .05       0   47.84      .1       0   90.65     .06       0
  184.31    .045       0  239.52      .1       0  655.58     .05       0
  715.01      .1       0
Bank Sta=184.31,239.52
XS Rating Curve= 0 ,0
Exp/Cntr(USF)=0,0
Exp/Cntr=0.3,0.1

Type RM Length L Ch R = 1 ,10521   ,591.2,582.4,587.3
XS GIS Cut Line= 2
2112335.92071335 303526.440631232112164.27644624302646.071648306
#Sta/Elev= 30
       0 1955.59    16.8 1953.43    43.2 1947.48    56.9 1946.84   81.231938.331
   100.4 1936.01   137.1 1921.73  178.811896.104   207.3 1880.81   254.1 1860.84
   264.1 1858.94   297.6 1858.22  304.991856.137   317.6 1855.01   344.4  1855.2
  350.641856.137   357.8 1858.23   363.9 1861.17   404.6 1884.01     448  1918.3
   454.7    1922   485.1 1942.33   514.9 1957.64   552.3 1969.83     575 1978.84
   611.8 1987.13     639 1991.07   678.6 1994.15   778.9 1999.46896.9456 2011.12
#Mann= 5 ,-1 , 0
       0     .05       0   81.23     .06       0  178.81      .1       0
  304.99    .045       0  350.64      .1       0
Bank Sta=304.99,350.64
XS Rating Curve= 0 ,0
Exp/Cntr(USF)=0,0
Exp/Cntr=0.3,0.1

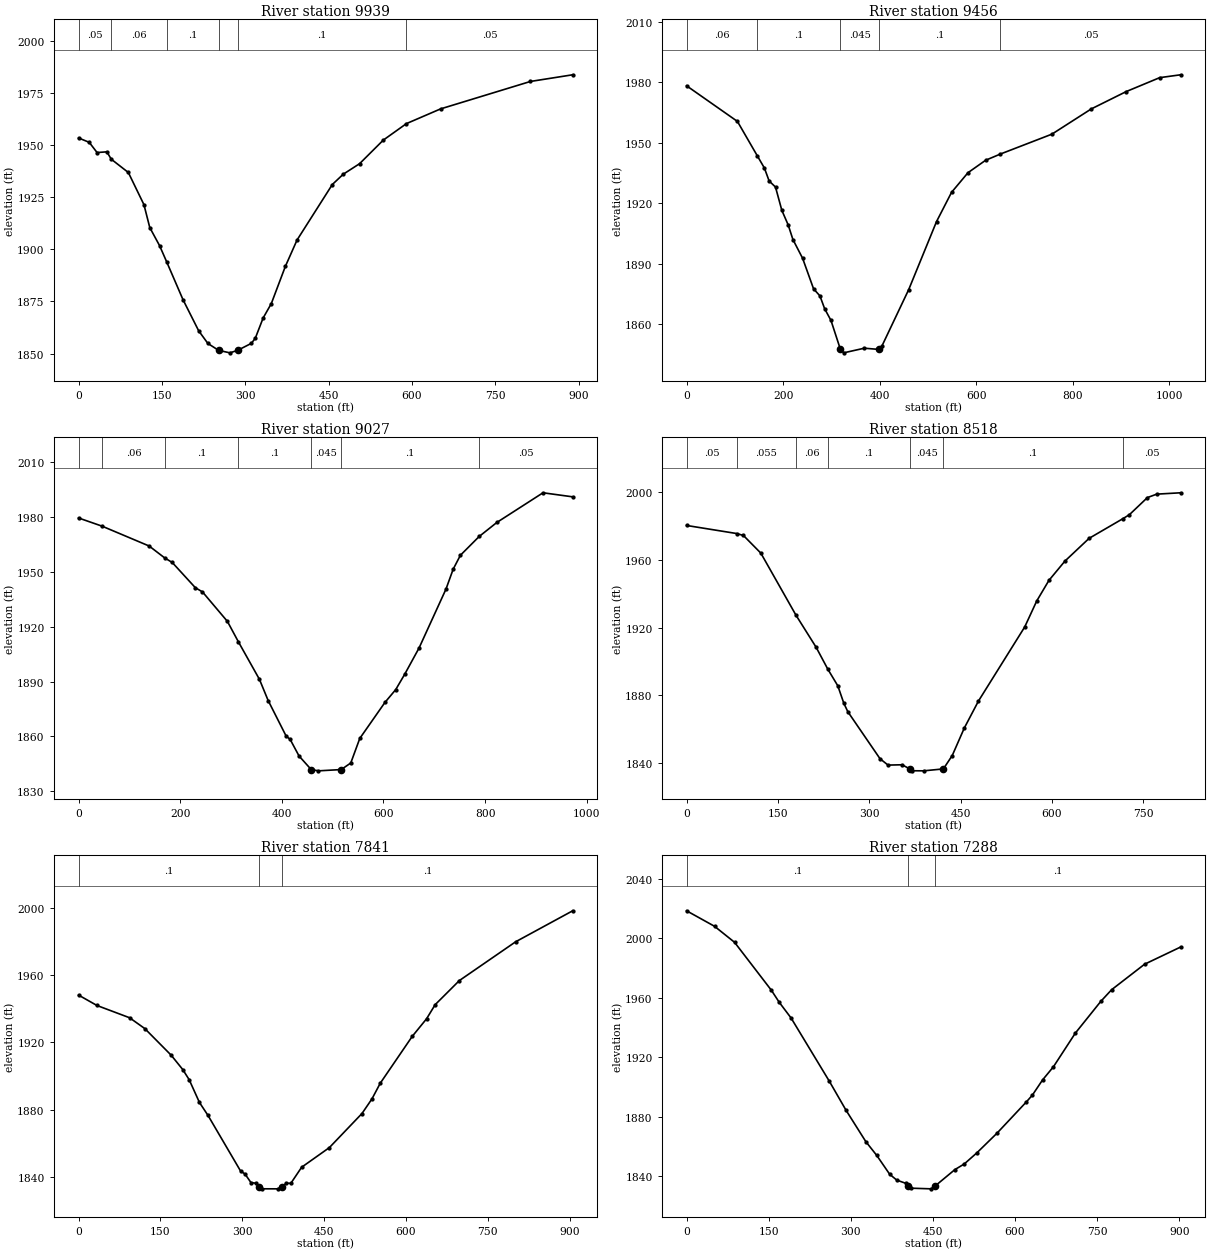
Type RM Length L Ch R = 1 ,9939    ,525,482.6,451.7
XS GIS Cut Line= 3
2112952.36356512 303406.474207982112817.63204363303057.648761916
2112566.62537344 302607.31326541
#Sta/Elev= 30
       0 1953.52    19.2 1951.42    33.3 1946.52    50.9 1946.86   58.911943.313
    89.6 1936.94   117.7 1921.48   128.2 1910.49   145.8 1901.83   158.71893.987
     188 1875.87   216.2 1860.93   232.8 1854.84  252.131851.532   272.4 1850.34
  286.291851.531   311.1  1854.9   318.2 1857.39   332.2 1867.05     347 1874.01
   372.3 1891.89   393.3 1904.52   456.8 1931.17   476.5 1936.12   505.9 1941.17
   548.5 1952.48  590.191960.409   651.7 1967.48   813.5 1980.66 889.505 1983.86
#Mann= 6 ,-1 , 0
       0     .05       0   58.91     .06       0   158.7      .1       0
  252.13    .045       0  286.29      .1       0  590.19     .05       0
Bank Sta=252.13,286.29
XS Rating Curve= 0 ,0
Exp/Cntr(USF)=0,0
Exp/Cntr=0.3,0.1

Type RM Length L Ch R = 1 ,9456    ,433.6,428.9,442.3
XS GIS Cut Line= 3
2113565.11514234302852.7830237512112994.81322258302823.252827259
 2112609.0750309302587.011255321
#Sta/Elev= 30
       0 1978.16   105.3  1960.5  146.221943.555   161.2 1937.38     171 1930.97
   184.2 1927.95   197.3 1916.42   210.4 1909.22   220.3 1901.93   240.3 1892.66
     263 1877.51   276.2    1874     286 1867.62   299.1 1861.83  318.651847.459
   325.4 1845.77   368.1 1848.07   398.91847.456   404.3 1848.99   460.1 1877.14
   517.7 1910.84   548.8 1925.33   582.8 1935.06   619.4 1941.24  650.151944.335
   756.6 1954.17   838.1 1966.67   910.5 1975.28   979.8 1982.181023.398 1983.61
#Mann= 5 ,-1 , 0
       0     .06       0  146.22      .1       0  318.65    .045       0
   398.9      .1       0  650.15     .05       0
Bank Sta=318.65,398.9
XS Rating Curve= 0 ,0
Exp/Cntr(USF)=0,0
Exp/Cntr=0.3,0.1

Type RM Length L Ch R = 1 ,9027    ,497.1,509.2,556.6
XS GIS Cut Line= 3
2113554.04131865302596.2394417252113181.22258794302457.816645668
 2112647.8334138302243.722721099
#Sta/Elev= 30
       0 1979.41   46.241974.938   138.9 1964.09  169.511957.581   184.4 1955.08
   229.9 1941.28   243.9    1939   292.9  1922.9  314.581911.705   355.9 1891.25
   373.1 1879.65   408.5 1860.21   416.3 1858.45   433.9 1849.32  457.831841.918
   472.1 1841.22  516.861841.918   535.7 1845.51   553.4 1858.92   602.9  1878.6
   624.1  1885.6   641.8 1893.99   670.1 1908.37   723.1 1940.57   737.2 1951.42
   751.4 1959.02  788.391969.298   823.2 1976.97     914 1993.18 972.439 1990.96
#Mann= 7 ,-1 , 0
       0     .05       0   46.24     .06       0  169.51      .1       0
  314.58      .1       0  457.83    .045       0  516.86      .1       0
  788.39     .05       0
Bank Sta=457.83,516.86
XS Rating Curve= 0 ,0
Exp/Cntr(USF)=0,0
Exp/Cntr=0.3,0.1

Type RM Length L Ch R = 1 ,8518    ,688,676.9,667.7
XS GIS Cut Line= 3
2113563.26950506302546.4072351452113517.12857304302101.608650481
 2113472.8332783301739.863743451
#Sta/Elev= 30
       0 1980.26   82.071975.517    93.4 1974.35     122 1963.94  179.711927.334
   212.8 1908.42  232.141895.404   248.4 1885.69   258.3 1875.39   264.9 1870.38
   317.7 1842.69   330.9 1838.91     354  1839.1  366.61 1836.66   370.5 1835.57
   389.4 1835.52  421.821836.659   436.4 1844.56   456.2 1860.79   479.4 1876.67
   555.4 1920.38   575.2 1935.76   595.2 1947.87   621.4 1959.22   661.2 1972.67
  716.291984.181   727.3  1986.6     757 1996.73   772.3 1998.74811.6321 1999.54
#Mann= 7 ,-1 , 0
       0     .05       0   82.07    .055       0  179.71     .06       0
  232.14      .1       0  366.61    .045       0  421.82      .1       0
  716.29     .05       0
Bank Sta=366.61,421.82
XS Rating Curve= 0 ,0
Exp/Cntr(USF)=0,0
Exp/Cntr=0.3,0.1

Type RM Length L Ch R = 1 ,7841    ,577,553.4,527.8
XS GIS Cut Line= 3
2114390.11500684302402.4475272452114124.34323841302018.554972846
2113781.05470419301745.400655293
#Sta/Elev= 30
       0 1948.11    33.7 1941.94    93.5 1934.66   121.5  1928.2   169.7 1912.44
   190.9 1903.94   202.7 1897.91   221.5 1884.41   237.2 1876.69     297 1843.64
     305 1841.94   315.9 1836.84     325 1836.43  331.031834.349   336.9 1833.13
   364.9 1833.11  372.971834.348   380.8 1836.48     389 1836.36   408.8 1845.92
   459.7  1857.6   519.4 1877.81   537.7 1886.49   552.9 1895.79   611.5  1923.6
   637.8 1934.05   653.5  1942.4   697.9 1956.73   801.1 1979.76905.6164 1998.15
#Mann= 3 ,-1 , 0
       0      .1       0  331.03    .045       0  372.97      .1       0
Bank Sta=331.03,372.97
XS Rating Curve= 0 ,0
Exp/Cntr(USF)=0,0
Exp/Cntr=0.3,0.1

Type RM Length L Ch R = 1 ,7288    ,391.3,375.5,362.8
XS GIS Cut Line= 2
2114724.17535466301540.5349171292113834.57818533301693.722811432
#Sta/Elev= 30
       0 2018.36    51.1 2007.94    87.7 1997.18   155.1  1964.9   169.3 1956.89
   190.9 1946.37   260.8 1903.89   291.4 1884.35   327.4 1863.37   347.4 1854.08
     371 1841.44     384 1837.47   400.6 1835.32  404.681833.458   410.7 1832.05
   446.7 1831.62  453.81 1833.46   490.2 1844.55   507.2  1848.3   530.5 1855.85
   567.1 1868.99   620.9 1890.06   631.7 1894.55   650.3 1904.74   670.3 1913.66
   710.2  1936.2   756.8 1957.55   776.4 1965.32   836.7 1982.47902.6902 1994.05
#Mann= 3 ,-1 , 0
       0      .1       0  404.68    .045       0  453.81      .1       0
Bank Sta=404.68,453.81
XS Rating Curve= 0 ,0
Exp/Cntr(USF)=0,0
Exp/Cntr=0.3,0.1

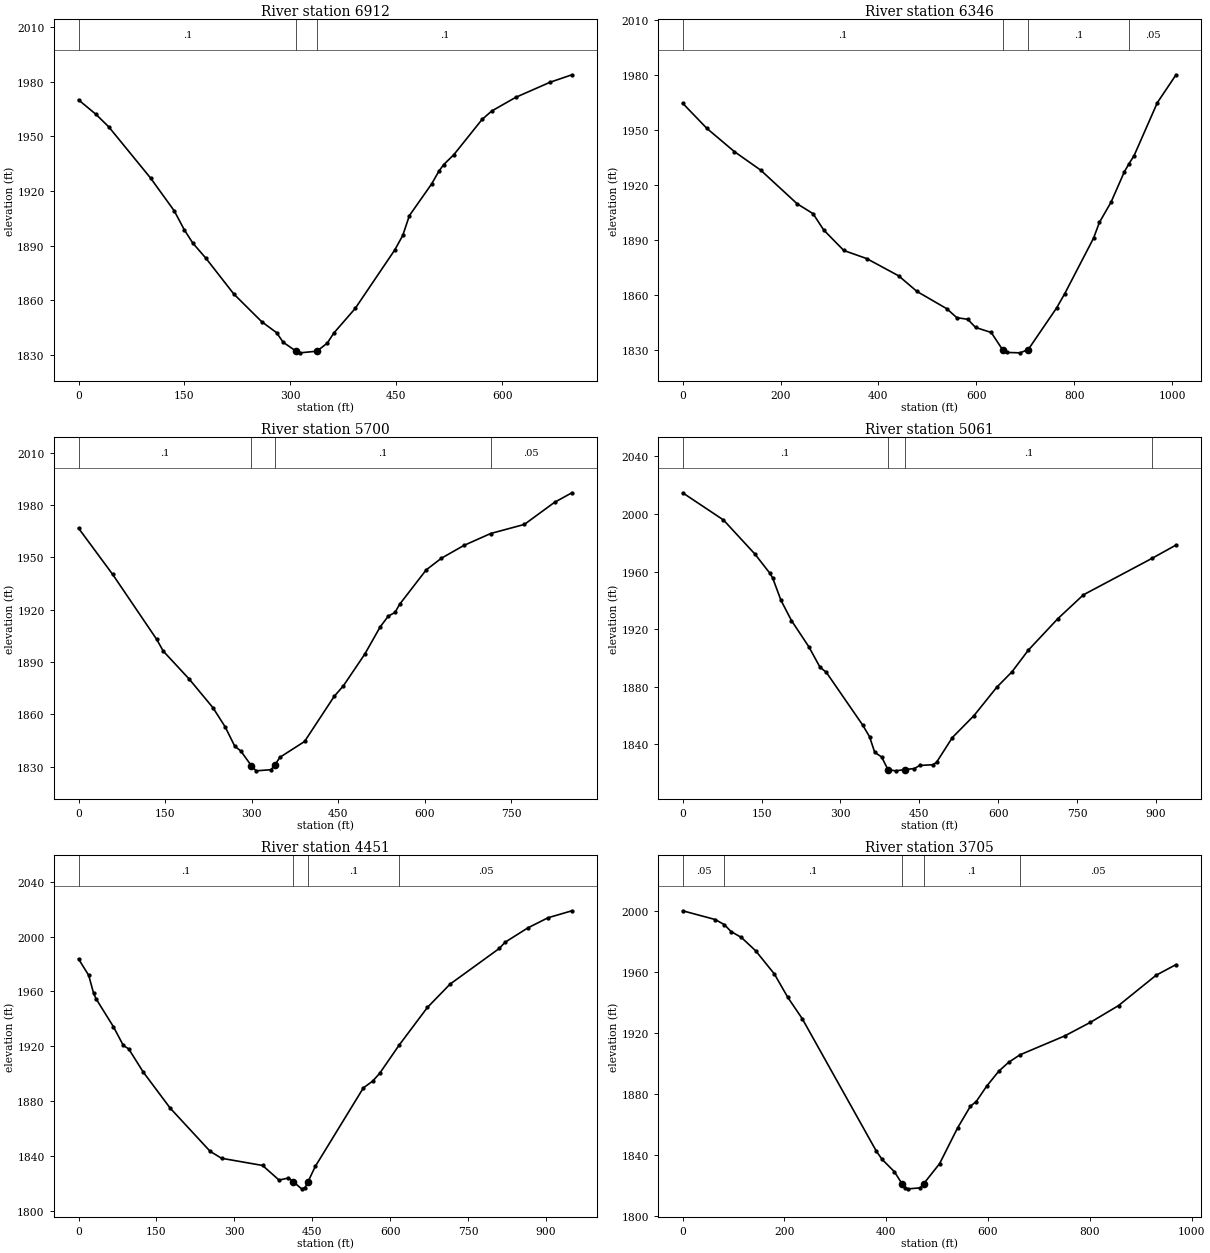
Type RM Length L Ch R = 1 ,6912    ,563.6,566.3,582.1
XS GIS Cut Line= 3
 2114307.0613292301090.1994206232113989.61171691301429.796680283
2113880.71911735301636.508055729
#Sta/Elev= 30
       0 1970.09    24.9 1962.05    42.8 1955.25   101.9 1927.16   135.5  1909.1
   149.9 1898.56   161.9 1891.32   180.5 1882.97   219.9 1863.37   259.4 1848.15
   280.3 1842.18   289.8 1836.85  308.051831.959   313.3 1831.06  337.45 1831.96
   352.2 1836.41   361.3 1841.87   391.7 1855.46   447.8 1887.67     459 1895.56
   468.4 1906.47     500 1923.95   510.2  1930.9     517 1934.52   531.4 1939.98
   571.3 1959.33     585 1963.96     619 1971.48   667.6 1979.77698.5052 1983.87
#Mann= 3 ,-1 , 0
       0      .1       0  308.05    .045       0  337.45      .1       0
Bank Sta=308.05,337.45
XS Rating Curve= 0 ,0
Exp/Cntr(USF)=0,0
Exp/Cntr=0.3,0.1

Type RM Length L Ch R = 1 ,6346    ,627.7,645.9,675.3
XS GIS Cut Line= 4
2114164.94725858300997.9175565852113659.24264366301134.494715361
2113465.45072918301285.8369723842113334.41048224301485.165798706
#Sta/Elev= 30
       0 1964.84    49.6 1951.09   105.8 1938.42   159.4 1928.34   234.1 1909.94
   266.4 1904.59   288.5  1895.6   329.3 1884.48   376.1 1880.06   441.4 1870.65
   478.8 1862.13     540 1852.66   560.2 1847.82   582.7 1846.91   598.6 1842.46
   630.6 1839.74  653.731830.353   662.6 1828.84   689.3 1828.62  706.061830.354
   764.1 1853.08   780.6  1860.8   839.8 1891.25   851.6 1899.77   875.4 1910.82
   902.8  1927.5  912.231931.862   922.5 1936.22   970.1 1965.171008.253 1980.36
#Mann= 4 ,-1 , 0
       0      .1       0  653.73    .045       0  706.06      .1       0
  912.23     .05       0
Bank Sta=653.73,706.06
XS Rating Curve= 0 ,0
Exp/Cntr(USF)=0,0
Exp/Cntr=0.3,0.1

Type RM Length L Ch R = 1 ,5700    ,652.8,639.1,631.4
XS GIS Cut Line= 4
2114183.40363139 300962.850448252113993.30299147300900.098780704
2113799.51107699300743.2196118392113443.30308181300549.427697359
#Sta/Elev= 30
       0 1966.64    59.1 1940.17   135.5 1902.88   146.9 1896.14   191.8 1880.13
   233.1 1863.66   254.1 1852.74   270.7 1841.68   281.1 1838.94   299.7  1830.4
   307.7 1827.53   333.4 1828.18  339.861830.637  339.871830.644   348.9 1835.28
   391.7 1844.35     443 1870.19   458.9 1876.23     496 1894.39   522.6 1909.96
   536.7 1916.19   548.5 1918.36   556.4 1922.97   602.4 1942.69     629 1949.44
     668 1956.77  714.311963.586   772.6 1968.78   824.9 1981.46855.0332 1986.93
#Mann= 4 ,-1 , 0
       0      .1       0   299.7    .045       0  339.87      .1       0
  714.31     .05       0
Bank Sta=299.7,339.86
XS Rating Curve= 0 ,0
Exp/Cntr(USF)=0,0
Exp/Cntr=0.3,0.1

Type RM Length L Ch R = 1 ,5061    ,595.7,609.9,611.2
XS GIS Cut Line= 4
2114550.68545026300289.1928407722114257.22912262300248.588820595
2113956.39024586300239.3606341912113635.24935901300124.931122784
#Sta/Elev= 30
       0 2014.78    77.7 1995.88   137.3 1972.28   165.2 1959.23     171 1955.81
     187 1940.09   206.9 1926.07     240 1907.83   261.2 1893.64   273.1 1890.16
   342.3  1853.5   355.4 1845.38   365.2 1834.56   378.4  1831.3  390.371822.569
   404.9 1821.69  422.751822.569   440.7  1823.3   450.6 1825.42     476 1825.93
   482.8 1827.62   512.9 1844.83   554.1 1860.09   597.2  1879.7   626.2 1890.44
   657.4 1905.54   713.3 1927.32     762 1943.91  892.921969.324938.1512 1978.49
#Mann= 4 ,-1 , 0
       0      .1       0  390.37    .045       0  422.75      .1       0
  892.92     .05       0
Bank Sta=390.37,422.75
XS Rating Curve= 0 ,0
Exp/Cntr(USF)=0,0
Exp/Cntr=0.3,0.1

Type RM Length L Ch R = 1 ,4451    ,740.5,745.7,741.6
XS GIS Cut Line= 4
2114613.43711781299831.4747951432114321.82642745299722.582195578
2114046.82647262299597.0788604862113744.14195857299451.273515305
#Sta/Elev= 30
       0 1983.72    19.6 1971.71      29 1958.69    33.6 1954.72    67.3 1934.16
    86.1 1920.66    96.6 1918.05   124.6 1901.16   176.3 1874.92   253.4 1843.31
   275.2  1838.3   354.2 1833.05   385.9  1822.4     404  1823.9  413.661821.098
   429.2    1816   435.9 1816.94  441.531821.101   455.7 1832.38   548.2 1889.64
   566.3 1894.65   579.5 1900.23  616.731920.689   671.4 1948.31   715.1 1965.35
   809.8 1991.36   820.7 1995.83   864.8 2006.36   903.5 2013.74949.5353 2018.83
#Mann= 4 ,-1 , 0
       0      .1       0  413.66    .045       0  441.53      .1       0
  616.73     .05       0
Bank Sta=413.66,441.53
XS Rating Curve= 0 ,0
Exp/Cntr(USF)=0,0
Exp/Cntr=0.3,0.1

Type RM Length L Ch R = 1 ,3705    ,614.5,593,571.2
XS GIS Cut Line= 4
2115032.39678054299299.9312582832114713.10153097299143.052089418
2114432.56466429298988.018557834 2114297.8331428298727.783701246
#Sta/Elev= 30
       0 1999.83    63.9 1994.11   82.111990.714    95.1 1986.23   115.4 1982.36
   143.6 1973.57   180.2 1958.44   206.7 1943.04     235 1929.12   380.8 1842.18
   391.8 1836.98     416 1828.86  431.031820.956   437.7    1818   443.7 1817.64
   466.7 1818.29  473.481820.961   504.8 1834.13     540 1857.47   565.5 1871.82
   576.8 1874.84     597 1884.76   621.2 1894.78   640.5 1900.54  662.551905.421
   750.9 1917.88   800.9 1926.69   856.3 1937.71   930.1 1957.58969.3225 1964.57
#Mann= 5 ,-1 , 0
       0     .05       0   82.11      .1       0  431.03    .045       0
  473.48      .1       0  662.55     .05       0
Bank Sta=431.03,473.48
XS Rating Curve= 0 ,0
Exp/Cntr(USF)=0,0
Exp/Cntr=0.3,0.1

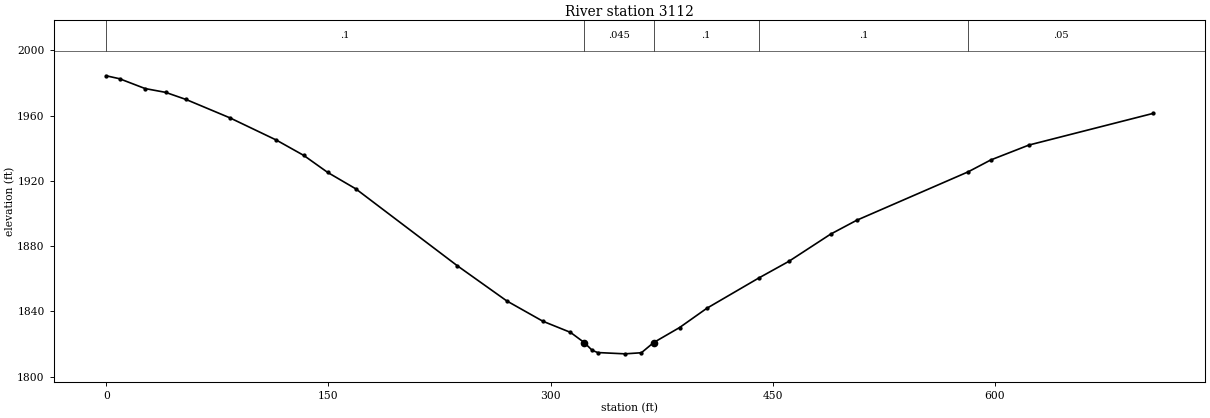
Type RM Length L Ch R = 1 ,3112    ,446.5,472,493.5
XS GIS Cut Line= 3
2114967.79947572298391.8777161482114727.86662922 298471.24011922
2114323.67206473298677.951494666
#Sta/Elev= 30
       0 1984.41       9  1982.6    26.3 1976.57    40.1 1974.25    53.9 1969.89
    83.5 1958.64   114.8 1945.05   133.4  1935.6   149.5 1925.21   168.4 1915.19
     237 1868.04   270.4 1846.48   294.8 1834.01   313.4 1827.21  322.741820.943
   328.1 1816.18   331.8 1814.84   350.2 1814.05   361.3 1814.72  369.541820.948
   387.1 1830.18   405.5 1841.98  440.581860.537   460.8  1870.7     489 1887.37
   506.6 1895.87  581.971925.595   597.1 1932.82   622.9 1941.97706.7031 1961.36
#Mann= 5 ,-1 , 0
       0      .1       0  322.74    .045       0  369.54      .1       0
  440.58      .1       0  581.97     .05       0
Bank Sta=322.74,369.54
XS Rating Curve= 0 ,0
Exp/Cntr(USF)=0,0
Exp/Cntr=0.3,0.1