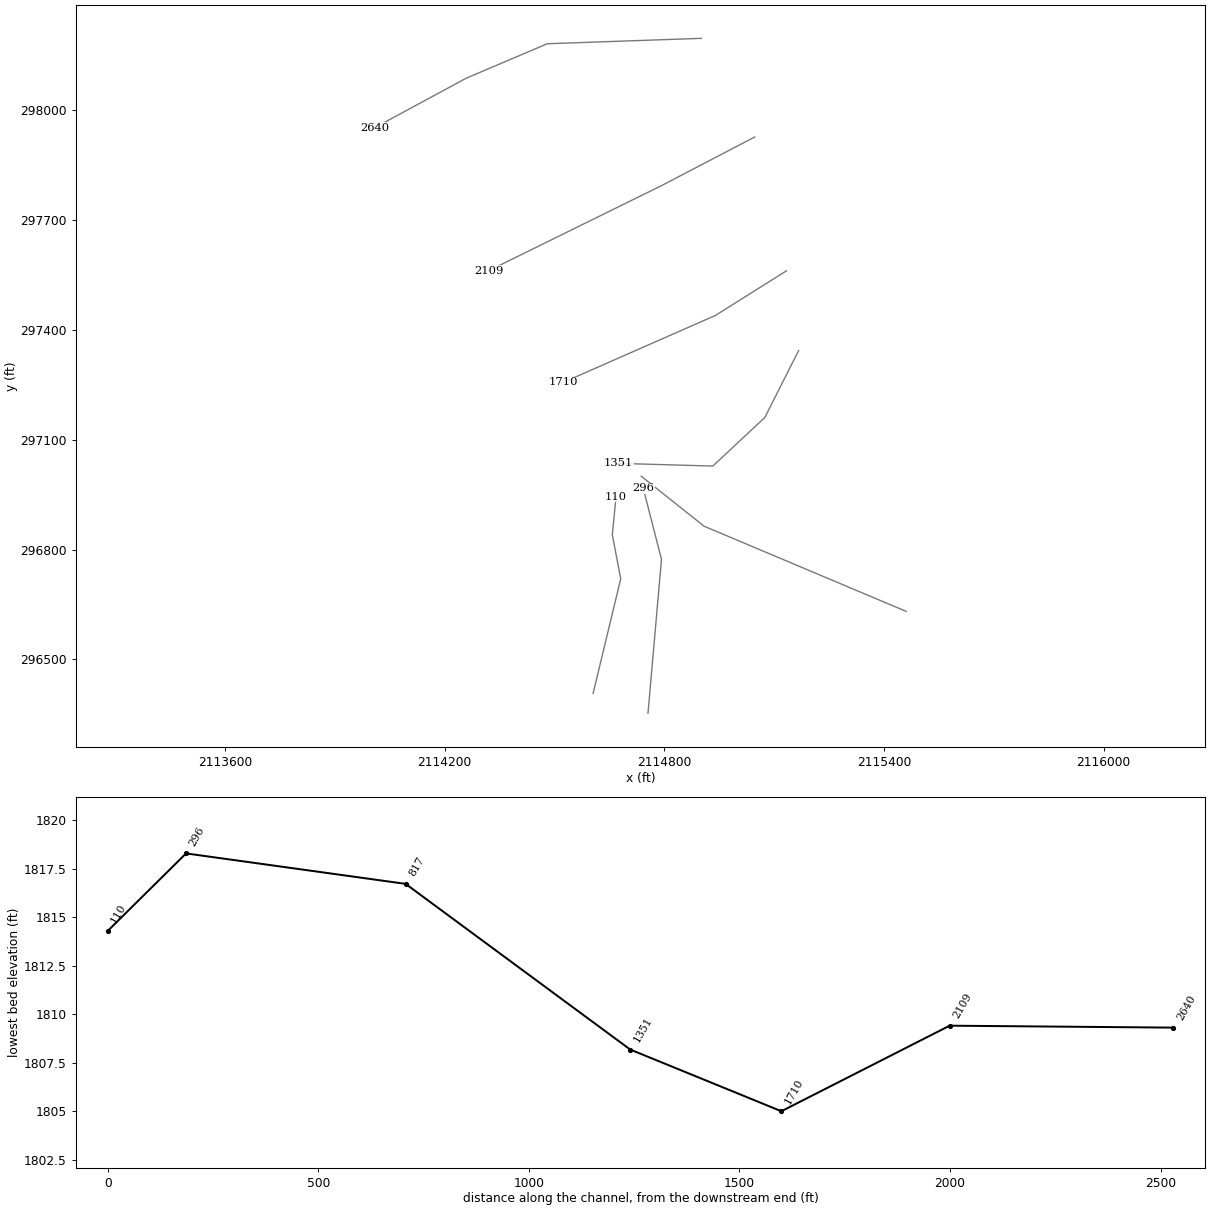
HEC-RAS study MLGNCK.prj: MLGNCK

--- MLGNCK.g01 (geometry) --- (continued)

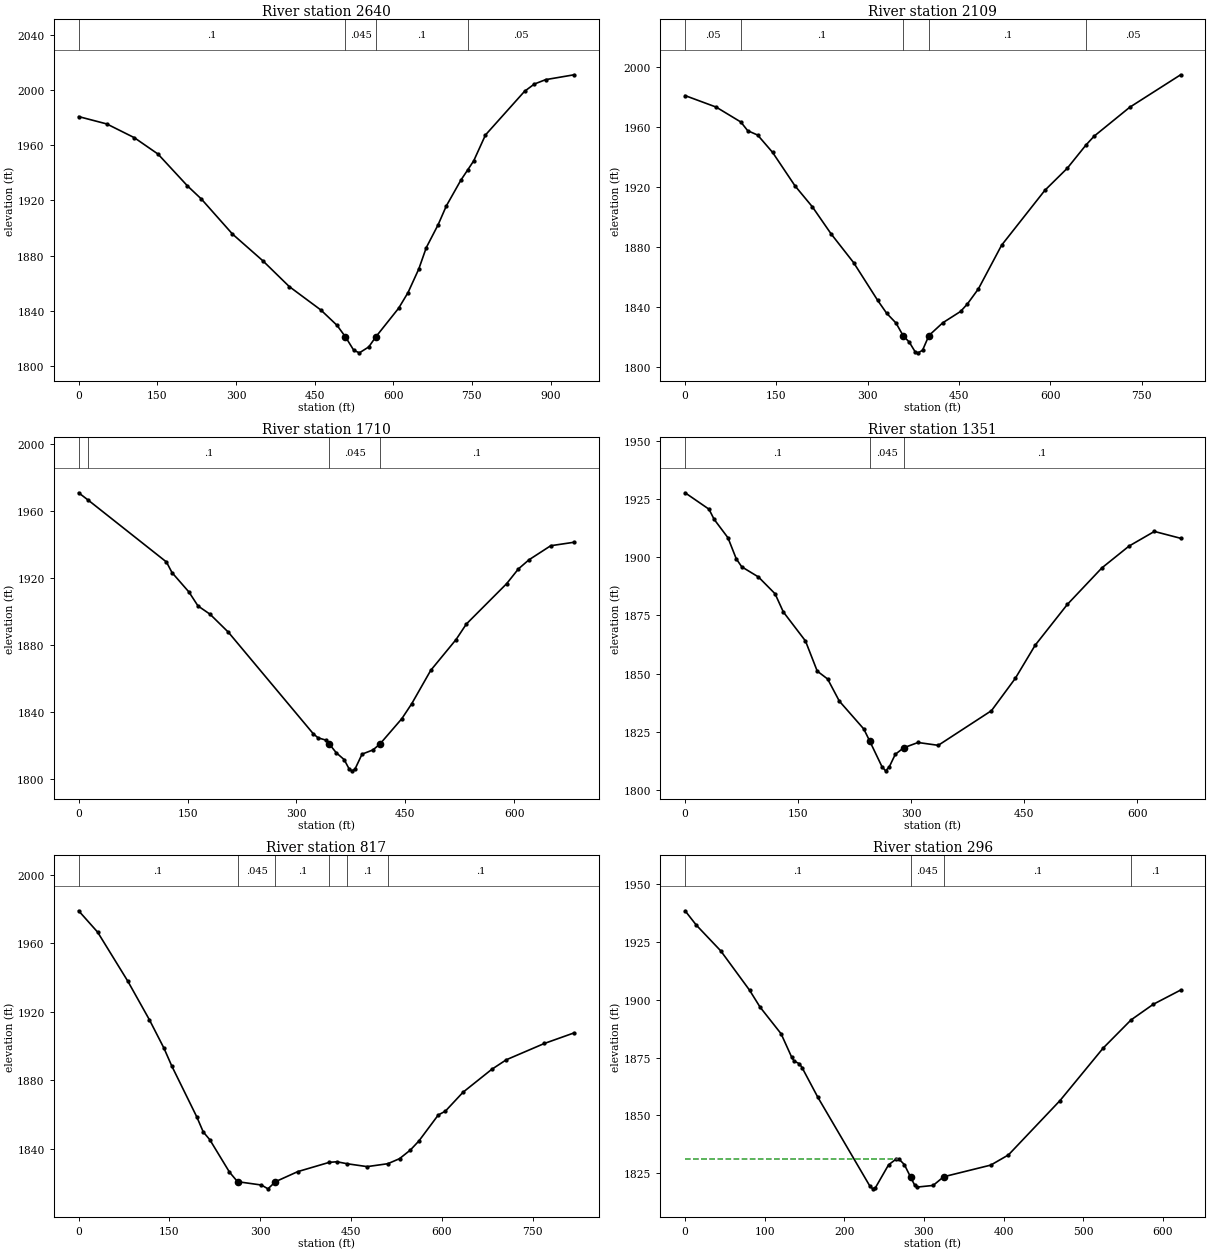
Type RM Length L Ch R = 1 ,2640    ,525.8,531.4,535.7
XS GIS Cut Line= 4
2114901.35653361298196.2401643872114480.55123359298181.475066141
 2114259.0747599298087.347564822  2114009.913727297952.616043326
#Sta/Elev= 30
       0 1980.95    53.7  1975.6   106.2 1965.62   151.4 1953.71   207.4 1930.65
   234.2 1921.01   293.3 1895.63   351.2 1876.22   401.6 1857.48     462 1840.41
   492.7 1829.31  508.751820.945   524.7 1811.16   535.4 1809.31   553.3 1813.62
  566.771820.942   610.3 1841.76   628.1 1853.07   648.6 1870.17     663  1885.8
   685.4 1902.27   701.2 1916.06   728.9 1934.76  742.321942.418   753.4  1948.8
   775.8 1967.58   850.4 1999.33     869 2004.58   890.6 2007.79944.9687 2011.32
#Mann= 4 ,-1 , 0
       0      .1       0  508.75    .045       0  566.77      .1       0
  742.32     .05       0
Bank Sta=508.75,566.77
XS Rating Curve= 0 ,0
Exp/Cntr(USF)=0,0
Exp/Cntr=0.3,0.1

Type RM Length L Ch R = 1 ,2109    ,393.7,399.5,399.5
XS GIS Cut Line= 3
2115047.16187879297926.7771213952114792.46393404297793.891237181
2114319.98079017297561.340939804
#Sta/Elev= 30
       0 1980.69      51 1973.04   91.571963.098   102.8 1957.33   119.2  1954.4
   143.6 1942.93   180.5  1920.6   209.2 1906.55   239.7 1888.67   276.8 1869.47
   316.4 1844.28   331.1 1835.74   346.4 1829.26  357.98 1820.94   368.3 1816.47
   377.7 1810.19   382.6 1809.41     390 1811.12  400.471820.936   423.1 1829.39
   452.4 1836.96   463.4 1841.82   481.7 1851.98   519.8 1881.05   590.9 1917.62
   627.7 1932.32  658.221947.698   671.7 1953.63   730.3 1972.93813.8916 1994.55
#Mann= 5 ,-1 , 0
       0     .05       0   91.57      .1       0  357.98    .045       0
  400.47      .1       0  658.22     .05       0
Bank Sta=357.98,400.47
XS Rating Curve= 0 ,0
Exp/Cntr(USF)=0,0
Exp/Cntr=0.3,0.1

Type RM Length L Ch R = 1 ,1710    ,344.3,359,363
XS GIS Cut Line= 3
2115133.90683099297561.3409398042114940.11491651297439.528879274
2114524.84652833297256.810788478
#Sta/Elev= 30
       0 1970.97   13.56 1966.46     121 1929.65   128.6 1923.34     152 1911.72
   164.4 1903.43   181.1 1898.45   206.3 1887.73   323.2 1827.14   329.8  1824.7
   340.6 1823.34  345.431820.937   354.9 1815.77   365.7 1811.73     373 1805.84
   376.4    1805   380.5 1805.87   390.4 1814.97   405.4 1817.48  414.891820.936
   445.2 1836.14   458.9 1845.12     485 1864.98   519.9 1883.37   534.1 1892.64
   589.6 1916.74   605.8 1925.54   620.2 1930.92   650.3 1939.37682.5853 1941.45
#Mann= 4 ,-1 , 0
       0     .05       0   13.56      .1       0  345.43    .045       0
  414.89      .1       0
Bank Sta=345.43,414.89
XS Rating Curve= 0 ,0
Exp/Cntr(USF)=0,0
Exp/Cntr=0.3,0.1

Type RM Length L Ch R = 1 ,1351    ,535.4,533.3,451.3
XS GIS Cut Line= 4
2115167.12830204297343.555740674  2115074.846438297160.837649879
2114932.73236738297027.9517656642114674.34314808297035.334314787
#Sta/Elev= 30
       0 1927.78    31.7 1920.72    38.5 1916.38    56.9 1908.43    67.9 1899.38
    75.2 1895.93    97.3 1891.58   119.4 1884.35   130.4 1876.52   159.8 1864.03
   175.4 1851.07   189.2 1847.68   204.7 1838.18   237.2 1826.18  245.131820.936
   261.3 1809.99   266.1 1808.18   270.9 1809.81     279 1815.28   290.2  1818.1
   309.2 1820.37     336 1819.15   406.7 1834.07   438.3 1847.96   464.6 1862.18
   507.3 1879.73   553.2 1895.46   589.3 1904.86   622.9 1911.15657.7579  1908.2
#Mann= 3 , 0 , 0
       0      .1       0  245.13    .045       0   290.2      .1       0
Bank Sta=245.13,290.2
XS Rating Curve= 0 ,0
Exp/Cntr(USF)=0,0
Exp/Cntr=0.3,0.1

Type RM Length L Ch R = 1 ,817     ,538.7,521.3,456.4
XS GIS Cut Line= 3
2115460.58462968  296631.13975032114908.73908273296863.690047676
2114737.09481562297000.267206453
#Sta/Elev= 30
       0 1979.03    31.3  1966.6    81.2 1937.93   116.8 1915.44   140.8 1898.89
   153.9 1888.34   195.1 1858.71   205.8  1849.9   216.5 1845.44   249.1 1826.45
  262.381820.901   301.9 1818.94   312.6 1816.72  325.051820.902   361.8 1826.77
  413.791832.181   426.5 1832.53   443.51831.356   476.4 1829.69  510.491831.387
   529.8 1834.32   547.6 1839.33   561.8 1844.65   593.8 1859.83   605.5 1862.05
   634.7 1873.11     682 1886.45   706.2 1892.07     769 1901.58818.1946 1907.77
#Mann= 6 ,-1 , 0
       0      .1       0  262.38    .045       0  325.05      .1       0
  413.79      .1       0   443.5      .1       0  510.49      .1       0
Bank Sta=262.38,325.05
XS Rating Curve= 0 ,0
Exp/Cntr(USF)=0,0
Exp/Cntr=0.3,0.1

Type RM Length L Ch R = 1 ,296     ,184.6,186.2,169.4
XS GIS Cut Line= 3
2114755.55118843296352.4485209052114792.46393404296773.253820919
2114742.63172746296967.045735399
#Sta/Elev= 30
       0 1938.45    14.2 1932.21    44.8 1921.12      81 1904.12    94.2 1896.81
   120.6  1885.3   133.7 1875.33     137 1873.49   143.6 1872.35   146.9 1870.71
   166.7 1857.89   232.2 1819.43   235.8 1818.29   239.1 1818.78   255.6 1828.67
   265.5 1831.25   268.8 1831.09   275.4  1828.8   283.4 1823.28   288.5 1819.81
   291.8 1819.06   311.6 1819.76   324.8 1823.51     384 1828.55   406.2 1832.95
     471 1856.44   525.2 1879.12  560.27  1891.3   588.1 1898.03622.5175 1904.19
#Mann= 4 ,-1 , 0
       0      .1       0   283.4    .045       0   324.8      .1       0
  560.27      .1       0
#XS Ineff= 2 , 0
          267.37 1831.24
Permanent Ineff=
       F       F
Bank Sta=283.4,324.8
XS Rating Curve= 0 ,0
Exp/Cntr(USF)=0,0
Exp/Cntr=0.3,0.1

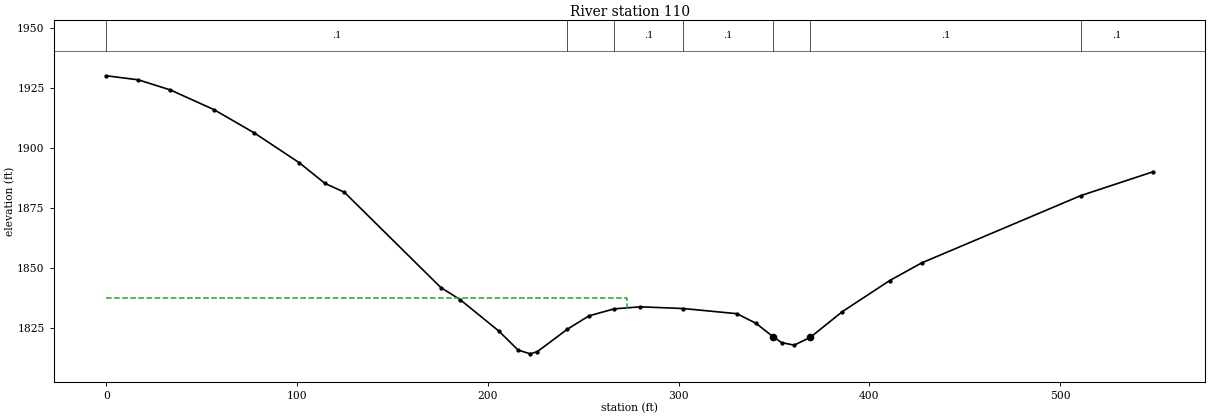
Type RM Length L Ch R = 1 ,110     ,110,110,110
XS GIS Cut Line= 4
2114605.64276973296407.0047632722114681.11897117296720.032377655
2114658.07886757296840.7942999552114668.40718987296944.077522975
#Sta/Elev= 30
       0 1930.14    16.8 1928.46    33.7 1924.22    56.5 1916.03    77.5 1906.39
   101.2 1893.92   114.7 1885.28   124.8 1881.64   175.4 1841.92   185.5 1836.89
   205.8 1823.79   215.9 1815.87   222.3 1814.29     226 1815.21  241.67 1824.52
     253  1830.1  266.221833.025     280 1833.88  302.351833.177   330.6 1831.02
   340.6 1827.02   349.4  1821.5     354 1818.99   360.6 1817.91   369.1 1821.18
   385.9 1831.89   410.7 1844.83   427.4 1852.16  510.791880.196548.7369 1890.15
#Mann= 7 ,-1 , 0
       0      .1       0  241.67      .1       0  266.22      .1       0
  302.35      .1       0   349.4    .045       0   369.1      .1       0
  510.79      .1       0
#XS Ineff= 2 , 0
          272.82 1837.47
Permanent Ineff=
       F       F
Bank Sta=349.4,369.1
XS Rating Curve= 0 ,0
Exp/Cntr(USF)=0,0
Exp/Cntr=0.3,0.1
Stream Node=BIGCLEARCK      ,Main            , 0 , 0 ,Upstream end
Stream Node=BIGCLEARCK      ,Main            , 0 , 1 ,Downstream end
Stream Node=BROADRN         ,Main            , 0 , 0 ,Upstream end
Stream Node=BROADRN         ,Main            , 0 , 1 ,Downstream end
Stream Node=LAURELBR        ,Main            , 0 , 0 ,Upstream end
Stream Node=LAURELBR        ,Main            , 0 , 1 ,Downstream end
Stream Node=LAURELCK1       ,Main            , 0 , 0 ,Upstream end
Stream Node=LAURELCK1       ,Main            , 0 , 1 ,Downstream end
Stream Node=MEADOWRV3       ,Main            , 0 , 0 ,Upstream end
Stream Node=MEADOWRV3       ,Main            , 0 , 1 ,Downstream end
Stream Node=MEADOWRV4       ,Main            , 0 , 0 ,Upstream end
Stream Node=MEADOWRV4       ,Main            , 0 , 1 ,Downstream end
Stream Node=MLGNCK          ,Main            , 0 , 0 ,Upstream end
Stream Node=MLGNCK          ,Main            , 0 , 1 ,Downstream end
Stream Node=MLGNCKTR3       ,Main            , 0 , 0 ,Upstream end
Stream Node=MLGNCKTR3       ,Main            , 0 , 1 ,Downstream end
Stream Node=MLGNCKTR4       ,Main            , 0 , 0 ,Upstream end
Stream Node=MLGNCKTR4       ,Main            , 0 , 1 ,Downstream end
Stream Node=MUDDYCK         ,Main            , 0 , 0 ,Upstream end
Stream Node=MUDDYCK         ,Main            , 0 , 1 ,Downstream end
Stream Node=SECONDCK        ,Main            , 0 , 0 ,Upstream end
Stream Node=SECONDCK        ,Main            , 0 , 1 ,Downstream end
Stream Node=TUCKHORN        ,Main            , 0 , 0 ,Upstream end
Stream Node=TUCKHORN        ,Main            , 0 , 1 ,Downstream end
Stream Node=TUCKHORNT2      ,Main            , 0 , 0 ,Upstream end
Stream Node=TUCKHORNT2      ,Main            , 0 , 1 ,Downstream end
LCMann Table=0

Chan Stop Cuts=-1
Use User Specified Reach Order=0
Composite Channel Slope=5